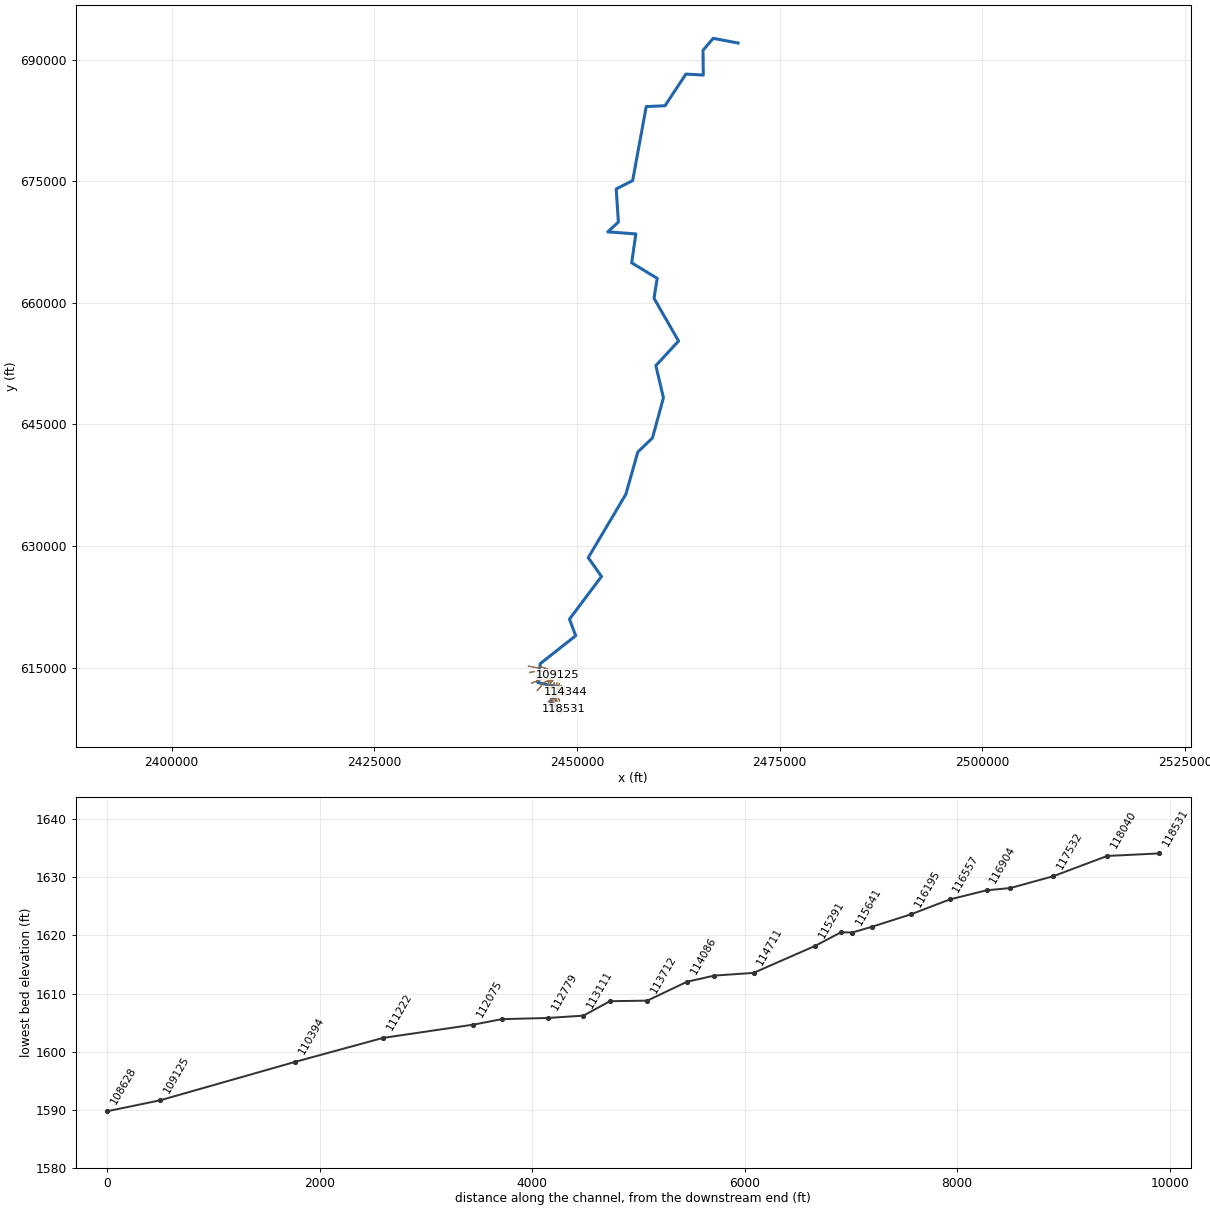
--- SBPOTOMC.prj (project) ---

Proj Title=SBPOTOMC
Current Plan=p01
Default Exp/Contr=0,0
English Units
Geom File=g01
Flow File=f01
Plan File=p01
BEGIN DESCRIPTION:
Stream Name: South Branch Potomac River
Flood Zone: Zone A
Pendleton County, WV
WVDHSEM Flood Warning & Analysis Mapping
HEC-RAS Version: 5.0.7
Hydrology Method:
Regression with Gage Weighting
Model Notes:
Model extends beyond county boundary in the downstream portion and normal depth used as boundary condition.
END DESCRIPTION:
DSS File=dss
DSS Export Rating Curves= 0
DSS Export Rating Curve Sorted= 0
DSS Export Volume Flow Curves= 0
DXF OffsetX= 0
DXF OffsetY= 0
DXF ScaleX= 0
DXF ScaleY= 0

--- SBPOTOMC.p01 (plan) ---

Plan Title=Floodplain
Program Version=5.07
Short Identifier=Floodplain
Geom File=g01
Flow File=f01
Subcritical Flow
K Sum by GR= 0
Std Step Tol= 0.01
Critical Tol= 0.01
Num of Std Step Trials= 20
Max Error Tol= 0.3
Flow Tol Ratio= 0.001
Split Flow NTrial= 30
Split Flow Tol= 0.02
Split Flow Ratio= 0.02
Log Output Level= 0
Friction Slope Method= 1
Unsteady Friction Slope Method= 2
Unsteady Bridges Friction Slope Method= 1
Parabolic Critical Depth
Global Vel Dist= 0 , 0 , 0
Global Log Level= 0
CheckData=True
Encroach Param=-1 ,0,0, 0
Computation Interval=0.1SEC
Output Interval=1MIN
Instantaneous Interval=Max Profile
Mapping Interval=1HOUR
Computation Time Step Use Courant=        0
Computation Time Step Use Time Series=    0
Computation Time Step Count To Double=0
Computation Time Step Max Doubling=0
Computation Time Step Max Halving=0
Computation Time Step Residence Courant=0
Run HTab= 0
Run UNet= 0
Run Sediment= 0
Run PostProcess= 0
Run WQNet= 0
Run RASMapper= 0
UNET Theta= 0
UNET Theta Warmup= 0
UNET ZTol= 0
UNET ZSATol= 0
UNET MxIter= 0
UNET Max Iter WO Improvement= 0
UNET MaxInSteps= 0
UNET DtIC= 0
UNET DtMin= 0
UNET MaxCRTS= 0
UNET WFStab= 0
UNET SFStab= 0
UNET WFX= 1
UNET SFX= 1
UNET 1D Methodology=Finite Difference
UNET DSS MLevel= 1
UNET Pardiso=0
UNET DZMax Abort= 0
UNET Use Existing IB Tables= 0
UNET Froude Reduction=False
UNET Froude Limit= 0
UNET Froude Power= 0
UNET D1 Cores= 0
UNET D2 Coriolis=0
UNET D2 Cores= 0
UNET D2 Theta= 1
UNET D2 Theta Warmup= 1
UNET D2 Z Tol= 0.01
UNET D2 Volume Tol= 0.01
UNET D2 Max Iterations= 20
UNET D2 Equation= 0
UNET D2 RampUpFraction=0.1
UNET D2 TimeSlices= 1
UNET D2 BCVolumeCheck=0
UNET D1D2 MaxIter= 0
UNET D1D2 ZTol=0.01
UNET D1D2 QTol=0.1
UNET D1D2 MinQTol=1
DSS File=dss
Write IC File= 0
Write IC File at Fixed DateTime=0
Write IC File at Sim End=0
Echo Input=False
Echo Parameters=False
Echo Output=False
Write Detailed= 0
HDF Write Warmup=0
HDF Write Time Slices=0
HDF Flush=0
HDF Face Node Velocities=0
HDF Compression= 1
HDF Chunk Size= 1
HDF Spatial Parts= 1
HDF Use Max Rows=0
HDF Fixed Rows= 1
Calibration Method= 0
Calibration Iterations= 20
Calibration Max Change=0.05
Calibration Tolerance=0.2
Calibration Maximum=1.5
Calibration Minimum=0.5
Calibration Optimization Method= 1
WQ AD Non Conservative
WQ ULTIMATE=-1
WQ Max Comp Step=1HOUR
WQ Output Interval=15MIN
WQ Output Selected Increments= 0
WQ Output face flow=0
WQ Output face velocity=0
WQ Output face area=0
WQ Output face dispersion=0
WQ Output cell volume=0
WQ Output cell surface area=0
WQ Output cell continuity=0
WQ Output cumulative cell continuity=0
WQ Output face conc=0
WQ Output face dconc_dx=0
WQ Output face courant=0
WQ Output face peclet=0
WQ Output face adv mass=0
WQ Output face disp mass=0
WQ Output cell mass=0
WQ Output cell source sink temp=0
WQ Output nsm pathways=0
WQ Output nsm derived pathways=0
WQ Output MaxMinRange=-1
WQ Daily Max Min Mean=-1
WQ Daily Range=0
WQ Daily Time=0
WQ Create Restart=0
WQ Fixed Restart=0
WQ System Summary=0
WQ Write To DSS=0
WQ Use Fixed Temperature=0
Sorting and Armoring Iterations= 10
XS Update Threshold= 0.02
Bed Roughness Predictor= 0
Hydraulics Update Threshold= 0.02
Energy Slope Method= 1
Volume Change Method= 1
Sediment Retention Method= 0
XS Weighting Method= 0
Number of US Weighted Cross Sections= 1
Number of DS Weighted Cross Sections= 1
Upstream XS Weight=0
Main XS Weight=1
Downstream XS Weight=0
Number of DS XS's Weighted with US Boundary= 1
Upstream Boundary Weight= 1
Weight of XSs Associated with US Boundary= 0
Number of US XS's Weighted with DS Boundary= 1
Downstream Boundary Weight= 0.5
Weight of XSs Associated with DS Boundary= 0.5
Percentile Method= 0
Sediment Output Level= 3
Mass or Volume Output= 0
Output Increment Type= 1
Profile and TS Output Increment= 1
XS Output Flag= 0
XS Output Increment= 10
Write Gradation File= 0
Read Gradation Hotstart= 0
Write HDF5 File= 1
Write Binary Output= 1
Write DSS Sediment File= 0
SV Curve= 0
Specific Gage Flag= 0

--- SBPOTOMC.f01 (steady flow) ---

Flow Title=Flows
Program Version=5.07
Number of Profiles= 6
Profile Names=P100yr,P10yr,P25yr,P50yr,P500yr,P101yr
River Rch & RM=SBPOTOMC,Main            ,118531
   34933   14174   21178   27582   57757   45460
River Rch & RM=SBPOTOMC,Main            ,96393
   39297   15914   23718   30932   65320   50229
River Rch & RM=SBPOTOMC,Main            ,54620
   44175   17954   26698   34792   73271   55861
Boundary for River Rch & Prof#=SBPOTOMC,Main            , 1
Up Type= 0
Dn Type= 3
Dn Slope=0.00018
Boundary for River Rch & Prof#=SBPOTOMC,Main            , 2
Up Type= 0
Dn Type= 3
Dn Slope=0.00018
Boundary for River Rch & Prof#=SBPOTOMC,Main            , 3
Up Type= 0
Dn Type= 3
Dn Slope=0.00018
Boundary for River Rch & Prof#=SBPOTOMC,Main            , 4
Up Type= 0
Dn Type= 3
Dn Slope=0.00018
Boundary for River Rch & Prof#=SBPOTOMC,Main            , 5
Up Type= 0
Dn Type= 3
Dn Slope=0.00018
Boundary for River Rch & Prof#=SBPOTOMC,Main            , 6
Up Type= 0
Dn Type= 3
Dn Slope=0.00018
DSS Import GetInterval= 0
DSS Import GetPeak= 0
DSS Import FillOption= 0

--- SBPOTOMC.g01 (geometry) ---

Geom Title=Geometry
Program Version=5.07

River Reach=SBPOTOMC        ,Main
Reach XY= 30
2448111.99937814609689.9446266442446671.27400005610822.202000007
2448023.50100005612558.4370000062445146.92400002613165.268999994
2445469.60400006615494.7270000282449840.94986314618939.487990513
2449071.12550014620984.2525683052453024.26800004626248.281000003
2451390.05199909628573.4847492432456020.86200002636377.223000005
2457505.69900009641605.3720000242459311.56800002643342.448000014
2460664.18600005 648292.88000001      2459732.03652268.979000017
2462530.44037259655294.9691565192459502.72799999660575.286000013
2459896.16200006663029.7155000122456743.29100004664947.381999999
2457265.31400004668512.9259999992453794.55199999668763.273000002
2455108.32600006669975.6860000342454838.52900004674058.052000001
2456867.76900008675091.7050000132458542.88600004684221.968999997
2460859.13800004684326.5620000212463435.40300003688231.291000023
     2465583.815688111.7910000232465545.64800006691156.199000031
2466802.25300005692641.4319999962469871.33200005692064.469000027

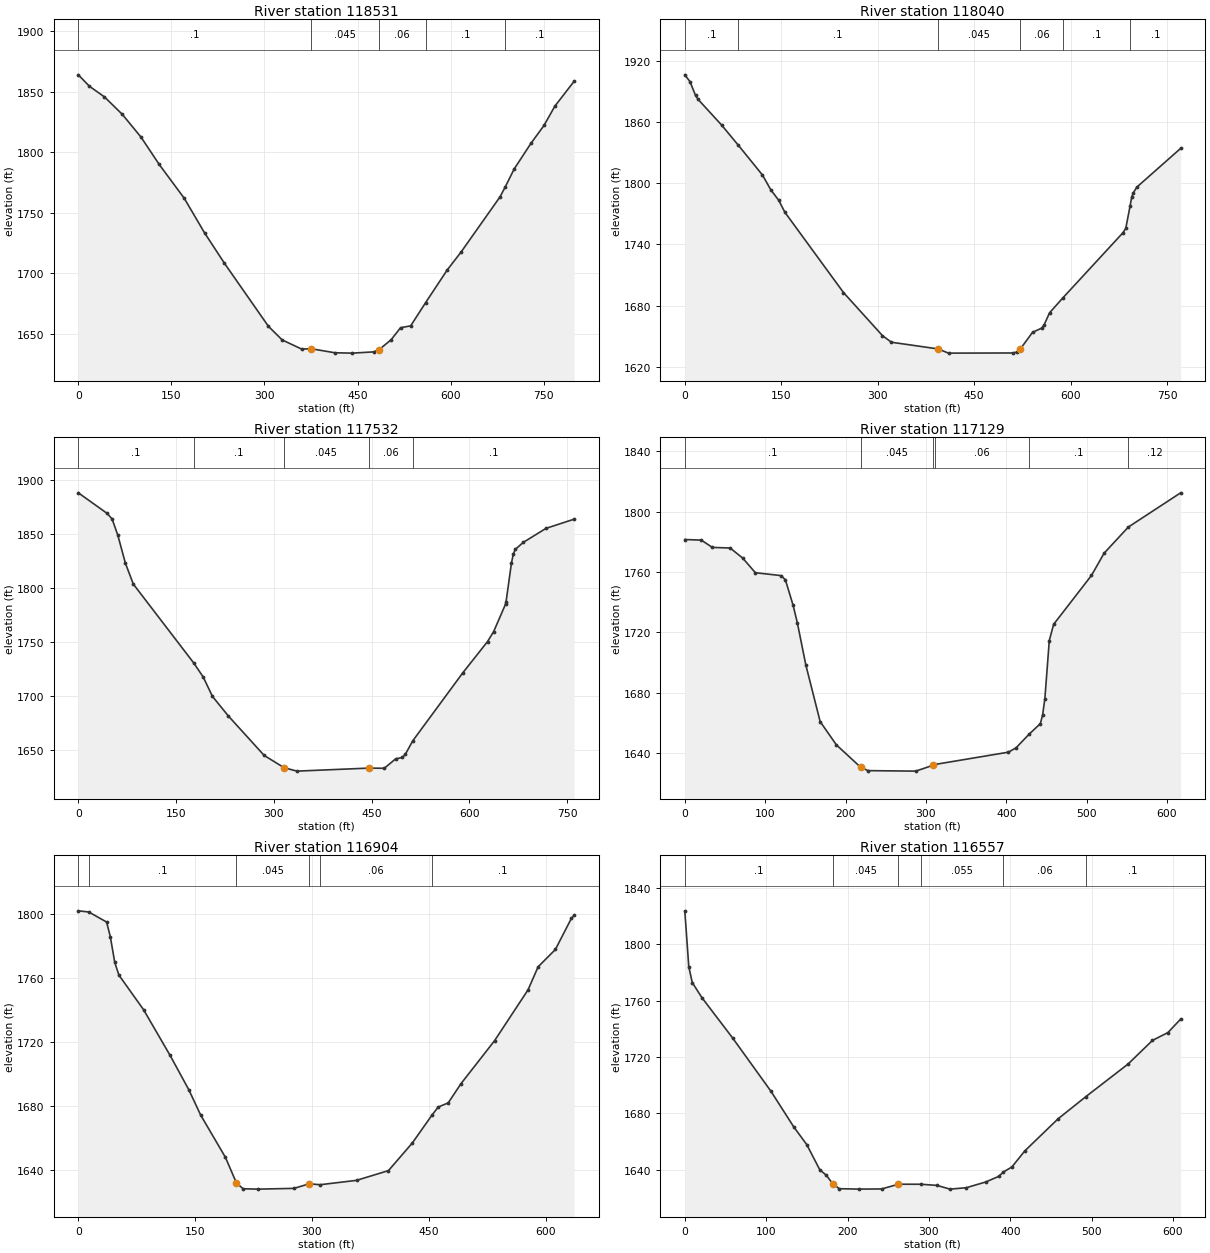
Type RM Length L Ch R = 1 ,118531  ,453.6,490.6,522
XS GIS Cut Line= 6
2447851.46899772609359.9599980562447972.65307172609545.445825592
2448096.56331111609675.4756318332448111.99937811609689.944626629
2448196.85035282609769.4796737132448390.61446978609943.622068688
#Sta/Elev= 30
       0 1864.09    17.8 1854.67    42.1 1845.86      71 1831.36   101.1 1812.57
   130.3 1790.07   170.7 1762.08   203.4 1733.56   235.4 1708.45   306.4 1656.27
   328.5 1645.04   359.9 1637.47   375.4 1637.73   413.6  1634.4   441.9 1634.11
   476.4 1635.15   484.4 1636.81   504.2  1645.2   519.3 1655.09   535.7 1656.66
  559.881675.925   594.6 1702.84   616.5 1717.35   679.8 1763.31  688.241771.588
   702.5 1786.27   729.4 1807.35   750.6 1822.27   768.1 1838.19   799.2 1858.82
#Mann= 5 ,-1 , 0
       0      .1       0   375.4    .045       0   484.4     .06       0
  559.88      .1       0  688.24      .1       0
Bank Sta=375.4,484.4
XS Rating Curve= 0 ,0
Exp/Cntr(USF)=0,0
Exp/Cntr=0.3,0.1

Type RM Length L Ch R = 1 ,118040  ,513.6,508.4,494.6
XS GIS Cut Line= 4
2447507.09266385609515.5125602962447606.01843854609750.461275175
 2447744.5145231610057.1311767012447833.54772032610212.939271831
#Sta/Elev= 30
       0 1905.99       8 1899.41    16.7 1885.82    20.6    1882    57.3  1856.8
   83.171837.151   120.8 1807.91   133.6 1793.59   145.9 1783.36   155.6 1771.51
   246.7 1692.98   307.2 1650.89   321.2 1644.33  393.851637.785     410 1633.67
   509.8 1633.82   515.8 1634.63  521.731637.784   540.7 1654.05   555.1  1658.2
   558.5 1661.16   567.2 1673.18     5881687.858     681 1751.32   685.6 1755.66
  692.311777.611   694.8  1786.1     697 1790.08   702.8 1796.12   770.9 1833.98
#Mann= 6 ,-1 , 0
       0      .1       0   83.17      .1       0  393.85    .045       0
  521.73     .06       0     588      .1       0  692.31      .1       0
Bank Sta=393.85,521.73
XS Rating Curve= 0 ,0
Exp/Cntr(USF)=0,0
Exp/Cntr=0.3,0.1

Type RM Length L Ch R = 1 ,117532  ,414.1,403.2,371.2
XS GIS Cut Line= 4
2447019.88322352609782.6121519482447143.54044188609987.883134421
2447306.76797011610269.8215922752447410.64003353610435.522264874
#Sta/Elev= 30
       0 1888.09    44.3 1868.98    51.8 1863.86    60.6 1848.85    72.2 1822.91
    84.4 1803.52   177.1 1730.42   191.8 1717.26   205.8  1699.5   230.3 1681.26
   285.2 1644.74   315.9 1633.33   335.6 1630.18   445.6 1632.98   469.6 1632.83
   487.1 1641.59   497.3 1642.82   501.8 1645.64  513.131658.156   590.3 1721.45
   628.1 1750.28   637.5 1759.57   655.7 1784.95   656.4 1786.73   664.8  1823.2
   667.7 1831.49   670.6 1835.65   682.7 1842.08   717.8 1855.16     761 1863.69
#Mann= 5 ,-1 , 0
       0      .1       0   177.1      .1       0   315.9    .045       0
   445.6     .06       0  513.13      .1       0
Bank Sta=315.9,445.6
XS Rating Curve= 0 ,0
Exp/Cntr(USF)=0,0
Exp/Cntr=0.3,0.1

Type RM Length L Ch R = 1 ,117129  ,233.2,224.3,201.2
XS GIS Cut Line= 4
2446725.57904383610143.6912295512446817.08538542610252.509581705
2447039.66837846610497.3508740532447148.48673062610591.330360004
#Sta/Elev= 30
       0 1781.54    20.5 1781.17    34.3 1776.32    56.4 1775.92    72.1 1769.24
    87.8 1759.55   119.9 1757.64   125.2 1754.79   134.8 1737.91   140.1 1726.18
   150.6 1698.43   168.4 1660.97   188.6 1645.55   218.7 1630.76   227.9 1628.48
   287.4 1628.15   309.3 1632.12  311.231632.566   402.7 1640.71   412.2 1643.62
  428.121652.484   442.4 1659.61   445.2 1665.39     448 1676.17   453.5 1714.64
   458.9 1725.37     506 1757.78   521.7 1772.49  551.841789.802   616.9 1812.47
#Mann= 6 ,-1 , 0
       0      .1       0   218.7    .045       0   309.3      .1       0
  311.23     .06       0  428.12      .1       0  551.84     .12       0
Bank Sta=218.7,309.3
XS Rating Curve= 0 ,0
Exp/Cntr(USF)=0,0
Exp/Cntr=0.3,0.1

Type RM Length L Ch R = 1 ,116904  ,372.5,347.1,260.1
XS GIS Cut Line= 4
2446567.29780434610356.3816451262446676.11615649610450.361131077
2446923.43059321 610638.320102982447094.07755454610702.621856526
#Sta/Elev= 30
       0  1801.9   13.411801.181    36.3 1794.89    41.1 1785.68    46.8 1769.59
    52.1  1761.7    83.8 1740.02   117.7 1711.57     142 1689.84   157.1 1674.11
   188.9 1647.67   203.1 1631.57   211.7 1627.98   230.6 1627.76   276.9 1628.23
   296.7 1631.11  310.491630.513   357.3 1633.25   398.3 1639.34   428.9  1656.6
  454.581674.333   462.2 1679.11   475.1 1681.75   491.6 1693.85   534.6 1720.66
   577.6 1752.48   590.5 1766.87   612.7 1777.72   633.2 1797.15   636.8    1799
#Mann= 6 ,-1 , 0
       0     .05       0   13.41      .1       0   203.1    .045       0
   296.7      .1       0  310.49     .06       0  454.58      .1       0
Bank Sta=203.1,296.7
XS Rating Curve= 0 ,0
Exp/Cntr(USF)=0,0
Exp/Cntr=0.3,0.1

Type RM Length L Ch R = 1 ,116557  ,398.6,362.5,239.6
XS GIS Cut Line= 4
2446465.89888528610821.3327861492446574.71723744610836.171652352
2446911.06487137610843.5910854532447061.92667777610781.762476275
#Sta/Elev= 30
       0 1823.67     4.9 1784.01     9.2 1772.75      21 1762.08      59 1733.26
   105.8  1695.7   133.9 1670.33   149.9 1657.77   165.9  1639.9   173.9 1636.03
   181.9  1629.9   189.9 1626.49   213.9 1626.19   241.9 1626.31   262.5 1629.66
  290.231629.647   309.9 1628.82   325.9 1626.18   345.9 1627.18   369.9 1631.27
   385.9 1635.27  391.231638.228   401.9 1641.88   417.9 1653.36   458.6 1676.02
  492.661691.737   544.7 1714.94   574.7 1731.71   593.7 1737.29   609.3 1746.83
#Mann= 6 ,-1 , 0
       0      .1       0   181.9    .045       0   262.5      .1       0
  290.23    .055       0  391.23     .06       0  492.66      .1       0
Bank Sta=181.9,262.5
XS Rating Curve= 0 ,0
Exp/Cntr(USF)=0,0
Exp/Cntr=0.3,0.1

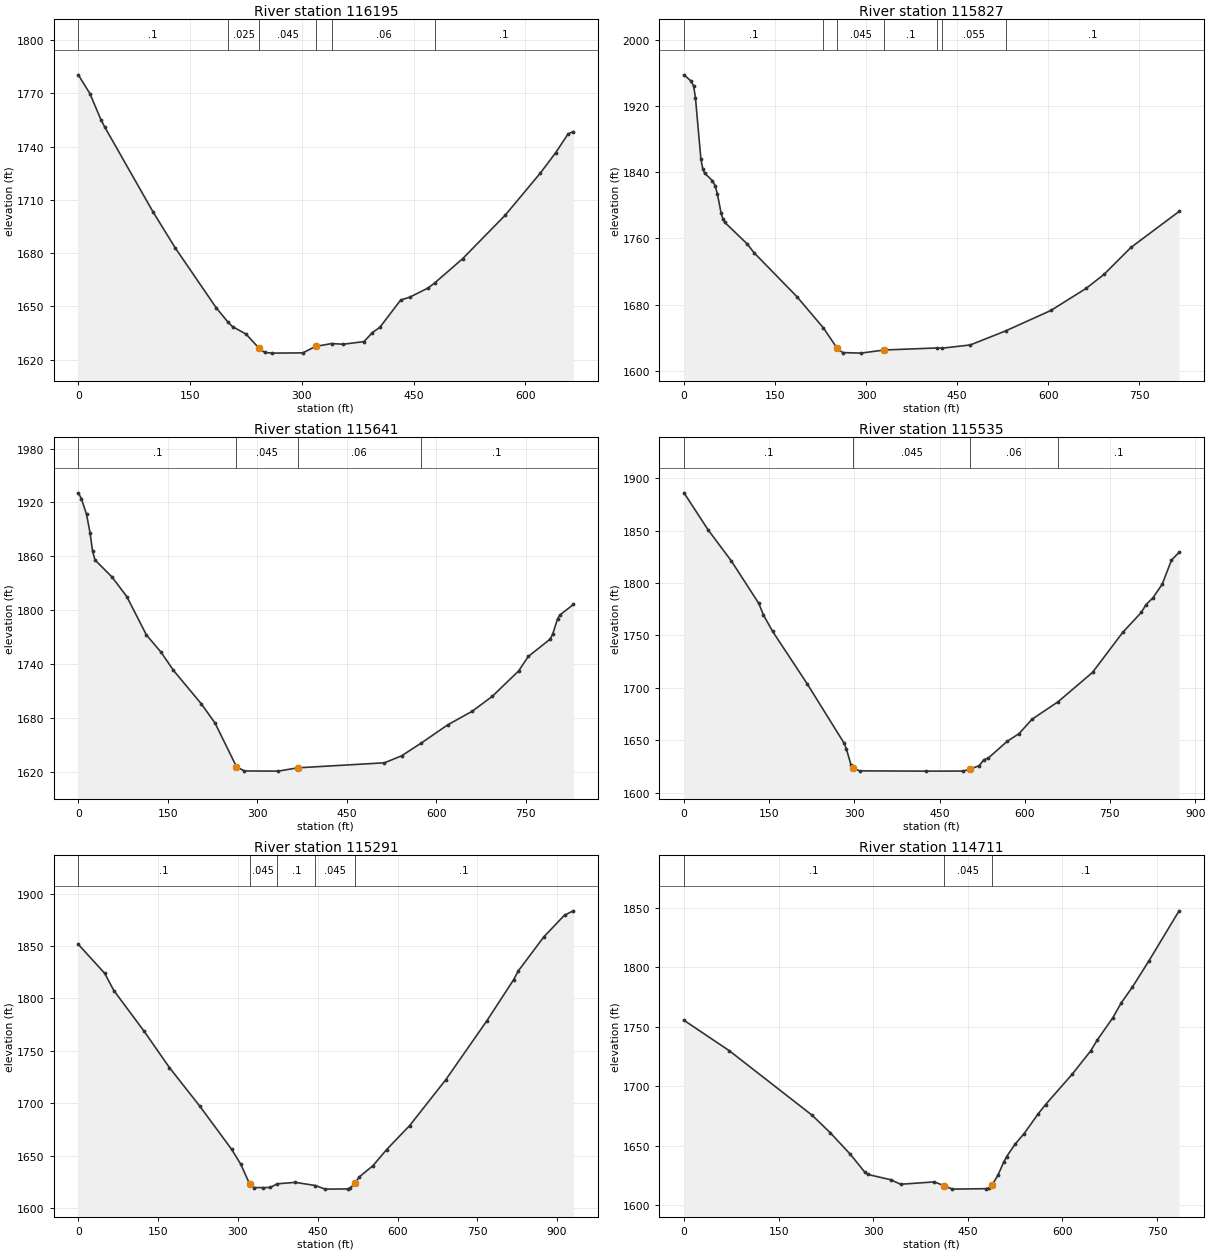
Type RM Length L Ch R = 1 ,116195  ,379.4,368.1,337.8
XS GIS Cut Line= 4
  2446713.213322611343.1662476172446794.82708612611234.347895463
2446997.62492422610962.3020150772447089.13126581610796.601342478
#Sta/Elev= 30
       0 1780.51    15.6 1769.91    30.3 1755.31    35.6    1751   100.3 1703.26
   130.3 1682.85   185.2 1649.15  200.931641.121     207 1638.59   225.1  1634.4
     243 1626.25   250.1 1624.06   260.1 1623.64   301.4 1623.79   318.5 1627.43
  340.161629.025   355.7 1628.66   383.5 1630.14   394.8 1635.23   404.8 1638.18
   432.8 1653.61   444.7 1655.14   469.6 1660.37  478.931663.382   515.8 1676.83
   572.9 1701.32     620 1725.02   640.6 1736.49   657.4 1747.16   664.6 1748.54
#Mann= 6 ,-1 , 0
       0      .1       0  200.93    .025       0     243    .045       0
   318.5      .1       0  340.16     .06       0  478.93      .1       0
Bank Sta=243,318.5
XS Rating Curve= 0 ,0
Exp/Cntr(USF)=0,0
Exp/Cntr=0.3,0.1

Type RM Length L Ch R = 1 ,115827  ,192.9,186.1,150.5
XS GIS Cut Line= 4
 2447052.0341003611605.3195505342447131.17472005611437.145733569
2447279.56338208611056.2815010282447329.02626942610841.117941086
#Sta/Elev= 30
       0 1957.59    11.5  1950.2    15.9 1944.17    18.9 1929.95    27.9 1855.82
    30.9 1844.36    33.9 1838.91    46.9 1829.72    51.3 1823.72      55 1813.89
      61 1791.25      64 1783.89      67 1779.57   104.4 1753.18   115.1    1743
   185.9 1689.77  229.711651.871  252.041627.577   261.3 1622.16   291.3 1621.49
   329.9 1625.29  417.031627.755  425.411627.471   471.6 1631.38  529.781648.347
   604.3 1673.03   662.4 1699.73   691.9 1716.65   736.1  1749.1   815.4  1792.6
#Mann= 7 ,-1 , 0
       0      .1       0  229.71    .025       0  252.04    .045       0
   329.9      .1       0  417.03     .06       0  425.41    .055       0
  529.78      .1       0
Bank Sta=252.04,329.9
XS Rating Curve= 0 ,0
Exp/Cntr(USF)=0,0
Exp/Cntr=0.5,0.3

Type RM Length L Ch R = 1 ,115641  ,93.8,105.4,86.4
XS GIS Cut Line= 4
2447275.57362255611694.0297180272447334.89159235611441.928346362
2447375.67269659 611177.469064322447437.46224847610880.879215301
#Sta/Elev= 30
       0 1930.62     5.2 1924.13    13.8 1906.67    19.7 1885.98    23.8 1866.15
    27.9  1855.9    56.6 1836.74    81.3 1814.94   114.2 1772.17   138.8  1752.9
   159.4  1732.8     206 1695.59   229.2 1673.96     265 1625.42   278.2 1620.71
   334.9  1620.5   367.3 1624.16     513 1629.79   541.5  1637.5   574.1 1651.57
   619.1 1672.14     660 1687.23   693.7 1703.91   737.6 1732.06   753.9 1748.27
   790.7 1767.67   794.8 1773.25     803 1790.35     807 1794.58   829.5 1806.21
#Mann= 4 ,-1 , 0
       0      .1       0     265    .045       0   367.3     .06       0
   574.1      .1       0
Bank Sta=265,367.3
XS Rating Curve= 0 ,0
Exp/Cntr(USF)=0,0
Exp/Cntr=0.5,0.3

Type RM Length L Ch R = 1 ,115535  ,190,243.9,245.5
BEGIN DESCRIPTION:
Inline. Added xs at top of the inline. C/E coefficients not changed for this xs
END DESCRIPTION:
XS GIS Cut Line= 4
2447377.84802689611732.6532021052447423.62229188611478.485572785
2447464.57821319611152.0427882092447523.60292332610873.783440471
#Sta/Elev= 30
       0 1885.95    42.4 1850.72    83.1 1821.22   131.8 1780.46     140 1769.37
   156.2 1753.71   217.2 1703.61     282 1647.16   286.1 1641.42   294.1 1626.44
   298.2 1623.11   309.5 1620.79   425.5 1620.54   491.7 1620.61   503.1 1622.32
   519.9  1625.8   527.9 1631.37     536 1633.11   568.7  1648.8   590.1 1656.39
     613 1670.11  658.871686.775   719.3 1714.68   772.4  1752.8   805.2 1771.92
   813.3 1779.22   825.6 1785.77     842 1798.79   858.3 1821.78   871.7 1829.16
#Mann= 4 ,-1 , 0
       0      .1       0   298.2    .045       0   503.1     .06       0
  658.87      .1       0
Bank Sta=298.2,503.1
XS Rating Curve= 0 ,0
Exp/Cntr(USF)=0,0
Exp/Cntr=0.3,0.1

Type RM Length L Ch R = 1 ,115291  ,475,580.1,614.7
BEGIN DESCRIPTION:
Mannings N in channel placed 0.1 because of island in the channel
END DESCRIPTION:
XS GIS Cut Line= 4
2447494.72694202 611756.181356932447583.76013923611550.910374457
2447717.30993506611204.6701630572447848.38658652610895.527117164
#Sta/Elev= 30
       0 1851.61    49.7 1823.92    66.8 1807.54   123.5  1768.9   171.4 1734.01
   228.1  1697.5   288.1 1656.22   305.2 1642.08  322.051623.103   330.9 1619.67
   348.1 1619.64     361 1619.81   373.8 1623.27   408.1 1624.66   445.7 1621.62
   463.9  1618.2   506.7 1618.41     511 1619.14   519.6 1623.78   528.2 1629.86
   553.9 1640.59   579.6 1655.95   622.9 1678.84   690.8 1722.57   768.2 1778.93
   818.4    1818   827.1 1826.32   874.8  1858.6   913.9 1879.47   930.6 1883.55
#Mann= 5 ,-1 , 0
       0      .1       0  322.05    .045       0   373.8      .1       0
   445.7    .045       0   519.6      .1       0
Bank Sta=322.05,519.6
XS Rating Curve= 0 ,0
Exp/Cntr(USF)=0,0
Exp/Cntr=0.5,0.3

Type RM Length L Ch R = 1 ,114711  ,315.8,367.3,397.8
XS GIS Cut Line= 4
 2447751.9339562611882.311719655 2447925.0540619611761.127645665
2448219.35824159611595.4269730662448434.52180153611498.974342747
#Sta/Elev= 30
       0 1755.44    71.8 1729.89   203.6 1675.45   232.2 1660.75   263.8 1642.81
   286.7 1627.76   291.3  1625.9     328 1621.42   343.4 1617.65   396.9 1619.63
   411.6 1616.54   425.7 1613.55   479.5 1613.94   484.1 1614.71   488.7 1617.19
   497.9 1625.46     507 1636.35   511.6 1640.96     525 1651.42   539.2  1660.2
   561.5 1676.79   573.2 1684.61   615.6 1710.21   644.8 1729.74   654.9 1738.65
   679.9 1757.59     693 1769.91   710.6 1783.15   736.7 1805.05   784.9 1847.42
#Mann= 3 ,-1 , 0
       0      .1       0   411.6    .045       0   488.7      .1       0
Bank Sta=411.6,488.7
XS Rating Curve= 0 ,0
Exp/Cntr(USF)=0,0
Exp/Cntr=0.3,0.1

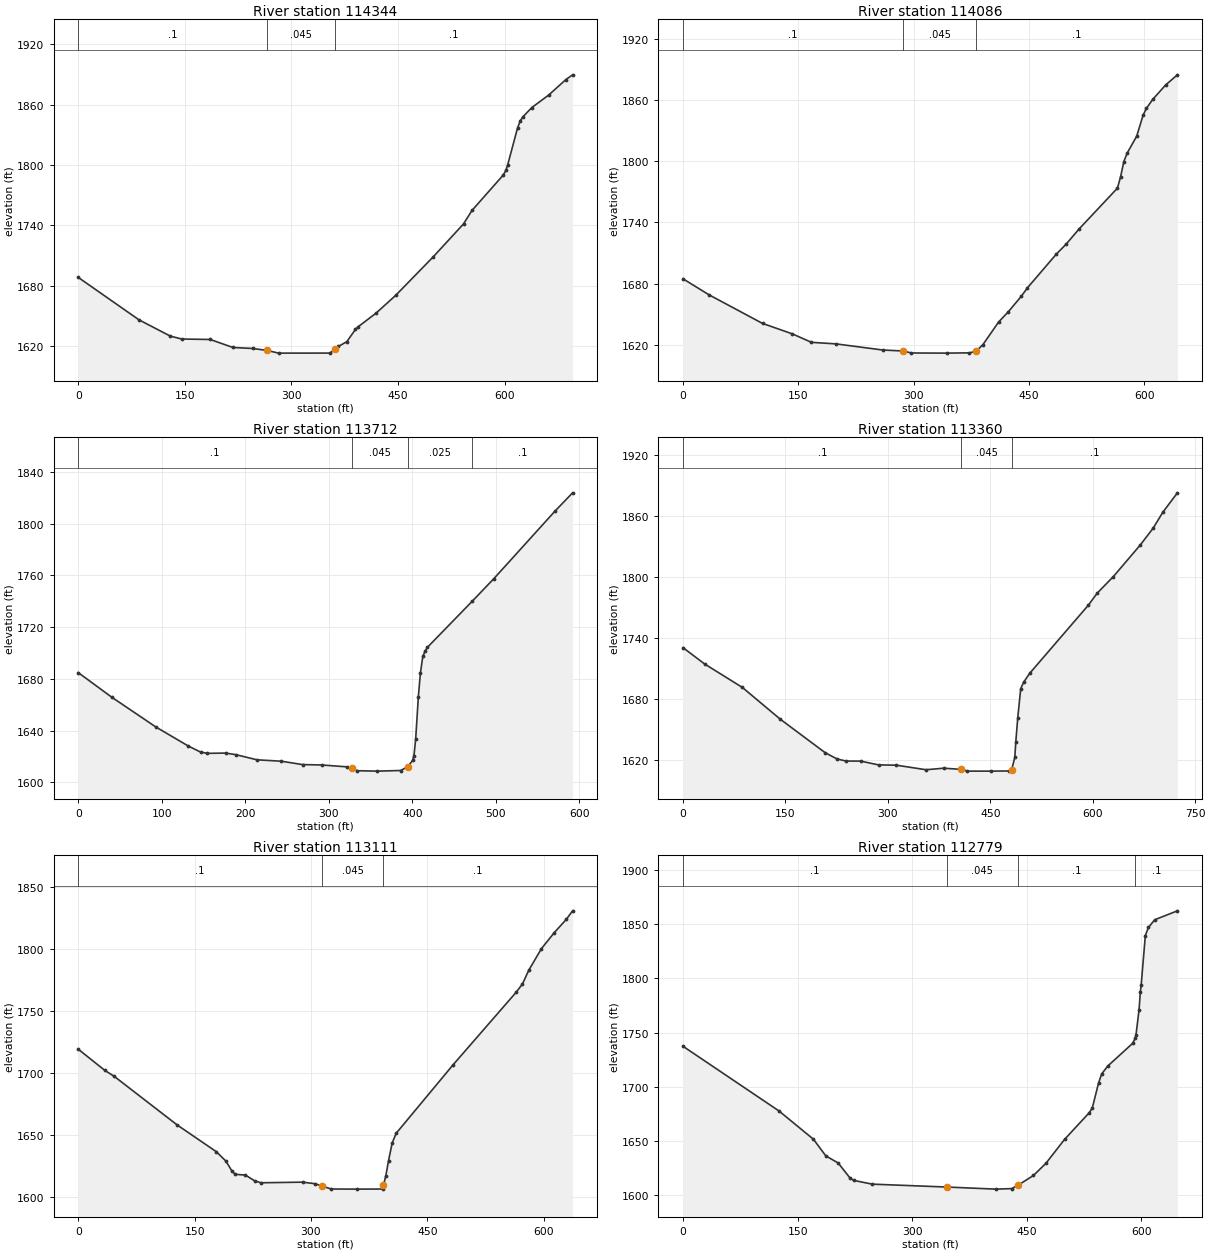
Type RM Length L Ch R = 1 ,114344  ,212.2,258.2,283.4
XS GIS Cut Line= 4
2447905.26890696612020.8078042152447964.62437178612020.807804215
2448343.01545995611998.5495049112448600.22247413611996.076360544
#Sta/Elev= 30
       0 1688.29    85.5 1646.13   129.6 1629.98   145.6  1627.1   185.7 1626.64
   217.7  1618.7   245.8 1617.69   265.8 1615.76   281.9 1613.09     354 1613.14
   361.8 1617.07     366 1619.71     378  1624.5     390 1636.61   394.1 1639.41
   418.9 1652.71   446.6  1670.4   499.1 1708.43   542.1 1741.41   554.1 1754.84
   598.1 1789.99   602.1 1795.08   604.1 1799.63   618.1 1836.57   622.1 1844.03
   626.1  1848.1   638.1  1856.9   662.1 1869.48   686.1 1884.76   695.6 1889.49
#Mann= 3 ,-1 , 0
       0      .1       0   265.8    .045       0   361.8      .1       0
Bank Sta=265.8,361.8
XS Rating Curve= 0 ,0
Exp/Cntr(USF)=0,0
Exp/Cntr=0.3,0.1

Type RM Length L Ch R = 1 ,114086  ,286.5,373.9,399.8
XS GIS Cut Line= 4
2447865.69859709612166.7233218772447949.78550557612186.508476814
2448300.97200571612297.7999733352448481.51154451612352.209149413
#Sta/Elev= 30
       0 1684.74    33.9 1669.05   103.4  1641.1   141.9 1630.97   167.1 1622.59
     199 1621.08   259.8 1615.08   286.3 1614.12   297.2 1612.17   343.3 1612.03
   372.7 1612.31   381.1 1613.83   390.2 1620.32   410.5 1642.38   423.1 1652.39
   439.9 1667.48   448.2 1676.01   485.9 1709.11   498.4 1718.62   515.1 1733.38
   565.3 1773.58   569.4 1784.81   573.6 1799.56   577.8 1807.69   590.3 1824.39
   598.7 1845.07   602.9 1851.55   611.2 1860.43   627.9 1874.48   643.3 1884.48
#Mann= 3 ,-1 , 0
       0      .1       0   286.3    .045       0   381.1      .1       0
Bank Sta=286.3,381.1
XS Rating Curve= 0 ,0
Exp/Cntr(USF)=0,0
Exp/Cntr=0.3,0.1

Type RM Length L Ch R = 1 ,113712  ,298.5,352.4,367.7
XS GIS Cut Line= 4
 2447751.9339562612315.1119839062447826.12828721612386.833170553
2448048.71128026612639.093896002 2448083.3353014 612787.48255803
#Sta/Elev= 30
       0 1684.89      40 1665.93    92.9  1642.9     132 1628.09   146.4 1623.55
   154.7 1622.51   176.7 1622.72   188.8 1621.49   214.2 1617.51   243.2 1616.44
   268.6 1613.83   291.5 1613.52   321.9 1612.09   327.6 1611.13   333.9  1609.1
     358 1608.78     386 1609.26   394.3 1612.03   400.4 1617.01     402  1620.4
   404.1  1633.8   407.3 1666.27   409.7 1684.21   412.6 1697.35   415.4 1701.58
   418.2 1704.46  471.711739.957   497.8 1757.53   570.8 1809.54     592 1823.77
#Mann= 4 ,-1 , 0
       0      .1       0   327.6    .045       0   394.3    .025       0
  471.71      .1       0
Bank Sta=327.6,394.3
XS Rating Curve= 0 ,0
Exp/Cntr(USF)=0,0
Exp/Cntr=0.3,0.1

Type RM Length L Ch R = 1 ,113360  ,228.8,248.9,256.1
XS GIS Cut Line= 4
2447526.87781879612391.7794592872447603.54529417612522.856110746
 2447751.9339562612876.5157552482447821.18199848613052.109005315
#Sta/Elev= 30
       0 1730.29    31.4 1714.32    86.9 1691.11   142.5 1659.77   208.3 1626.76
   225.6 1620.65   238.6 1618.62   260.3 1618.55   286.4 1614.79   312.4 1614.54
   355.8 1610.06   381.8 1611.56   407.8 1610.39   416.5 1608.69   451.2 1608.68
   477.2 1608.85   481.3 1610.03   485.9 1622.18   487.4 1637.75   490.2 1660.94
   494.6 1690.01   498.9 1696.31   507.6 1704.94   593.8  1772.3   606.7 1784.11
   630.3 1800.38   669.5 1831.32   688.4  1847.9   702.8 1863.78   724.1 1882.87
#Mann= 3 ,-1 , 0
       0      .1       0   407.8    .045       0   481.3      .1       0
Bank Sta=407.8,481.3
XS Rating Curve= 0 ,0
Exp/Cntr(USF)=0,0
Exp/Cntr=0.3,0.1

Type RM Length L Ch R = 1 ,113111  ,321.5,331.3,338.9
XS GIS Cut Line= 4
2447376.01601239 612510.49038891 2447427.9520441612658.879050939
2447504.61951949612963.0758080982447536.77039626613126.303336329
#Sta/Elev= 30
       0 1719.12    34.3    1702    46.4  1697.2   127.6 1657.95   177.9 1636.45
   190.2 1628.92   198.5 1620.43   202.6 1618.13   215.5 1617.55   227.4 1612.87
   235.6 1611.33   289.2 1611.82   305.7 1610.53     314 1608.67   326.4  1606.3
   359.4  1606.2   392.4 1606.29   393.4 1609.26   396.5 1616.87     400 1629.11
   404.7 1643.42   409.9 1651.29   483.2  1706.5   564.7 1765.19   572.7 1771.78
   580.8 1782.83   597.1 1800.24   613.4 1812.97   629.3    1824   637.3 1830.79
#Mann= 3 ,-1 , 0
       0      .1       0     314    .045       0   393.4      .1       0
Bank Sta=314,393.4
XS Rating Curve= 0 ,0
Exp/Cntr(USF)=0,0
Exp/Cntr=0.3,0.1

Type RM Length L Ch R = 1 ,112779  ,432.8,437.6,437.5
XS GIS Cut Line= 4
 2447074.2923996612520.3829663792447111.38956511612686.083638977
2447175.69131866613064.4747271512447195.47647359613155.981068735
#Sta/Elev= 30
       0 1737.42   125.5 1677.87   170.6 1651.83   186.9 1636.44   203.1 1629.86
   218.5  1616.1   223.4 1613.83   247.7 1610.39   345.1 1607.73   409.2  1605.8
   430.3 1606.27   438.4 1609.31   458.7  1618.4   474.9 1629.46   499.4  1651.6
   531.7 1676.16   535.8 1680.65   543.9 1703.43     548 1711.91   556.1 1719.31
   588.5  1740.1  591.951744.823   592.9 1747.53     597 1771.15   598.6 1787.03
   599.8 1794.15   605.2 1839.52   609.3 1847.01   617.5 1854.05   647.2 1862.29
#Mann= 4 ,-1 , 0
       0      .1       0   345.1    .045       0   438.4      .1       0
  591.95      .1       0
Bank Sta=345.1,438.4
XS Rating Curve= 0 ,0
Exp/Cntr(USF)=0,0
Exp/Cntr=0.3,0.1

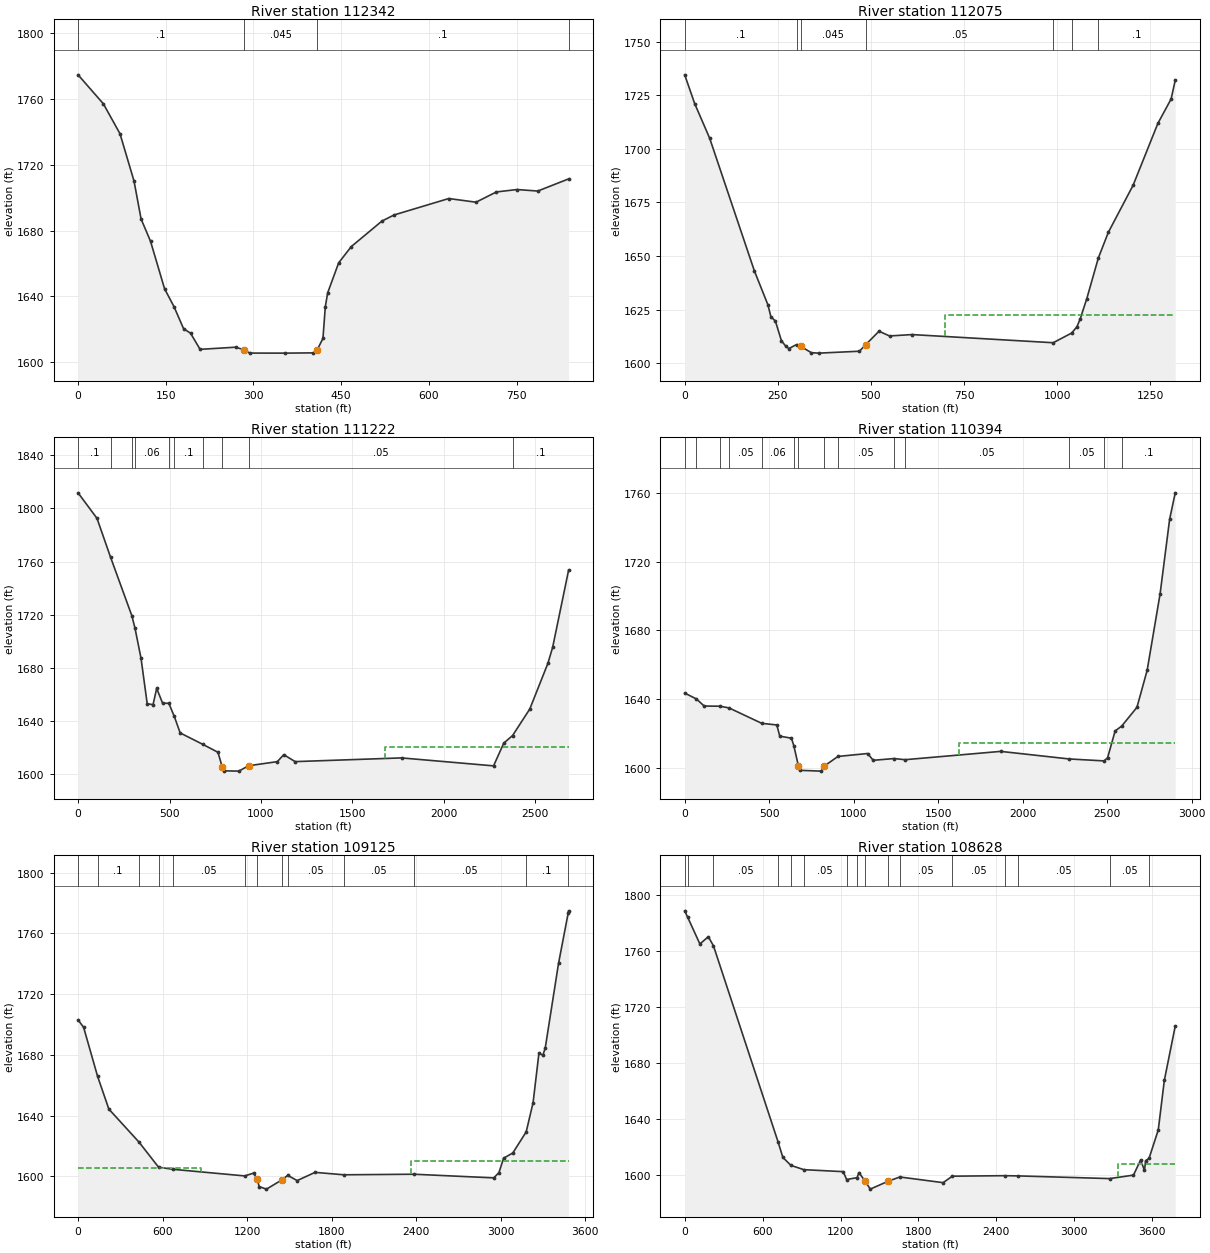
Type RM Length L Ch R = 1 ,112342  ,262.8,266.4,263.4
XS GIS Cut Line= 4
2446671.16986776612599.5235861272446683.53558959612738.019670688
2446732.99847694 613074.367304622446950.63518124613361.252051208
#Sta/Elev= 30
       0 1774.55    43.3 1756.95    71.7  1738.8    95.7 1710.09   107.8 1687.02
   123.9 1673.55     148 1644.62   164.2 1633.73   180.4 1620.48   192.5 1617.64
   208.7 1607.89   269.3 1609.18   283.6 1607.67   293.6 1605.62   354.1 1605.59
   402.7 1605.75  409.08  1607.6   418.9 1614.55   422.9 1633.73     427 1642.23
   445.8 1660.44   467.4 1670.29   519.8 1685.77   540.6 1689.48   634.1 1699.45
   680.7 1697.22   715.6 1703.45   750.8 1704.91   786.3 1703.99   839.1 1711.37
#Mann= 4 ,-1 , 0
       0      .1       0   283.6    .045       0  409.08      .1       0
   839.1      .1       0
Bank Sta=283.6,409.08
XS Rating Curve= 0 ,0
Exp/Cntr(USF)=0,0
Exp/Cntr=0.3,0.1

Type RM Length L Ch R = 1 ,112075  ,844.7,853.1,369.1
XS GIS Cut Line= 4
2446426.04992371612523.9972247812446420.55404734612697.117330482
2446483.75662561613205.4858948392447052.69434427613479.483971452
#Sta/Elev= 30
       01734.487  26.9071721.023  66.9271704.957 187.0871643.005 223.3641627.218
 231.4261621.638 243.5181619.608 259.6411610.451 271.7341607.781 279.7951606.781
  300.321608.667     3121607.758 340.2571604.831 360.4111604.653 469.2431605.544
   485.7 1608.54 521.6431614.875 549.8581612.663  610.32 1613.31  989.341609.503
 1038.541613.9931052.8621616.8751061.7411620.595  1079.51630.057 1110.471649.017
1137.2161660.9641203.8121682.9591270.4071711.8511305.925 1723.241316.9681731.962
#Mann= 7 ,-1 , 0
       0      .1       0  300.32    .025       0     312    .045       0
   485.7     .05       0  989.34      .1       0 1038.54     .05       0
 1110.47      .1       0
#XS Ineff= 2 , 0
                          698.66         1622.28
Permanent Ineff=
       F       F
Bank Sta=312,485.7
XS Rating Curve= 0 ,0
Exp/Cntr(USF)=0,0
Exp/Cntr=0.3,0.1

Type RM Length L Ch R = 1 ,111222  ,874.6,828.4,322.1
XS GIS Cut Line= 4
2445094.43300097612189.5944641312445580.02890785612735.889859375
 2445748.1197987613109.4251723622447179.94802942613680.397251063
#Sta/Elev= 30
       01811.733 103.4191792.554  177.731763.243  293.771719.384  311.151709.956
 344.251 1687.24  377.971653.094 409.8841652.345  429.881664.636 461.9911653.512
  496.391653.372  525.841643.609 558.3241631.083  681.621622.529 764.9141616.529
     788 1605.59 800.0051602.581 878.9591602.359   931.91606.3911089.5031609.503
1124.5941614.7371186.7821609.5171768.6441612.3032271.6111606.3172327.5931623.462
 2375.62 1629.142469.7011649.0872568.7471683.4592594.5841695.4192682.0061753.628
#Mann= 10 ,-1 , 0
       0      .1       0  177.73     .12       0  293.77      .1       0
  311.15     .06       0  496.39      .1       0  525.84      .1       0
  681.62     .06       0     788    .045       0   931.9     .05       0
 2375.62      .1       0
#XS Ineff= 2 , 0
                         1675.62          1620.5
Permanent Ineff=
       F       F
Bank Sta=788,931.9
XS Rating Curve= 0 ,0
Exp/Cntr(USF)=0,0
Exp/Cntr=0.3,0.1

Type RM Length L Ch R = 1 ,110394  ,1215.3,1269,832.5
XS GIS Cut Line= 4
2444423.37468814613100.6177718872444934.34627579613301.655773585
2445439.19063263613511.9139904282447231.61200729613740.894497564
#Sta/Elev= 30
       01643.604   69.151640.207 115.4611636.062  209.911635.969  262.421634.969
   455.71626.027 545.2281625.063 562.5291618.566 631.8581617.366  645.721613.022
  672.531601.466 683.8541598.681 809.5131598.227   822.61600.949  907.121606.768
1082.6171608.465 1115.69 1604.52 1239.351605.538 1304.061604.8711869.7691609.704
 2275.131605.307 2482.28 1604.172502.8721606.065 2547.231621.579 2585.861624.393
 2676.271635.2972736.7581656.8532813.3751701.3192869.831 1744.712902.9651760.023
#Mann= 14 ,-1 , 0
       0      .1       0   69.15     .05       0  209.91      .1       0
  262.42     .05       0   455.7     .06       0  645.72      .1       0
  672.53    .045       0   822.6    .025       0  907.12     .05       0
 1239.35      .1       0 1304.06     .05       0 2275.13     .05       0
 2482.28     .05       0 2585.86      .1       0
#XS Ineff= 2 , 0
                          1623.8         1614.41
Permanent Ineff=
       F       F
Bank Sta=672.53,822.6
XS Rating Curve= 0 ,0
Exp/Cntr(USF)=0,0
Exp/Cntr=0.3,0.1

Type RM Length L Ch R = 1 ,109125  ,462.1,496.7,419.5
XS GIS Cut Line= 4
2444172.07718601 614411.553074632444687.23706537614507.883783777
2445664.65785594614569.7463598872447592.59177274614128.113614969
#Sta/Elev= 30
       01703.103  39.338 1698.19  138.281665.984 218.389 1644.35   431.6 1622.69
  571.241606.084   673.11604.678  1182.41600.3261245.0371602.149 1271.661598.131
1285.1171593.2811337.2211591.625  1444.61597.613 1487.981600.701 1554.85 1597.25
1682.0621602.665 1886.431601.066 2384.051601.4342950.0761599.0362987.0081602.506
3019.8371611.9833085.4951615.475 3180.231629.3173229.121 1648.553270.4711680.981
3298.8821679.9133315.2971684.4913409.6791740.257  3478.81773.7083481.3351774.931
#Mann= 13 ,-1 , 0
       0      .1       0  138.28      .1       0   431.6     .06       0
  571.24     .05       0   673.1     .05       0  1182.4     .05       0
 1271.66    .045       0  1444.6    .025       0 1487.98     .05       0
 1886.43     .05       0 2384.05     .05       0 3180.23      .1       0
  3478.8      .1       0
#XS Ineff= 2 , 0
          868.95 1605.29 2364.68         1609.89
Permanent Ineff=
       F       F
Bank Sta=1271.66,1444.6
XS Rating Curve= 0 ,0
Exp/Cntr(USF)=0,0
Exp/Cntr=0.3,0.1

Type RM Length L Ch R = 1 ,108628  ,709.5,601,245.3
XS GIS Cut Line= 4
2444015.84978472615187.2153508542445187.81682922614967.763354474
2445617.38243915615093.8315226072447629.80393787614374.776045107
#Sta/Elev= 30
       0 1788.35   22.911783.787   116.9 1764.71     182 1769.87   221.61763.361
  718.331623.621   755.8  1612.4  817.671606.703  917.021603.645  1220.4 1602.22
 1246.79 1596.62 1327.611597.937  1341.3 1601.55  1391.3 1595.23  1428.8 1589.75
    1563 1595.25 1656.421598.418  1989.8 1594.36 2060.391598.985 2464.361599.341
 2565.351599.191  3272.31597.271  3455.4 1599.75  3510.4 1610.51  3539.9 1603.13
  3549.2 1610.07 3575.271611.685  3646.3    1632  3693.1 1667.42    3777 1706.09
#Mann= 16 ,-1 , 0
       0      .1       0   22.91      .1       0   221.6     .05       0
  718.33     .06       0  817.67     .05       0  917.02     .05       0
 1246.79    .025       0 1327.61      .1       0  1391.3    .045       0
    1563    .025       0 1656.42     .05       0 2060.39     .05       0
 2464.36     .05       0 2565.35     .05       0  3272.3     .05       0
 3575.27      .1       0
#XS Ineff= 2 , 0
                         3337.78         1607.53
Permanent Ineff=
       F       F
Bank Sta=1391.3,1563
XS Rating Curve= 0 ,0
Exp/Cntr(USF)=0,0
Exp/Cntr=0.5,0.3