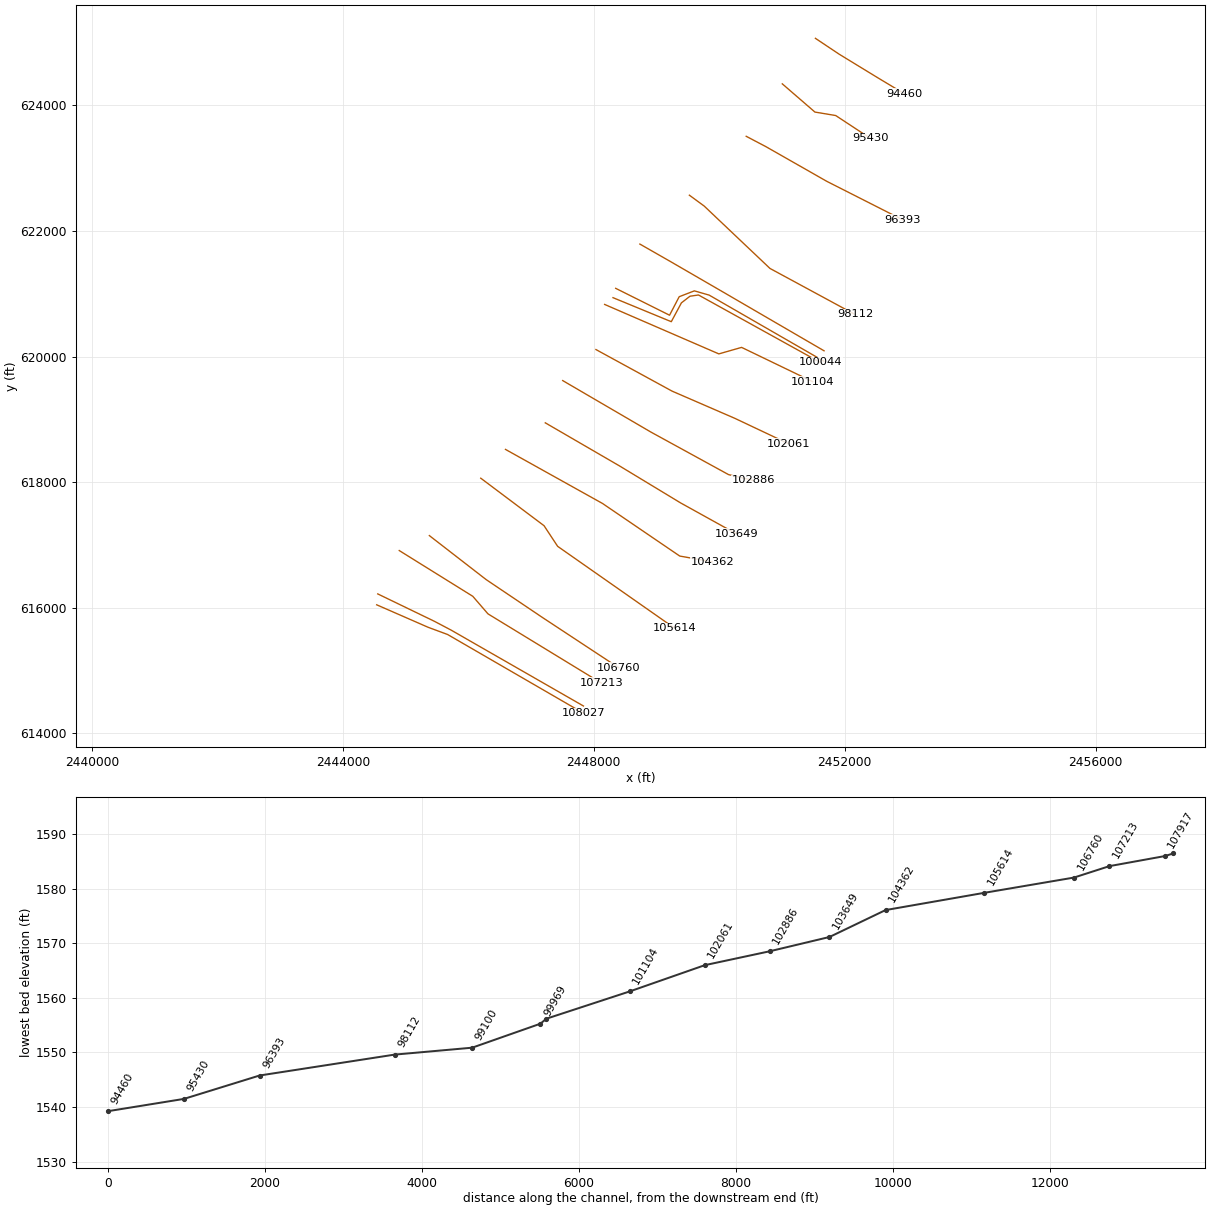
HEC-RAS study SBPOTOMC.prj: SBPOTOMC

--- SBPOTOMC.g01 (geometry) --- (continued)

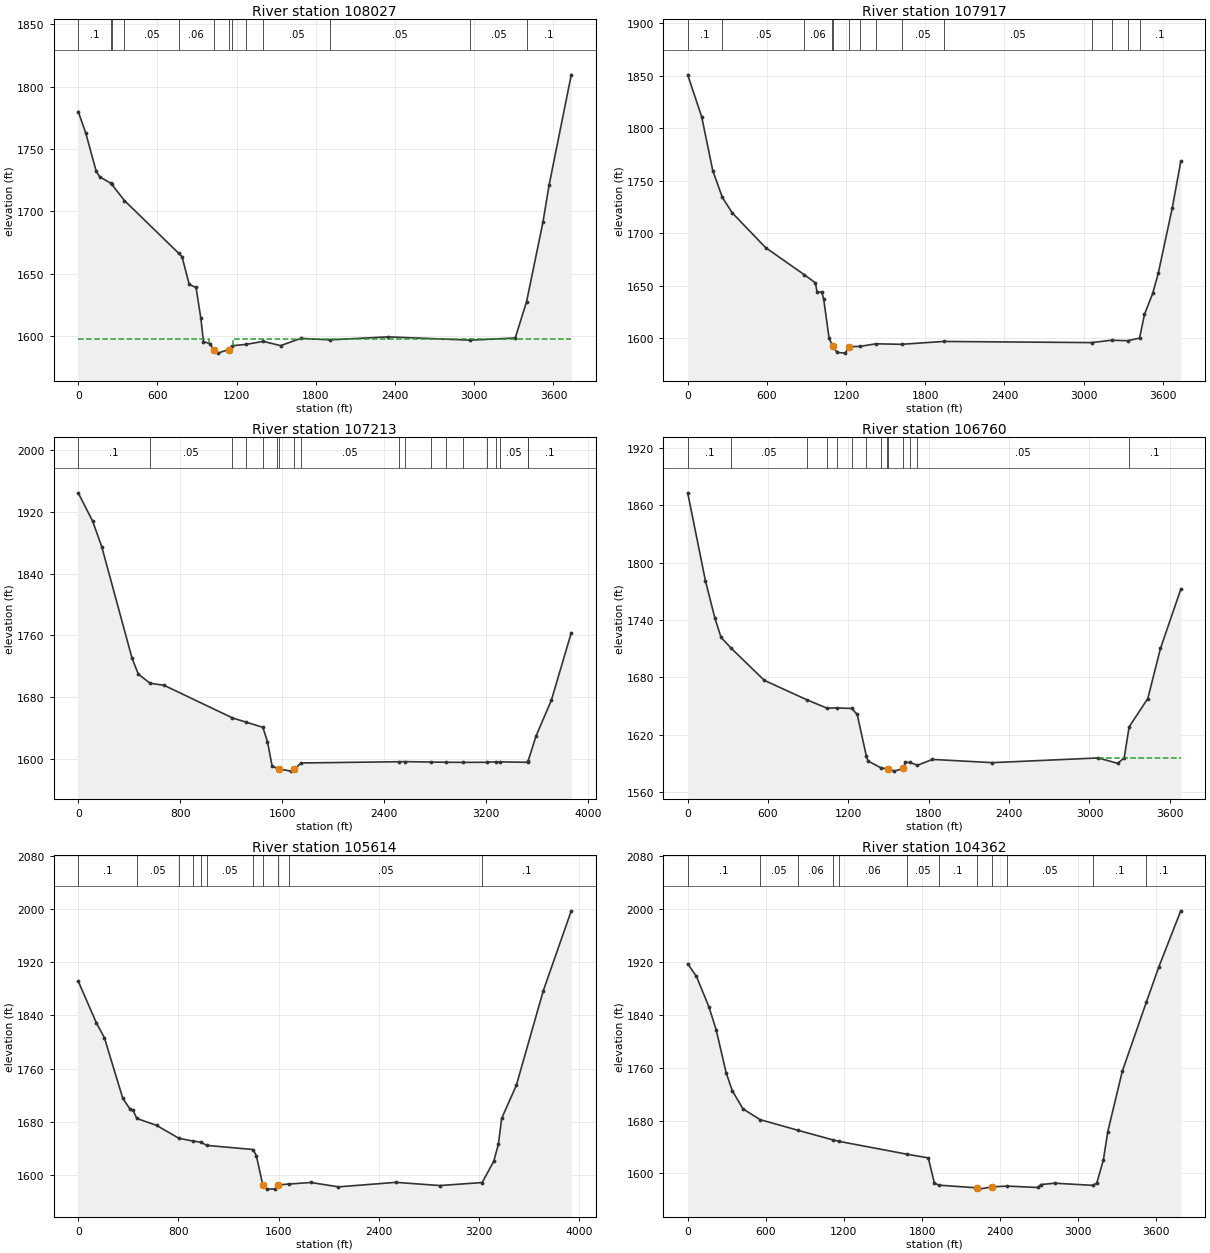
Type RM Length L Ch R = 1 ,108027  ,126.6,110.1,96
XS GIS Cut Line= 4
2444538.55416359616046.1060078482445358.46254833615687.920774922
2445669.07630501  615573.18956752447840.57427963614316.742930125
#Sta/Elev= 30
       0 1780.07      57 1762.97   135.5 1732.55   161.7 1727.89  248.081722.506
  254.761721.679  350.621708.726  760.751666.551   786.4 1663.79     841 1641.49
   892.7 1639.08   929.1 1614.38   948.7 1595.74   998.5 1594.08  1026.5 1588.84
  1057.1 1586.49  1140.1 1589.35 1167.291592.415 1270.621593.484 1401.991595.913
  1532.8  1592.5  1685.4 1598.28 1908.261597.143  2346.1 1599.52 2970.98 1596.89
  3310.2  1598.6 3396.071627.674    3520 1691.28  3566.2 1720.85  3734.7 1809.48
#Mann= 13 ,-1 , 0
       0      .1       0  248.08     .05       0  254.76      .1       0
  350.62     .05       0  760.75     .06       0  1026.5    .045       0
  1140.1     .05       0 1167.29    .055       0 1270.62     .06       0
 1401.99     .05       0 1908.26     .05       0 2970.98     .05       0
 3396.07      .1       0
#XS Ineff= 2 , 0
             993 1597.56    1173         1597.56
Permanent Ineff=
       F       F
Bank Sta=1026.5,1140.1
XS Rating Curve= 0 ,0
Exp/Cntr(USF)=0,0
Exp/Cntr=0.5,0.3

Type RM Length L Ch R = 1 ,107917  ,714.2,704,497.4
XS GIS Cut Line= 4
2444555.34409638616219.6019800472445459.20214509615783.063727418
2445725.04274765615643.1476208062447834.97763536614434.272459679
#Sta/Elev= 30
       0 1850.96   105.9 1811.08   190.3 1759.68  262.391734.376   336.9 1719.64
   590.1  1686.5   884.11660.604   967.6 1652.94   979.6 1644.66  1016.8 1643.76
  1030.4 1637.53    1071 1600.52  1092.31594.334  1098.2 1592.35    1133  1586.7
  1193.1    1586  1224.7 1592.19 1301.821592.365  1426.9 1594.87 1620.091594.406
 1938.39 1597.12 3061.251596.031 3211.591598.297 3333.641597.806 3423.791600.374
  3461.1 1622.92  3523.5 1642.96  3565.3 1661.98  3671.1 1723.92  3735.9 1768.53
#Mann= 14 ,-1 , 0
       0      .1       0  262.39     .05       0   884.1     .06       0
  1092.3      .1       0  1098.2    .045       0  1224.7    .055       0
 1301.82      .1       0  1426.9     .06       0 1620.09     .05       0
 1938.39     .05       0 3061.25     .05       0 3211.59      .1       0
 3333.64     .05       0 3423.79      .1       0
Bank Sta=1098.2,1224.7
XS Rating Curve= 0 ,0
Exp/Cntr(USF)=0,0
Exp/Cntr=0.5,0.3

Type RM Length L Ch R = 1 ,107213  ,410.5,452.7,396.5
XS GIS Cut Line= 4
2444898.32696165616910.1469820082446070.29400615616181.753121683
2446313.09195959615901.6016369422448120.06903617 614799.67246363
#Sta/Elev= 30
       0 1944.88   113.5 1908.06   184.2 1875.31   422.9 1730.19   471.5 1709.94
  563.511698.103     674 1695.37 1209.22  1653.2 1316.84 1647.64 1447.931641.008
  1484.4 1622.42    1521 1590.72  1562.91587.698    1576 1586.79  1671.5 1584.16
  1694.1 1586.82 1749.79 1594.74 2512.351596.339 2560.24 1596.49 2766.721595.956
 2881.971595.665 3021.081595.509  3203.71595.636 3275.451596.232 3310.941596.178
 3525.421595.593 3529.821597.855  3590.2 1629.45  3710.9    1676  3867.1 1763.47
#Mann= 19 ,-1 , 0
       0      .1       0  563.51     .05       0 1209.22     .06       0
 1316.84     .05       0 1447.93      .1       0  1562.9    .025       0
    1576    .045       0  1694.1      .1       0 1749.79     .05       0
 2512.35     .06       0 2560.24     .05       0 2766.72     .06       0
 2881.97     .05       0 3021.08     .06       0  3203.7     .05       0
 3275.45     .06       0 3310.94     .05       0 3525.42      .1       0
 3529.82      .1       0
Bank Sta=1576,1694.1
XS Rating Curve= 0 ,0
Exp/Cntr(USF)=0,0
Exp/Cntr=0.3,0.1

Type RM Length L Ch R = 1 ,106760  ,1183.3,1146.4,1069.9
XS GIS Cut Line= 4
2445378.38764733 617148.342089642446284.70376847616446.932221973
2447175.25787012615847.9754810442448396.81438122615044.112486639
#Sta/Elev= 30
       0 1873.08   132.4 1781.16   203.7 1741.78   249.4 1721.95  322.021710.961
     572    1677  887.231656.837  1040.11647.884 1113.311648.188 1223.711647.601
  1265.7 1641.39 1333.04 1598.38  1346.1 1592.78 1442.371585.476 1485.231584.646
  1495.6 1584.54  1543.8 1582.06 1608.16 1584.84  1625.7 1591.18 1661.041591.177
 1715.211588.196  1827.7 1594.31  2274.5 1590.93  3066.2 1595.85  3210.8 1590.18
  3259.3 1595.99 3296.071628.348  3435.5 1657.96    3530 1710.33  3681.6 1772.18
#Mann= 14 ,-1 , 0
       0      .1       0  322.02     .05       0  887.23     .06       0
  1040.1     .05       0 1113.31    .055       0 1223.71     .05       0
 1333.04      .1       0 1442.37    .025       0 1485.23     .05       0
  1495.6    .045       0 1608.16     .05       0 1661.04    .025       0
 1715.21     .05       0 3296.07      .1       0
#XS Ineff= 2 , 0
                         3065.68         1596.17
Permanent Ineff=
       F       F
Bank Sta=1495.6,1608.16
XS Rating Curve= 0 ,0
Exp/Cntr(USF)=0,0
Exp/Cntr=0.3,0.1

Type RM Length L Ch R = 1 ,105614  ,1141.6,1251.7,988.4
XS GIS Cut Line= 4
2446198.01266123618062.5392205322447206.78190911617305.962284621
2447423.60125047 616977.51351876  2449294.230207615669.531547514
#Sta/Elev= 30
       0 1891.61   145.9 1828.57   208.8 1806.75   355.9 1715.69   414.6 1699.09
   437.4 1697.83  468.221685.334     626 1674.97  804.611655.546  916.741651.429
  976.591649.823 1028.87 1644.89 1397.341638.704  1422.8 1629.26 1473.29 1586.14
  1505.7 1579.25  1571.4 1579.45  1597.91585.591 1681.631586.871  1858.5 1589.22
    2078 1582.66  2536.9 1589.43  2887.6 1584.63 3225.381589.134  3317.8 1620.86
  3355.3 1646.76  3381.3 1685.49  3498.4 1735.09  3713.2 1876.85  3937.1 1997.09
#Mann= 11 ,-1 , 0
       0      .1       0  468.22     .05       0  804.61    .035       0
  916.74     .02       0  976.59    .035       0 1028.87     .05       0
 1397.34      .1       0 1473.29    .045       0  1597.9      .1       0
 1681.63     .05       0 3225.38      .1       0
Bank Sta=1473.29,1597.9
XS Rating Curve= 0 ,0
Exp/Cntr(USF)=0,0
Exp/Cntr=0.3,0.1

Type RM Length L Ch R = 1 ,104362  ,688.1,713.6,702.3
XS GIS Cut Line= 4
2446591.73027023618521.4240351162448140.03085523617659.397222924
2449370.30213089616822.4779877862449889.19205667616730.416871921
#Sta/Elev= 30
       0 1917.37    67.5  1898.1   162.9 1852.18     219 1817.23   295.2 1752.42
   342.3 1725.19   424.6 1697.66  556.061681.304  845.191665.318  1118.91650.421
 1162.051648.439 1681.751629.076  1847.9 1623.38  1893.9 1585.88  1926.51582.141
  2220.7 1578.09  2235.1  1576.1  2340.3 1579.59 2454.271580.706    2690 1578.57
  2711.7 1583.02  2819.6 1585.06 3111.861581.813    3142 1585.27  3192.9 1620.61
  3226.7 1663.29  3337.7 1754.45 3523.06 1859.38    3618 1912.32    3787 1997.47
#Mann= 12 ,-1 , 0
       0      .1       0  556.06     .05       0  845.19     .06       0
  1118.9     .05       0 1162.05     .06       0 1681.75     .05       0
  1926.5      .1       0  2220.7    .045       0  2340.3      .1       0
 2454.27     .05       0 3111.86      .1       0 3523.06      .1       0
Bank Sta=2220.7,2340.3
XS Rating Curve= 0 ,0
Exp/Cntr(USF)=0,0
Exp/Cntr=0.3,0.1

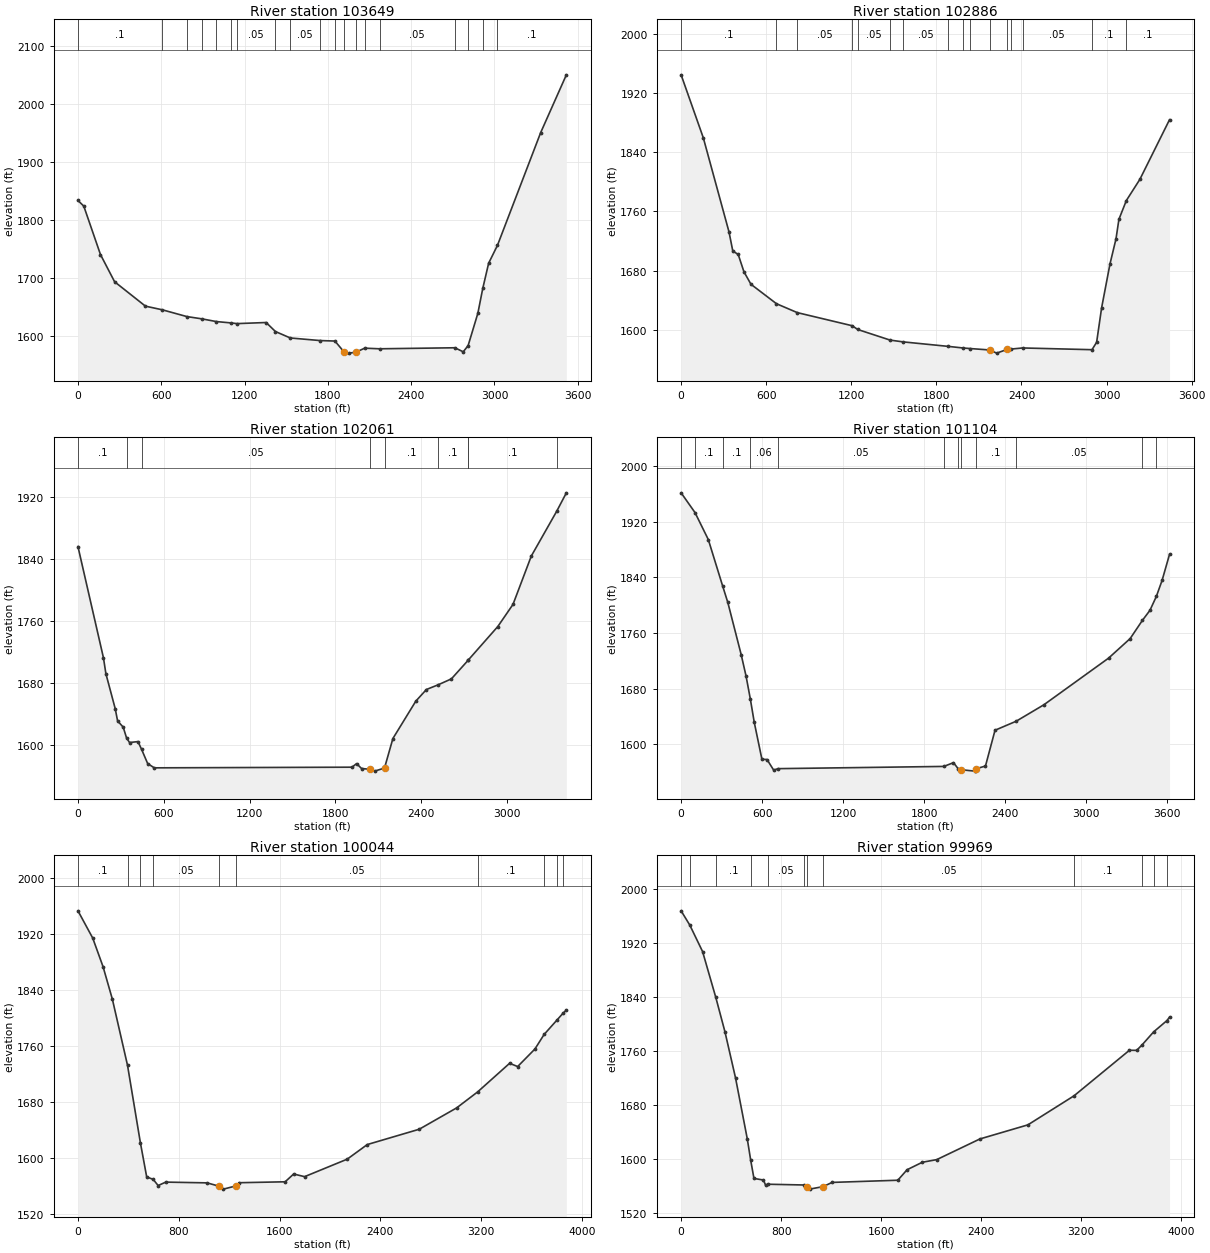
Type RM Length L Ch R = 1 ,103649  ,758.2,763,766.9
XS GIS Cut Line= 4
2447226.44938943618944.6540417132448408.60085179618259.006193544
2449385.84606067617667.9304623642450268.51915257617179.307857922
#Sta/Elev= 30
       01834.053  41.9591824.293 162.1861740.885 263.9161694.056 485.8731652.078
  607.971645.734  784.121634.119  890.441630.267  996.751625.509 1103.071623.178
 1145.341621.9841355.2061623.889 1422.41 1608.34 1529.491597.256 1743.661592.812
 1850.741591.9691918.7851572.5451948.7751571.1662000.5941572.589 2064.911579.705
    21721578.628 2714.351580.4012774.8961573.434 2810.061584.1812880.0521639.666
 2915.591682.6552957.7761725.983 3021.121756.6413332.6791950.9613517.5862050.394
#Mann= 19 ,-1 , 0
       0      .1       0  607.97     .06       0  784.12     .05       0
  890.44    .055       0  996.75     .05       0 1103.07    .055       0
 1145.34     .05       0 1422.41    .055       0 1529.49     .05       0
 1743.66    .025       0 1850.74     .05       01918.785    .045       0
2000.594    .025       0 2064.91      .1       0    2172     .05       0
 2714.35      .1       0 2810.06      .1       0 2915.59      .1       0
 3021.12      .1       0
Bank Sta=1918.785,2000.594
XS Rating Curve= 0 ,0
Exp/Cntr(USF)=0,0
Exp/Cntr=0.3,0.1

Type RM Length L Ch R = 1 ,102886  ,810.6,824.2,821.5
XS GIS Cut Line= 4
2447503.97223653619617.7882331472448909.99655156618797.607382712
2450148.63701956 618119.702802252450541.98906008618027.641686385
#Sta/Elev= 30
       0 1944.29   156.6 1859.21   337.6 1732.29   364.4  1706.5   402.7 1701.71
   443.1 1678.35   492.6  1661.5  672.62 1635.23  819.611623.209 1206.581605.516
 1245.281600.458 1473.561586.138 1564.52 1583.74  1881.21577.701 1986.551575.512
 2036.091574.751  2175.8 1572.81    2225 1568.54  2298.9 1573.54 2323.151573.953
 2407.941575.516 2897.261573.172  2929.9 1583.17  2965.3 1629.98  3024.2 1689.05
  3066.6 1722.92  3087.1 1749.23 3139.571774.603    3235 1803.23  3443.8 1883.66
#Mann= 16 ,-1 , 0
       0      .1       0  672.62     .06       0  819.61     .05       0
 1206.58    .055       0 1245.28     .05       0 1473.56    .055       0
 1564.52     .05       0  1881.2    .055       0 1986.55     .05       0
 2036.09    .025       0  2175.8    .045       0  2298.9      .1       0
 2323.15    .025       0 2407.94     .05       0 2897.26      .1       0
 3139.57      .1       0
Bank Sta=2175.8,2298.9
XS Rating Curve= 0 ,0
Exp/Cntr(USF)=0,0
Exp/Cntr=0.3,0.1

Type RM Length L Ch R = 1 ,102061  ,977.9,957.4,1007.6
XS GIS Cut Line= 4
2448034.28793277620111.6017552892449247.96343412619449.596936368
2450248.85167225619016.1414001692451100.00072515618614.209902966
#Sta/Elev= 30
       0  1855.8   178.2 1712.26   195.4 1691.64   260.2 1646.81   277.1 1630.78
   316.3 1622.78  339.781608.797   360.5 1602.93   419.5 1604.11  445.081593.989
   487.3 1575.76   533.6 1570.24  1915.9 1571.09  1947.8  1575.7  1982.8 1569.37
  2043.7 1568.34  2074.2    1566 2143.061569.947  2201.8 1608.11  2361.9  1656.3
    2436 1671.33 2519.821677.552  2610.8 1685.07 2726.531708.821 2729.321709.505
  2935.3 1752.65  3041.5 1781.23  3169.6 1843.69 3346.661901.317  3414.5  1925.2
#Mann= 9 ,-1 , 0
       0      .1       0  339.78     .06       0  445.08     .05       0
  2043.7    .045       0 2143.06      .1       0 2519.82      .1       0
 2726.53     .05       0 2729.32      .1       0 3346.66     .12       0
Bank Sta=2043.7,2143.06
XS Rating Curve= 0 ,0
Exp/Cntr(USF)=0,0
Exp/Cntr=0.3,0.1

Type RM Length L Ch R = 1 ,101104  ,178.6,1060,1115
XS GIS Cut Line= 4
2448173.12945367620830.2022041162449993.76619896620042.526344671
2450356.51166055620146.1679051242451489.65938817619600.322353404
#Sta/Elev= 30
       0 1961.69  102.961933.302   201.5 1894.46  307.841827.582   346.1  1803.9
   444.9 1729.02   481.2 1698.01  512.721665.228   542.1 1631.28   598.8 1578.21
   636.5 1577.91     686 1562.59   717.61564.746 1946.881567.946    2018 1573.39
 2053.99  1564.3  2075.4 1563.17  2176.1 1561.18  2185.4 1564.62  2255.1  1568.5
  2325.9 1620.01 2482.441632.971  2687.6 1656.63  3167.1 1723.77  3327.1 1751.93
 3417.79 1778.12  3473.8 1792.61 3521.381812.663  3563.7 1835.66  3618.7 1873.06
#Mann= 12 ,-1 , 0
       0      .1       0  102.96      .1       0  307.84      .1       0
  512.72     .06       0   717.6     .05       0 1946.88      .1       0
 2053.99      .1       0  2075.4    .045       0  2185.4      .1       0
 2482.44     .05       0 3417.79      .1       0 3521.38      .1       0
Bank Sta=2075.4,2185.4
XS Rating Curve= 0 ,0
Exp/Cntr(USF)=0,0
Exp/Cntr=0.5,0.3

Type RM Length L Ch R = 1 ,100044  ,132.5,75.1,112.1
XS GIS Cut Line= 6
2448306.27776638620938.186345952 2449235.6005465620555.375878262
2449396.78390132620855.0761786252449532.78235694620960.852755223
2449668.78081257620981.0006745752451613.05503005619905.605479156
#Sta/Elev= 30
       0 1953.63   117.3 1914.67   199.5 1873.68     273 1827.53  393.291733.098
  495.291622.691   545.6 1573.64  597.291570.091   636.4 1561.31     697 1566.21
  1024.8 1565.13 1122.57 1560.24  1154.4 1556.18  1258.1 1560.97  1281.1 1565.35
  1644.5 1566.65  1712.2 1577.76  1799.1 1573.99  2137.4 1598.98  2296.8 1619.85
  2708.9  1641.7  3005.9 1672.18 3172.751695.036  3426.4 1735.86  3490.4 1731.24
  3627.5  1756.3 3700.331777.061 3805.841798.324 3849.221807.119    3877 1811.87
#Mann= 10 ,-1 , 0
       0      .1       0  393.29      .1       0  495.29     .06       0
  597.29     .05       0 1122.57    .045       0  1258.1     .05       0
 3172.75      .1       0 3700.33      .1       0 3805.84      .1       0
 3849.22      .1       0
#XS Ineff= 2 , 0
            1095  1560.5    1285          1560.5
Permanent Ineff=
       F       F
Bank Sta=1122.57,1258.1
XS Rating Curve= 0 ,0
Exp/Cntr(USF)=0,0
Exp/Cntr=0.5,0.3

Type RM Length L Ch R = 1 ,99969   ,846.9,869.2,419.3
XS GIS Cut Line= 6
2448349.09209501621086.7772511742449207.89715739620658.633964941
2449361.52504245620953.2972854662449603.30007467 621046.48141247
2449840.03812706620978.4821846562451668.46180827619925.753398508
#Sta/Elev= 30
       0 1967.39   69.651946.211   171.7 1907.11  277.681839.104   350.5 1788.47
   435.4 1719.97   529.1 1630.04  556.711598.085   582.8  1571.1   658.9 1568.72
   676.7 1560.77  693.741562.526  985.741561.394    1005 1558.65  1027.6 1555.27
  1135.8 1558.96    1208 1565.22  1733.6 1568.44  1807.8 1583.98  1929.7 1595.06
    2045 1598.96  2390.7  1629.6  2774.4 1650.44  3143.41693.457  3586.7 1760.91
  3644.5 1760.76 3688.631769.048 3780.51 1788.19  3886.71804.873  3907.2 1809.91
#Mann= 12 ,-1 , 0
       0      .1       0   69.65      .1       0  277.68      .1       0
  556.71     .06       0  693.74     .05       0  985.74    .025       0
    1005    .045       0  1135.8     .05       0  3143.4      .1       0
 3688.63      .1       0 3780.51      .1       0  3886.7     .12       0
Bank Sta=1005,1135.8
XS Rating Curve= 0 ,0
Exp/Cntr(USF)=0,0
Exp/Cntr=0.5,0.3

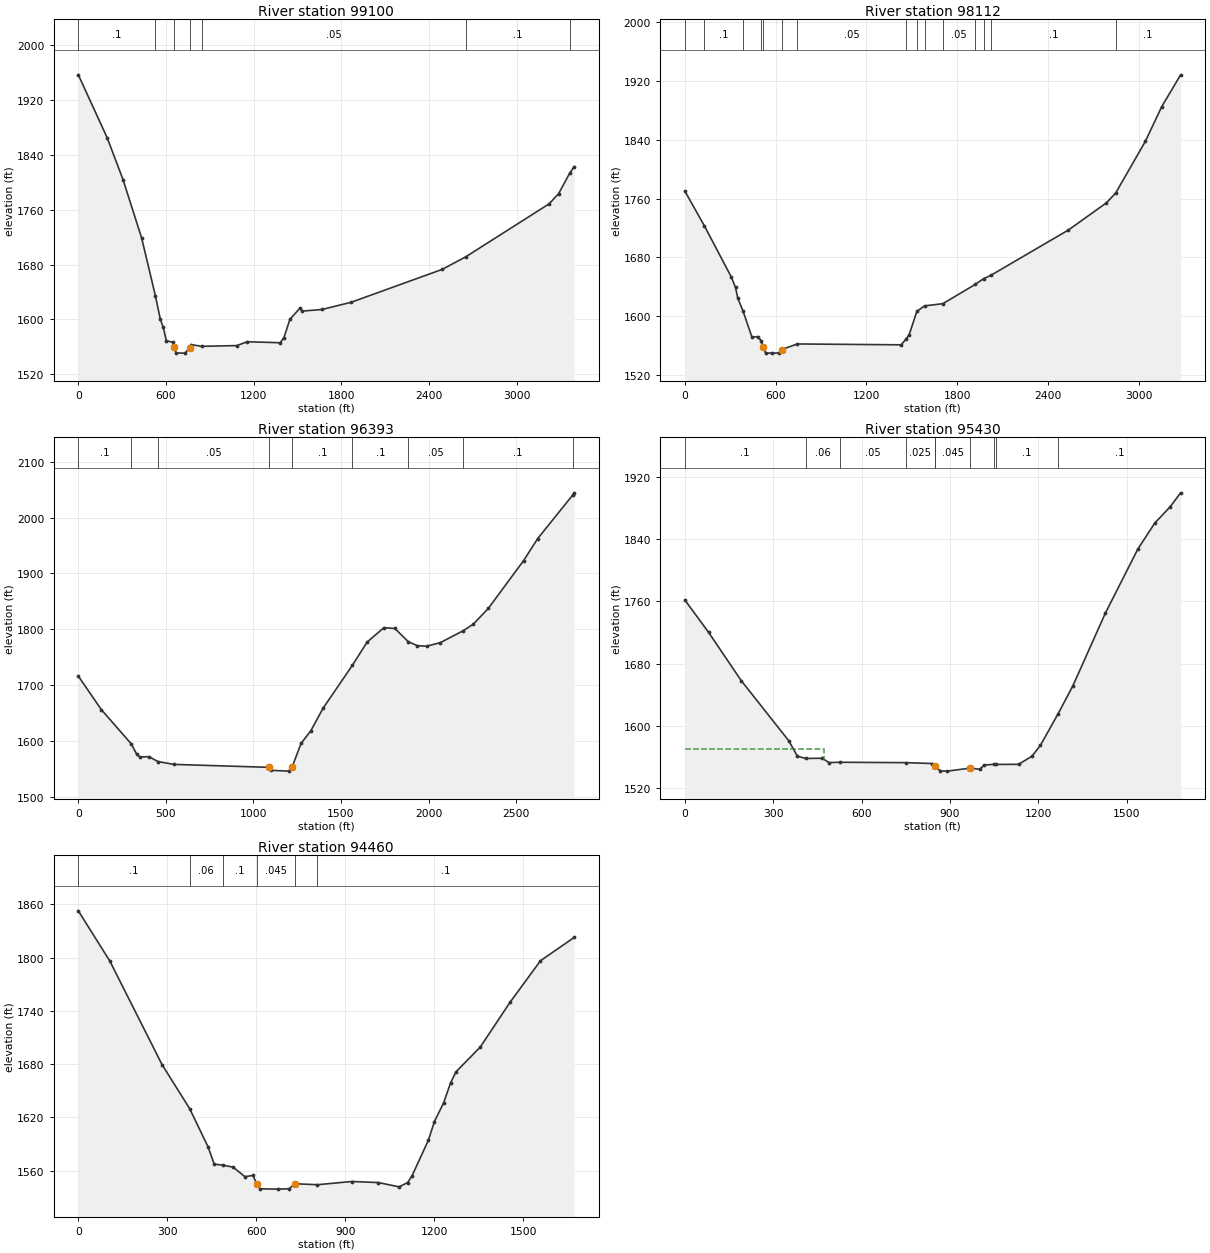
Type RM Length L Ch R = 1 ,99100   ,1003,987.5,916.9
XS GIS Cut Line= 4
2448734.42105261621791.9544284982449215.45262715621517.439027325
2449998.70299196621064.1108419032451670.98029819620091.973733163
#Sta/Elev= 30
       0 1956.81   197.5 1864.93     306 1803.89   433.3 1718.79  527.641634.245
   561.1 1600.26   580.8 1588.66     602 1569.17   645.5 1566.62   654.8 1559.93
   668.6 1551.05   730.8 1550.87     761 1559.05   770.3 1563.22  846.41 1560.81
  1085.1 1561.86  1155.3 1567.51  1381.4 1566.01  1407.1 1573.45    1448 1600.29
    1519 1616.95  1532.9 1612.19  1667.1 1614.51  1866.5 1625.02  2490.6 1673.06
 2653.971691.713  3221.1 1768.54  3286.5 1783.37 3361.321812.896  3393.1 1823.04
#Mann= 7 ,-1 , 0
       0      .1       0  527.64     .06       0   654.8    .045       0
     761      .1       0  846.41     .05       0 2653.97      .1       0
 3361.32      .1       0
Bank Sta=654.8,761
XS Rating Curve= 0 ,0
Exp/Cntr(USF)=0,0
Exp/Cntr=0.3,0.1

Type RM Length L Ch R = 1 ,98112   ,1503.4,1718.6,1604.5
XS GIS Cut Line= 4
2449523.79877534622570.4767969992449760.22906781622397.094582519
2450808.40336444621404.0873541362452163.93704128620671.153447473
#Sta/Elev= 30
       0 1770.33  129.841722.743     308    1653   335.2 1638.99   350.3 1624.47
     3841607.456   443.7 1571.55   483.3 1572.06  504.141566.626   516.2 1557.89
   534.2  1549.8   577.7  1549.6   621.9 1549.81   639.5 1554.51  744.421562.085
  1430.5 1560.91 1465.271569.412  1482.9 1574.28 1534.08 1606.43 1585.41 1613.94
 1705.551616.884  1919.81643.096  1975.11650.897 2024.96  1655.7  2535.5 1717.12
  2787.4 1754.16 2848.611767.544  3044.8 1837.89  3153.4 1885.27    3278 1928.46
#Mann= 15 ,-1 , 0
       0      .1       0  129.84      .1       0     384     .06       0
  504.14      .1       0   516.2    .045       0   639.5      .1       0
  744.42     .05       0 1465.27      .1       0 1534.08      .1       0
 1585.41      .1       0 1705.55     .05       0  1919.8      .1       0
  1975.1     .05       0 2024.96      .1       0 2848.61      .1       0
Bank Sta=516.2,639.5
XS Rating Curve= 0 ,0
Exp/Cntr(USF)=0,0
Exp/Cntr=0.3,0.1

Type RM Length L Ch R = 1 ,96393   ,875.3,963.3,977.9
XS GIS Cut Line= 4
2450430.11489648623508.3169571382450745.35528645623342.815752407
2451714.71948558622791.1450699732452928.39498694622176.426309545
#Sta/Elev= 30
       0 1715.97   131.7 1655.87  302.491594.566   333.3 1576.12   351.1 1571.12
   403.7 1571.63  454.981562.897   546.3 1557.84  1089.4 1552.56  1103.2 1547.18
  1201.8 1545.77 1221.571553.599  1272.1 1595.42  1327.9 1618.11  1397.8  1658.5
 1564.891735.213    1649 1776.88  1745.4 1802.88  1807.7 1801.39 1884.651777.739
  1935.9 1770.56  1988.8 1769.64  2067.8 1776.05 2197.321797.145  2256.1 1809.15
  2341.3 1837.24  2543.1 1922.97  2623.4 1962.37 2822.662040.099  2831.9 2044.44
#Mann= 9 ,-1 , 0
       0      .1       0  302.49     .06       0  454.98     .05       0
  1089.4    .045       0 1221.57      .1       0 1564.89      .1       0
 1884.65     .05       0 2197.32      .1       0 2822.66      .1       0
Bank Sta=1089.4,1221.57
XS Rating Curve= 0 ,0
Exp/Cntr(USF)=0,0
Exp/Cntr=0.3,0.1

Type RM Length L Ch R = 1 ,95430   ,988.4,970.7,869.1
XS GIS Cut Line= 4
2451005.42860816624343.703990539 2451525.5752516623894.486434842
2451856.57766106623839.319366599 2452408.2483435623476.792918141
#Sta/Elev= 30
       0 1761.99    80.9 1720.15   191.5 1658.07   353.2 1580.42   382.3 1560.72
  410.091557.804   466.8 1558.05   489.3 1552.48   526.71552.892  749.15 1552.41
   838.5  1551.3  848.471548.788   849.8 1548.09   866.9 1541.77   891.2 1541.48
   968.3 1545.33  1000.7 1543.87  1016.9 1549.34 1049.421550.235 1055.681550.099
  1132.9 1550.26  1178.6 1560.72  1207.3 1574.84 1267.021615.275  1317.4 1651.46
  1427.5 1744.93  1537.6 1827.38    1595 1860.79  1647.7 1882.04    1683  1899.9
#Mann= 10 ,-1 , 0
       0      .1       0  410.09     .06       0   526.7     .05       0
  749.15    .025       0  848.47      .1       0   849.8    .045       0
   968.3      .1       0 1049.42      .1       0 1055.68      .1       0
 1267.02      .1       0
#XS Ineff= 2 , 0
          473.45 1569.62
Permanent Ineff=
       F       F
Bank Sta=849.8,968.3
XS Rating Curve= 0 ,0
Exp/Cntr(USF)=0,0
Exp/Cntr=0.3,0.1

Type RM Length L Ch R = 1 ,94460   ,843.6,839.2,816.9
XS GIS Cut Line= 4
2451533.45626135625068.7568874532451911.74472931624816.564575483
2452518.58247999624446.1571172772452952.03801618624186.083795558
#Sta/Elev= 30
       0 1852.66   106.1 1796.14   282.1 1679.49  375.071629.962   437.8  1586.4
     458 1567.35  486.981566.255   522.1  1563.9   561.3 1553.29     589 1554.63
   600.6 1545.14   612.8 1539.55   672.8 1539.22   711.2 1539.69   728.7 1545.31
  805.471544.193   922.1 1547.81    1011 1546.63  1081.4 1541.77  1109.6  1546.6
  1123.6 1553.46  1179.9 1594.39  1200.2 1615.38  1231.1 1636.34  1254.4 1658.69
    1273  1671.4  1354.7 1699.23    1455 1749.64  1557.6 1796.45  1671.1 1822.67
#Mann= 6 ,-1 , 0
       0      .1       0  375.07     .06       0  486.98      .1       0
   600.6    .045       0   728.7    .025       0  805.47      .1       0
Bank Sta=600.6,728.7
XS Rating Curve= 0 ,0
Exp/Cntr(USF)=0,0
Exp/Cntr=0.3,0.1