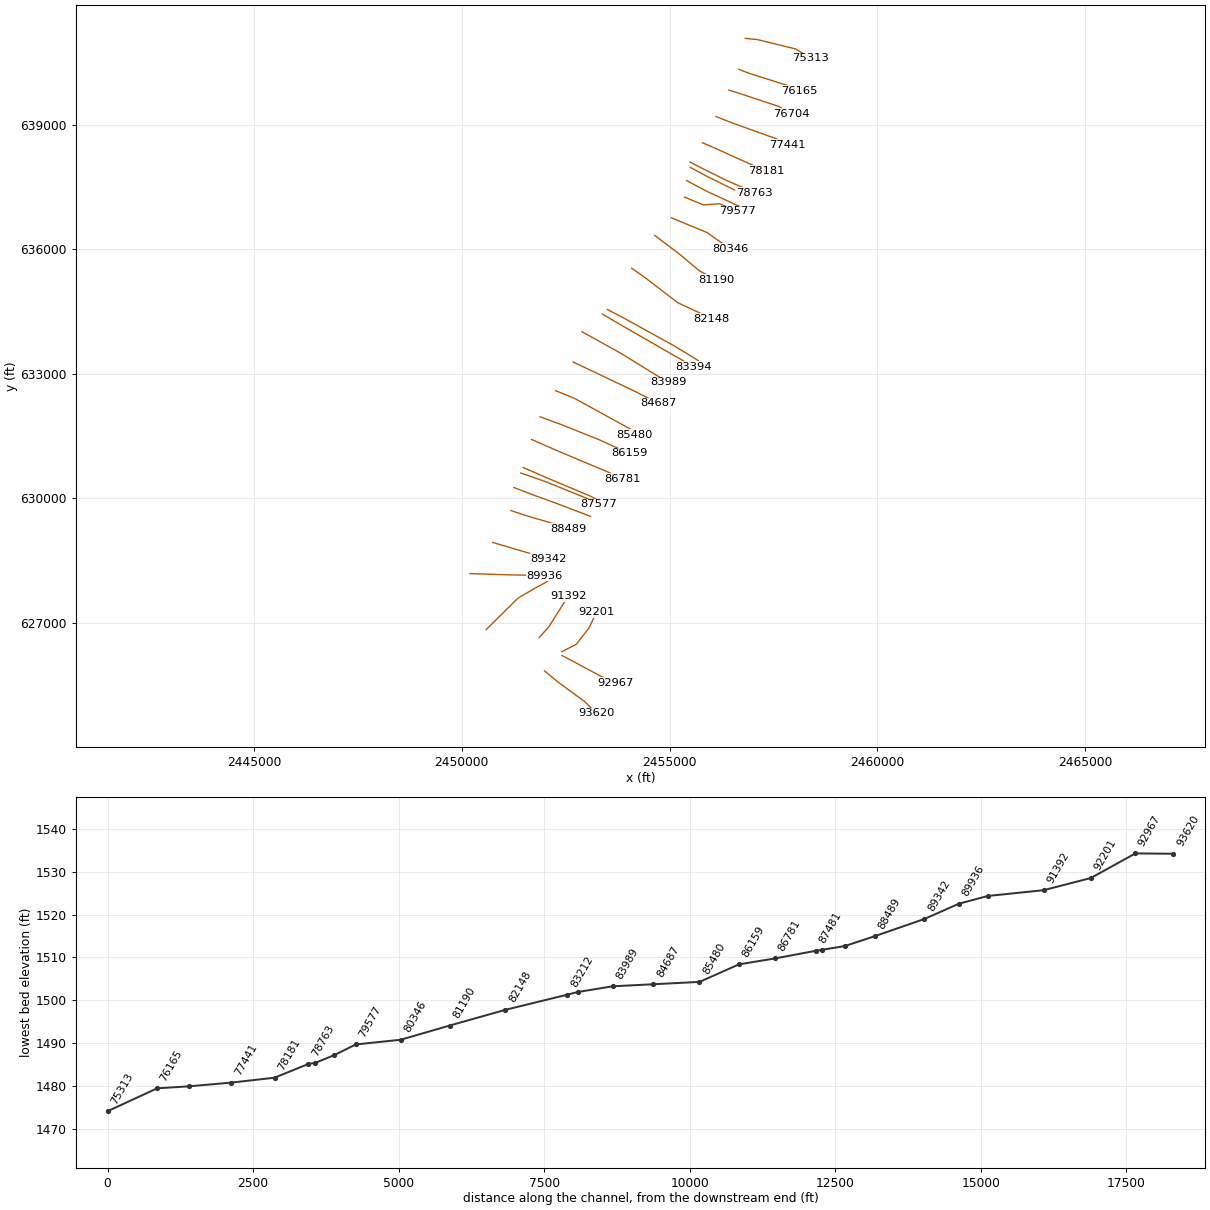
HEC-RAS study SBPOTOMC.prj: SBPOTOMC

--- SBPOTOMC.g01 (geometry) --- (continued)

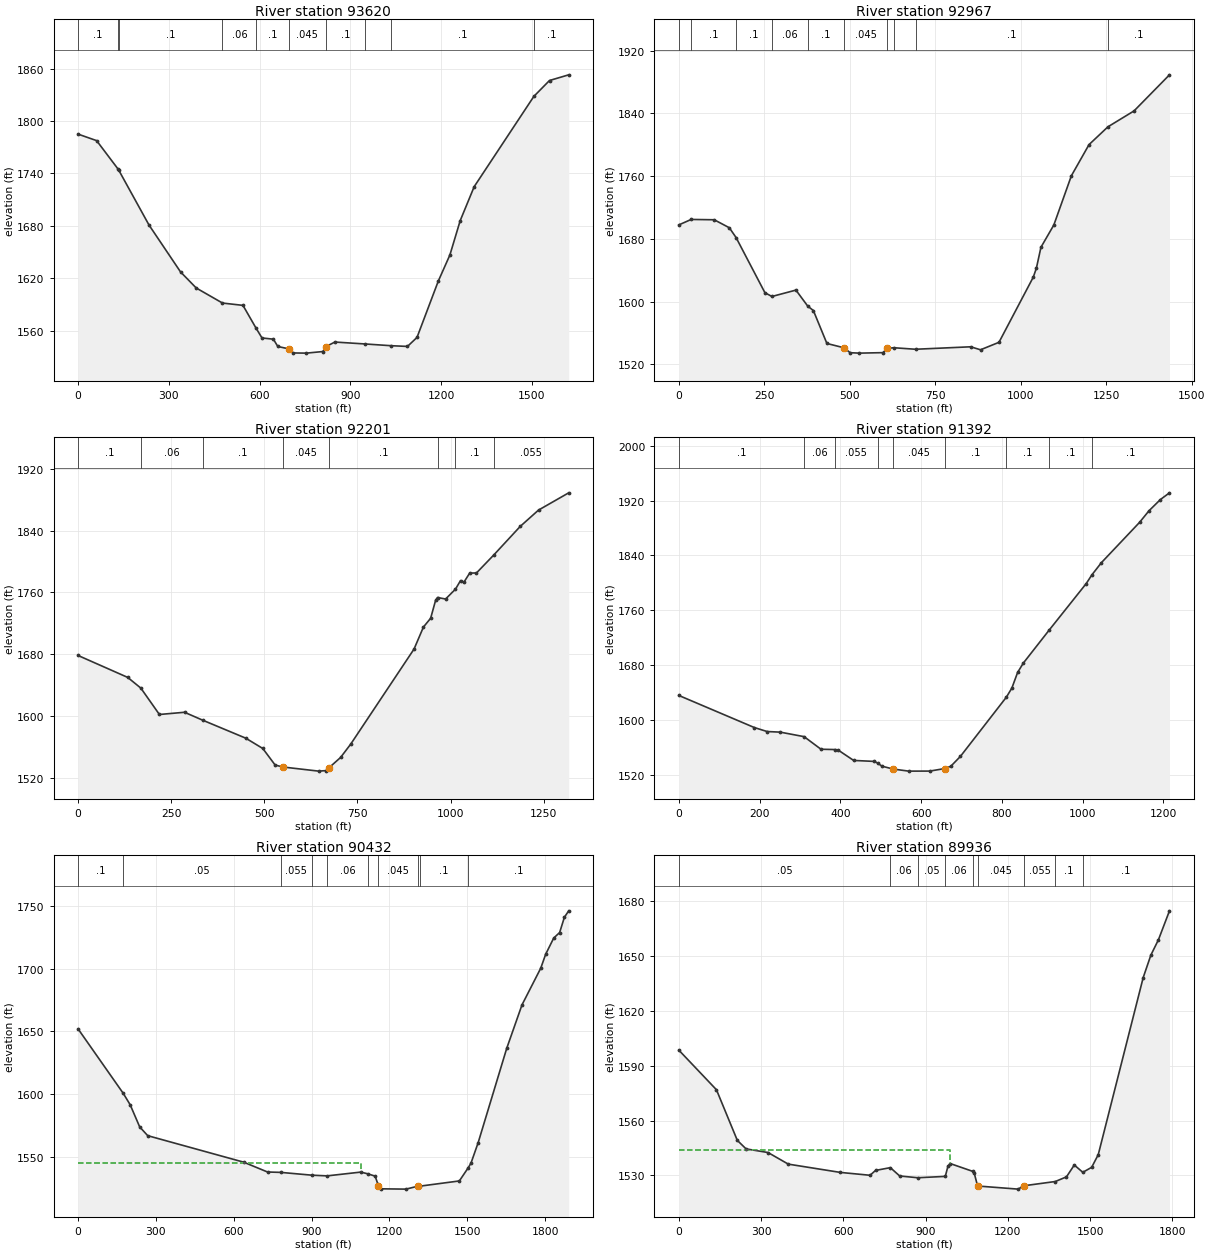
Type RM Length L Ch R = 1 ,93620   ,641,653.7,684
XS GIS Cut Line= 4
 2451990.5548268625848.9768526112452321.55723626625573.141511394
2452967.80003568 625100.28092645 2453243.6353769624824.445585232
#Sta/Elev= 30
       0 1785.08    61.3 1777.63  132.821744.769  134.751743.597   234.4 1680.98
   338.7 1627.23   390.6  1608.8  477.321591.574     545 1588.91  588.771562.502
   607.9 1551.58   645.5 1550.17   660.3  1541.8   696.6 1539.08     711  1534.4
   754.5  1534.2     809 1536.01   818.9 1541.57   848.7  1546.9  948.061544.714
 1034.571542.695  1088.8 1541.89  1120.3 1552.21  1190.7 1616.78    1229 1646.67
    1263 1685.94  1309.3 1724.92 1506.551828.335  1558.2 1846.51  1621.7 1853.01
#Mann= 10 ,-1 , 0
       0      .1       0  132.82      .1       0  134.75      .1       0
  477.32     .06       0  588.77      .1       0   696.6    .045       0
   818.9      .1       0  948.06    .025       0 1034.57      .1       0
 1506.55      .1       0
Bank Sta=696.6,818.9
XS Rating Curve= 0 ,0
Exp/Cntr(USF)=0,0
Exp/Cntr=0.3,0.1

Type RM Length L Ch R = 1 ,92967   ,638.9,766,934.2
XS GIS Cut Line= 4
 2452408.2483435626219.3843108172452676.20267497626077.526135334
2453338.20749389625722.8806966262453684.97192285625565.260501645
#Sta/Elev= 30
       0 1697.84   36.17 1704.79   103.6 1704.37   147.7 1694.18  167.391681.731
   251.8 1611.34  272.241606.531   342.5 1614.68   377.21594.135   393.5 1588.62
   433.1 1546.59  483.271541.076   501.2  1534.8   528.4 1534.28   596.6 1534.89
   610.1 1540.32  628.641541.155  692.26 1539.22   853.7 1542.36   882.4 1538.54
   936.4 1548.07  1036.7 1631.17  1045.7 1642.42  1059.2 1669.33  1096.9 1697.76
  1148.2 1760.53  1199.8 1800.24 1255.061822.918  1331.6 1843.26  1435.1 1889.24
#Mann= 10 ,-1 , 0
       0      .1       0   36.17      .1       0  167.39      .1       0
  272.24     .06       0   377.2      .1       0  483.27    .045       0
   610.1    .055       0  628.64      .1       0  692.26      .1       0
 1255.06      .1       0
Bank Sta=483.27,610.1
XS Rating Curve= 0 ,0
Exp/Cntr(USF)=0,0
Exp/Cntr=0.3,0.1

Type RM Length L Ch R = 1 ,92201   ,799.3,808.9,818.5
XS GIS Cut Line= 4
2452400.36733375626306.0754180572452755.01277246626487.338642286
2453054.49114292 626873.50811999 2453243.6353769627259.677597694
#Sta/Elev= 30
       0 1678.33   133.2 1649.94  168.481636.075   218.3  1601.9   285.7 1604.77
  334.811594.455   450.1 1571.22   495.8 1557.87   528.9 1536.47   548.9 1533.93
   645.7 1528.53   665.8  1529.2   674.3 1533.21   704.6 1546.21   731.8 1563.48
   901.9 1686.71   927.1 1715.22   946.4 1726.55   959.8 1749.97  964.811753.433
   986.5 1751.46 1013.071764.264  1026.6 1775.35  1035.5 1773.11  1051.2 1785.05
  1069.4 1785.22 1115.21 1808.17  1186.9 1845.55  1235.9 1866.65    1317 1889.02
#Mann= 8 ,-1 , 0
       0      .1       0  168.48     .06       0  334.81      .1       0
   548.9    .045       0   674.3      .1       0  964.81      .1       0
 1013.07      .1       0 1115.21    .055       0
Bank Sta=548.9,674.3
XS Rating Curve= 0 ,0
Exp/Cntr(USF)=0,0
Exp/Cntr=0.3,0.1

Type RM Length L Ch R = 1 ,91392   ,1004.3,959.6,869
XS GIS Cut Line= 4
2451864.45867081626652.8398470162452093.00795354626905.032158986
2452321.55723626627267.5586074432452557.98752873627645.847075399
#Sta/Elev= 30
       0 1635.97   187.1 1589.17   218.7 1583.38   251.1 1582.52  310.181575.936
     352 1557.59  385.871557.135   394.6 1556.36   432.9 1541.27   484.4 1539.85
  492.14 1537.36   503.3 1532.85   531.1 1528.68   569.2 1525.69   621.4 1525.76
   659.1 1529.49   673.6 1532.82   697.2 1547.11   810.91633.329   824.7 1646.69
   838.9 1669.43     853 1683.08  916.991731.154  1008.7 1798.92 1023.091811.871
  1046.4 1829.46    1141 1888.26  1164.3 1905.13  1192.6 1921.51    1215 1931.26
#Mann= 9 ,-1 , 0
       0      .1       0  310.18     .06       0  385.87    .055       0
  492.14      .1       0   531.1    .045       0   659.1      .1       0
   810.9      .1       0  916.99      .1       0 1023.09      .1       0
Bank Sta=531.1,659.1
XS Rating Curve= 0 ,0
Exp/Cntr(USF)=0,0
Exp/Cntr=0.3,0.1

Type RM Length L Ch R = 1 ,90432   ,563.2,496.6,381.4
XS GIS Cut Line= 4
2450587.73509146626841.9840809942451352.19303712627598.561016904
2451769.88655382627842.8723191252452061.48391454628000.492514107
#Sta/Elev= 30
       0    1652  174.161600.632   200.8 1591.55   237.5  1573.9   268.5 1566.92
   638.2 1545.82   730.2 1537.98  780.561537.687  901.851535.436   960.11534.905
  1089.4 1537.91 1116.151536.557  1144.9 1534.68  1157.3 1527.19  1168.3 1524.59
  1263.9 1524.34  1308.6 1526.64 1317.731526.719  1469.4 1530.86 1502.471541.001
  1514.1 1544.96  1541.9 1561.34    1652 1636.51  1710.9 1671.17  1783.2 1700.39
  1802.1 1711.49  1833.2  1724.4    1856 1728.78  1874.2 1740.93  1890.9 1746.06
#Mann= 10 ,-1 , 0
       0      .1       0  174.16     .05       0  780.56    .055       0
  901.85     .05       0   960.1     .06       0 1116.15    .055       0
  1157.3    .045       0  1308.6    .025       0 1317.73      .1       0
 1502.47      .1       0
#XS Ineff= 2 , 0
         1089.33 1545.42
Permanent Ineff=
       F       F
Bank Sta=1157.3,1308.6
XS Rating Curve= 0 ,0
Exp/Cntr(USF)=0,0
Exp/Cntr=0.3,0.1

Type RM Length L Ch R = 1 ,89936   ,617.4,593.7,508.3
XS GIS Cut Line= 4
2450201.56561376628189.6367480842451194.57284214628158.112709088
2451643.79039784628150.231699339 2451990.5548268 628142.35068959
#Sta/Elev= 30
       0 1598.49   137.2 1576.84   213.3 1549.18   245.3 1544.51   325.3 1542.53
   399.3 1536.19   589.4 1531.66   697.5  1530.1   717.5 1532.75  771.541534.268
   805.6 1529.71  871.691528.755  971.841529.491   981.7 1535.07   989.7 1536.51
 1072.141532.229  1077.7 1531.12  1089.7 1524.24  1237.7 1522.53  1257.7 1524.35
 1373.171526.689  1413.9 1529.24  1442.4 1535.71 1473.49 1531.72  1505.8 1534.45
  1529.8 1541.37  1693.8 1638.17  1721.8 1650.45  1749.5 1658.87  1789.6 1674.63
#Mann= 9 ,-1 , 0
       0     .05       0  771.54     .06       0  871.69     .05       0
  971.84     .06       0 1072.14    .035       0  1089.7    .045       0
  1257.7    .055       0 1373.17      .1       0 1473.49      .1       0
#XS Ineff= 2 , 0
          987.59 1543.94
Permanent Ineff=
       F       F
Bank Sta=1089.7,1257.7
XS Rating Curve= 0 ,0
Exp/Cntr(USF)=0,0
Exp/Cntr=0.3,0.1

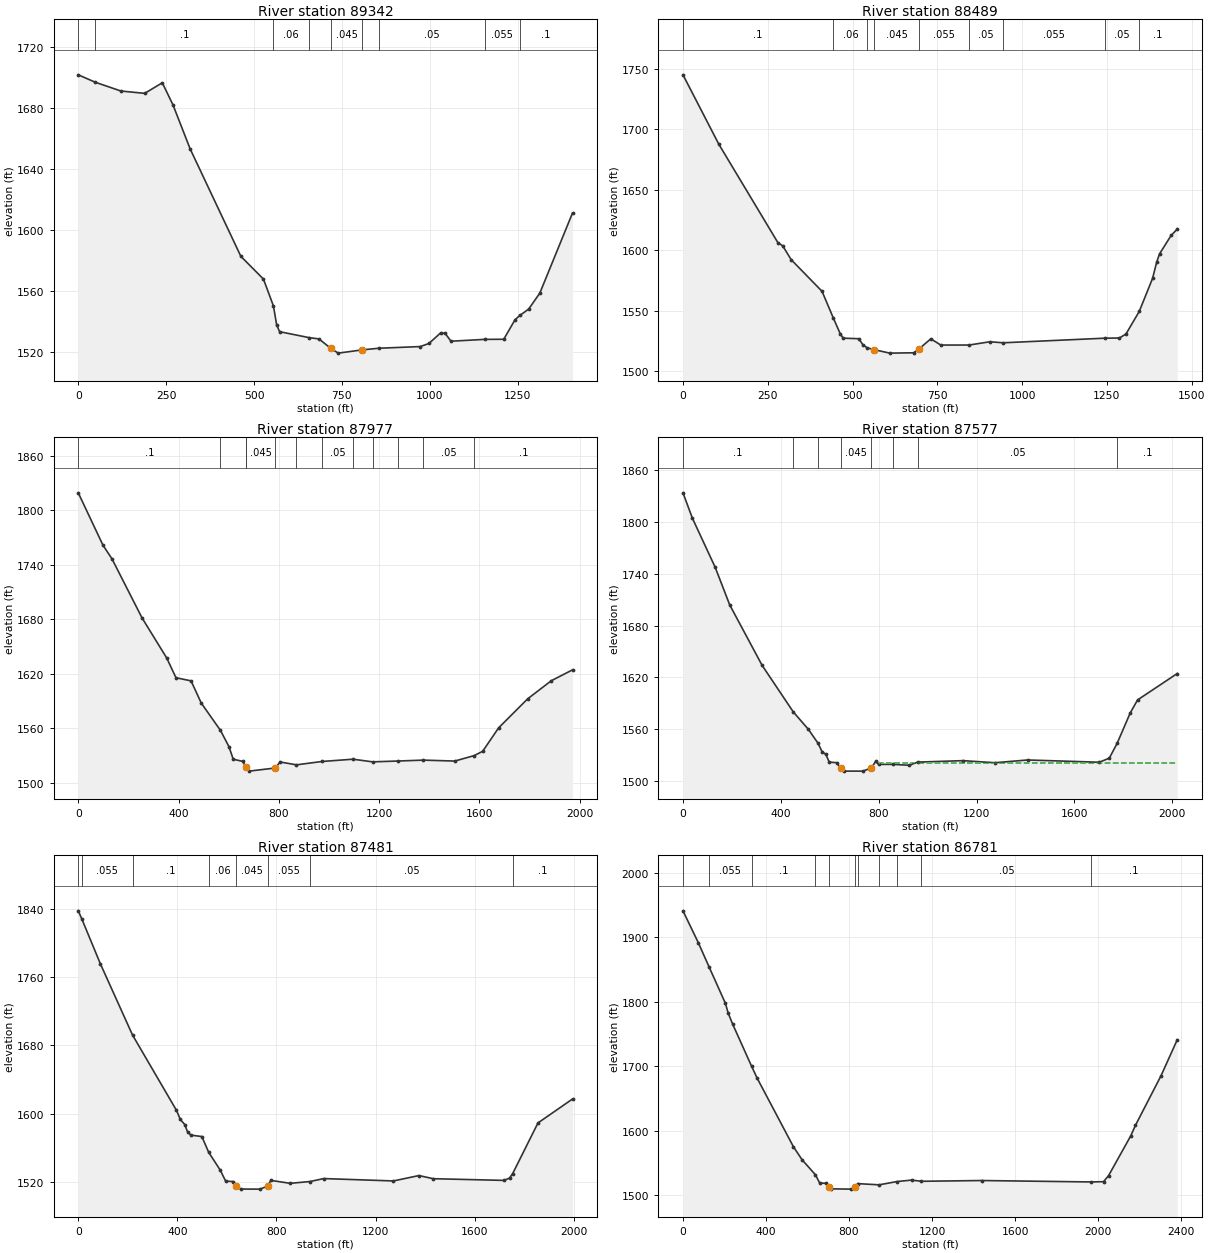
Type RM Length L Ch R = 1 ,89342   ,849.8,852.4,863
XS GIS Cut Line= 4
2450741.49516258628940.4482728082451223.14870832628798.046354939
2451922.59342256628592.8200615382452090.12509064628542.560561113
#Sta/Elev= 30
       0 1701.45   48.681696.567   121.4 1690.83     189  1689.3   239.1 1696.23
   269.5 1681.74   318.3 1652.89   462.6 1582.42   526.9  1567.5   555.41549.797
   564.4  1537.5   572.7 1533.03  655.49 1529.18     685 1528.26   718.6 1522.05
   739.5 1518.96   807.4 1521.08  855.681522.175   972.9 1523.26   997.6 1525.28
  1031.3 1532.31  1043.8 1531.89  1060.4 1526.77 1155.961527.979  1210.5 1528.05
  1242.5 1540.81 1256.071543.634  1281.5 1547.88  1313.2 1558.34  1406.1 1610.83
#Mann= 9 ,-1 , 0
       0      .1       0   48.68      .1       0   555.4     .06       0
  655.49      .1       0   718.6    .045       0   807.4    .025       0
  855.68     .05       0 1155.96    .055       0 1256.07      .1       0
Bank Sta=718.6,807.4
XS Rating Curve= 0 ,0
Exp/Cntr(USF)=0,0
Exp/Cntr=0.3,0.1

Type RM Length L Ch R = 1 ,88489   ,518.2,512.8,485.4
XS GIS Cut Line= 4
 2451181.2657913629706.9056542852451562.40033618629581.256903223
2452320.48113426629359.2774430142452571.77863638629271.323317271
#Sta/Elev= 30
       0  1745.2   105.7 1687.77   279.9 1606.35   293.9 1603.77   319.4 1592.15
     410 1566.11  443.461543.934   464.2 1530.68   472.5 1527.32   518.4 1526.86
   530.9 1521.76  543.551519.305   564.7 1517.74   609.8 1514.94   680.2 1515.22
   696.9 1518.63   730.9 1526.79   760.1 1521.62  843.811521.635   905.2 1524.35
  943.891523.493 1244.57 1527.31  1286.9 1527.46  1306.3 1530.75 1345.441549.422
  1384.8  1576.8    1397 1590.32  1405.5 1597.13  1439.4 1612.28  1457.5 1617.54
#Mann= 9 ,-1 , 0
       0      .1       0  443.46     .06       0  543.55      .1       0
   564.7    .045       0   696.9    .055       0  843.81     .05       0
  943.89    .055       0 1244.57     .05       0 1345.44      .1       0
Bank Sta=564.7,696.9
XS Rating Curve= 0 ,0
Exp/Cntr(USF)=0,0
Exp/Cntr=0.3,0.1

Type RM Length L Ch R = 1 ,87977   ,402.6,399.7,385.3
XS GIS Cut Line= 4
2451253.06490741 630262.052183222451787.46787213630057.821750844
 2452240.1786639629894.4374049432453097.94647988629567.668713142
#Sta/Elev= 30
       0 1818.97    98.5 1761.38   134.5 1746.29   254.4 1681.29   352.9 1637.11
   389.8 1615.43   449.9    1612   490.7 1587.51  567.241557.472   601.1 1539.56
   618.1 1525.75   656.4 1523.35  668.321517.063   669.1 1516.72   681.9 1512.64
   785.6 1516.09   805.2  1522.7  870.421519.563  971.47 1523.24 1095.561525.768
 1173.991522.849  1275.4 1523.77  1376.8 1524.75  1501.6 1523.72 1579.61 1529.78
    1613 1534.47  1676.8 1560.34  1792.4 1592.21  1886.5  1612.1  1971.3 1624.12
#Mann= 12 ,-1 , 0
       0      .1       0  567.24     .06       0  668.32     .05       0
   669.1    .045       0   785.6     .06       0  870.42    .055       0
  971.47     .05       0 1095.56    .055       0 1173.99     .05       0
  1275.4    .055       0  1376.8     .05       0 1579.61      .1       0
Bank Sta=669.1,785.6
XS Rating Curve= 0 ,0
Exp/Cntr(USF)=0,0
Exp/Cntr=0.5,0.3

Type RM Length L Ch R = 1 ,87577   ,98.1,96.3,88.6
XS GIS Cut Line= 4
2451422.40728711630610.6487444952452006.69694832630406.651061055
2452996.46348649630006.2111639322453296.16378686629860.138748629
#Sta/Elev= 30
       0 1833.42    38.5 1804.06   131.7 1747.28     191 1703.87   323.5 1633.95
  450.981580.125     512 1560.22  551.841544.052   568.1  1534.4   584.2 1531.04
   597.7 1522.14   627.6 1521.54   644.8 1515.04   657.8 1511.78   735.4 1511.75
     770 1515.45   787.2 1522.94   800.2  1519.5  856.74  1519.6   925.3 1518.49
   958.61522.164  1144.1 1523.87  1274.8 1521.46  1408.3 1524.63  1701.7 1522.03
  1742.5 1526.78 1775.031544.292  1828.4  1579.3  1857.9 1594.05    2020 1624.56
#Mann= 8 ,-1 , 0
       0      .1       0  450.98     .05       0  551.84     .06       0
   644.8    .045       0     770    .035       0  856.74    .055       0
   958.6     .05       0 1775.03      .1       0
#XS Ineff= 2 , 0
             614    1521     800            1521
Permanent Ineff=
       F       F
Bank Sta=644.8,770
XS Rating Curve= 0 ,0
Exp/Cntr(USF)=0,0
Exp/Cntr=0.5,0.3

Type RM Length L Ch R = 1 ,87481   ,699.6,699.3,700.6
XS GIS Cut Line= 4
2451477.81406533630744.1287102032452024.32637775630504.872167897
2453107.27704293630049.0254925552453303.71925661629943.248915956
#Sta/Elev= 30
       0 1837.57   13.921828.378    89.7 1775.22  219.031692.067   396.5 1603.79
     412 1593.15   429.9 1587.16     442 1577.93   455.1 1574.79   498.8 1573.15
  526.691554.492     573 1533.87   594.9 1520.85   625.3 1520.44   638.3 1515.41
   655.6 1511.62   733.8 1511.54   764.9 1515.23   777.1 1521.78   855.3 1518.33
  935.691520.454   990.9 1523.91  1271.9 1521.12    1375 1527.44  1432.5 1523.75
  1718.9 1521.76  1740.6 1524.55 1753.211529.715  1855.4  1589.1  1994.7 1617.12
#Mann= 8 ,-1 , 0
       0      .1       0   13.92    .055       0  219.03      .1       0
  526.69     .06       0   638.3    .045       0   764.9    .055       0
  935.69     .05       0 1753.21      .1       0
Bank Sta=638.3,764.9
XS Rating Curve= 0 ,0
Exp/Cntr(USF)=0,0
Exp/Cntr=0.5,0.3

Type RM Length L Ch R = 1 ,86781   ,619.8,621.9,633.5
XS GIS Cut Line= 4
2451679.29325885631419.0840084992452271.13838982631159.679546841
2453578.23465779630608.1302545762453865.34250855630474.650288869
#Sta/Elev= 30
       0 1940.85    73.6 1891.65  125.22 1854.34   204.7 1797.36   217.8 1782.39
   239.6 1765.16  330.351700.236   357.5 1681.57   532.2  1575.4   573.9 1555.23
  638.041532.048   658.7  1519.3   689.2 1518.72   704.5 1512.31   715.2 1510.19
   810.7 1509.76   828.1 1512.79  842.491518.281   944.71516.412 1030.88 1521.47
  1101.6 1523.78 1149.131521.896  1440.3 1523.09 1966.811520.871  2026.4 1521.31
    2051 1530.85  2158.1 1592.63  2180.1 1608.54  2303.7 1685.59  2381.5  1741.1
#Mann= 11 ,-1 , 0
       0      .1       0  125.22    .055       0  330.35      .1       0
  638.04     .06       0   704.5    .045       0   828.1    .035       0
  842.49     .06       0   944.7     .05       0 1030.88     .06       0
 1149.13     .05       0 1966.81      .1       0
Bank Sta=704.5,828.1
XS Rating Curve= 0 ,0
Exp/Cntr(USF)=0,0
Exp/Cntr=0.3,0.1

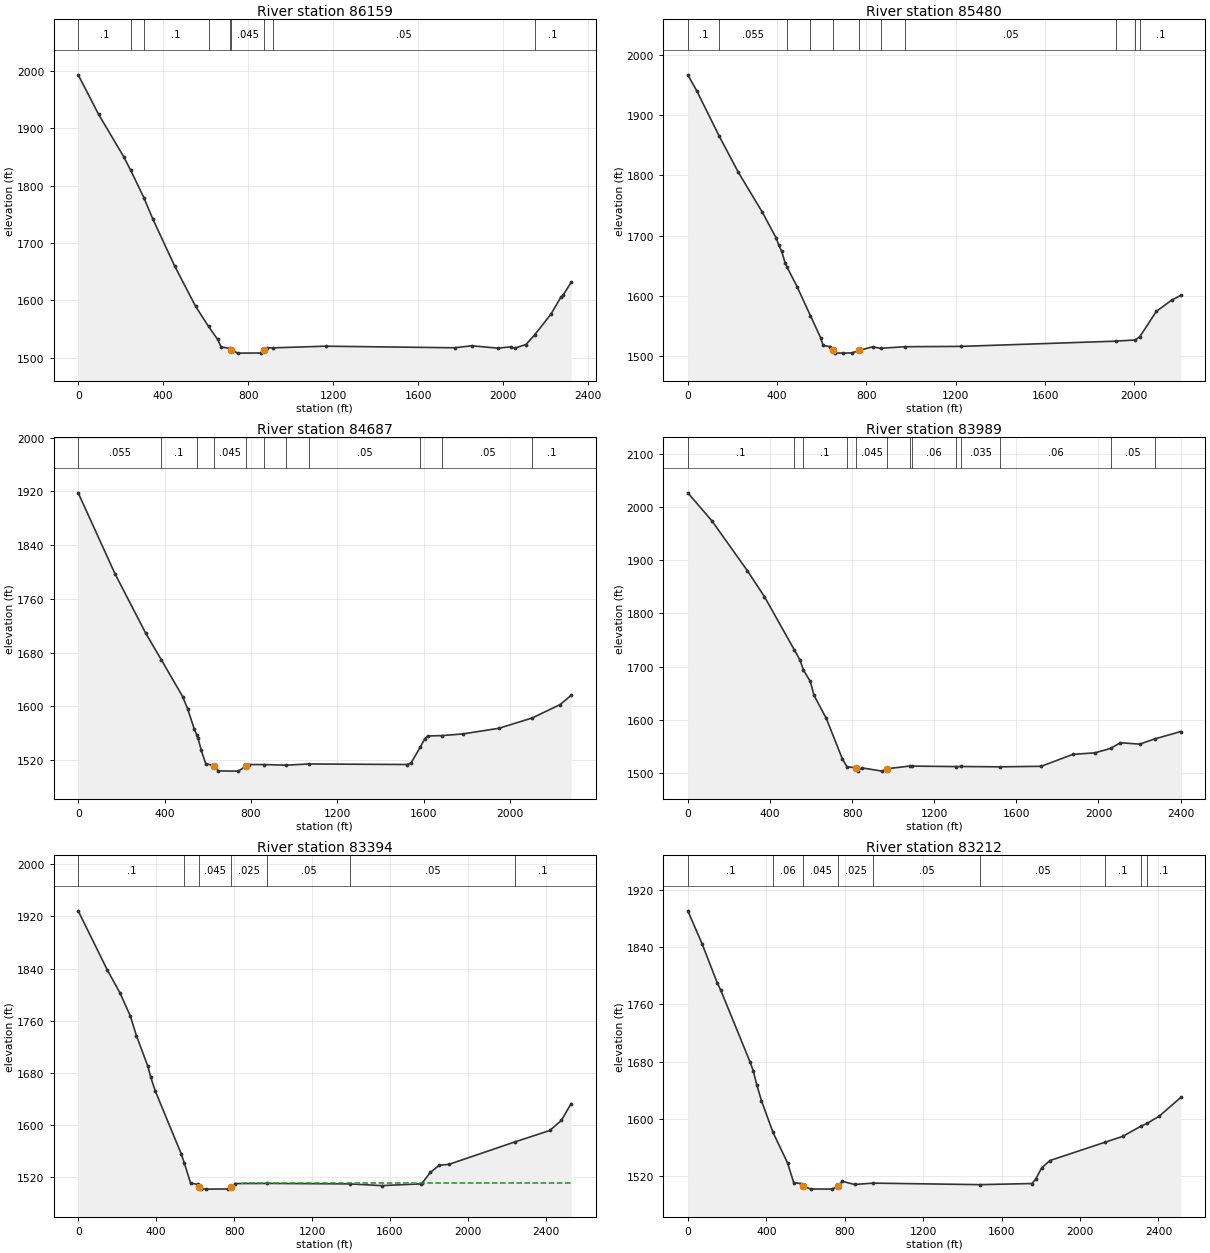
Type RM Length L Ch R = 1 ,86159   ,690.8,679,602.6
XS GIS Cut Line= 4
2451884.89879724631964.3948816922452429.37671851631763.356879994
2453287.97651743631419.916960425 2454029.3041487631084.853624261
#Sta/Elev= 30
       0 1992.57    95.8 1923.89   214.4 1849.91  247.161826.328  309.261778.608
   351.6 1741.27   453.9 1659.84     552 1589.96  613.031554.835   655.7 1532.44
   672.4 1518.91  714.791516.695   720.3 1514.34   749.9 1508.37   857.6 1508.59
   874.8 1513.79   887.8 1517.73  918.321517.578  1163.4 1520.44  1771.6 1517.68
  1850.6 1521.18  1976.6 1516.98  2034.9 1519.45  2052.5 1516.98  2106.6 1523.37
  2146.41539.885  2223.7  1576.2  2269.9 1605.38  2280.8 1609.31  2318.7 1631.54
#Mann= 9 ,-1 , 0
       0      .1       0  247.16    .055       0  309.26      .1       0
  613.03     .06       0  714.79     .05       0   720.3    .045       0
   874.8     .06       0  918.32     .05       0  2146.4      .1       0
Bank Sta=720.3,874.8
XS Rating Curve= 0 ,0
Exp/Cntr(USF)=0,0
Exp/Cntr=0.3,0.1

Type RM Length L Ch R = 1 ,85480   ,787.4,793.3,830.4
XS GIS Cut Line= 4
2452257.24723086632593.3245713892452713.18844893 632408.09845155
2454120.50045961631633.5403809622454162.56744865631532.579607267
#Sta/Elev= 30
       0  1967.6    40.5 1940.62  139.471866.409   226.1 1805.41   334.1 1738.68
     396 1695.78   407.5 1683.94   420.6 1673.54   435.9 1654.46  445.131646.978
   489.5 1614.81  548.931566.828   594.4 1530.15   606.1 1517.03   638.5 1514.94
   649.1 1508.84   658.3 1504.52   693.7 1504.27   735.9 1504.73   768.4 1508.89
   827.2 1514.76  863.241512.273  970.681514.948  1224.7 1515.48  1919.61524.222
    20041526.241 2025.041531.913  2098.5  1573.8  2166.7 1592.39  2207.9 1600.48
#Mann= 11 ,-1 , 0
       0      .1       0  139.47    .055       0  445.13      .1       0
  548.93     .06       0   649.1    .045       0   768.4      .1       0
  863.24     .06       0  970.68     .05       0  1919.6      .1       0
    2004     .05       0 2025.04      .1       0
Bank Sta=649.1,768.4
XS Rating Curve= 0 ,0
Exp/Cntr(USF)=0,0
Exp/Cntr=0.3,0.1

Type RM Length L Ch R = 1 ,84687   ,703,698.1,642.8
XS GIS Cut Line= 4
2452676.48592893 633283.706767842453103.69168254633082.668766141
2454159.14119146632580.0737618942454732.93715464632291.081634453
#Sta/Elev= 30
       0 1917.96   170.5 1797.48   311.9  1709.6  385.681669.152   484.4 1614.44
   507.3 1596.17   537.3 1566.83  549.171557.727   555.3 1552.49   570.3 1534.57
   590.7 1515.01   630.6  1511.4   648.3 1504.03   741.4 1503.72   777.4 1511.01
     792 1513.54  859.52  1513.5  962.971512.605 1068.44 1514.37  1525.5 1513.56
  1543.2 1516.46 1583.68 1538.95  1605.7 1551.88  1618.6 1556.04 1687.441556.625
    1784 1559.17  1949.7 1567.55 2104.051582.955  2231.9  1602.7  2283.6 1616.47
#Mann= 11 ,-1 , 0
       0    .055       0  385.68      .1       0  549.17     .06       0
   630.6    .045       0   777.4      .1       0  859.52     .12       0
  962.97     .06       0 1068.44     .05       0 1583.68      .1       0
 1687.44     .05       0 2104.05      .1       0
Bank Sta=630.6,777.4
XS Rating Curve= 0 ,0
Exp/Cntr(USF)=0,0
Exp/Cntr=0.3,0.1

Type RM Length L Ch R = 1 ,83989   ,595.8,594.9,606.5
XS GIS Cut Line= 4
2452892.42948992634011.3002759122453507.30243311 633671.83917186
2453827.54875768633492.5012300962454961.22074669632794.364242517
#Sta/Elev= 30
       0 2027.01   116.9  1974.5   290.5 1880.23   373.3 1831.55  518.881731.319
   546.4 1712.17  563.381693.254   596.7 1672.07   614.3 1646.13   674.3  1602.6
   752.1 1526.79   774.51511.882   820.2 1509.06   830.1 1504.42   848.4 1509.34
   946.6 1503.24   972.2 1507.82 1079.821512.769 1092.021512.708 1306.891511.798
 1331.541511.963 1521.751511.319  1720.9 1512.33  1875.3 1534.77  1982.9 1537.68
 2058.931545.946  2106.6  1556.7  2200.6 1554.04 2273.79 1563.83  2400.8 1577.76
#Mann= 13 ,-1 , 0
       0      .1       0  518.88    .055       0  563.38      .1       0
   774.5     .06       0   820.2    .045       0   972.2    .025       0
 1079.82     .12       0 1092.02     .06       0 1306.89    .055       0
 1331.54    .035       0 1521.75     .06       0 2058.93     .05       0
 2273.79      .1       0
Bank Sta=820.2,972.2
XS Rating Curve= 0 ,0
Exp/Cntr(USF)=0,0
Exp/Cntr=0.5,0.3

Type RM Length L Ch R = 1 ,83394   ,180.2,182.5,193.5
XS GIS Cut Line= 4
2453386.82942394634436.2349314792453882.97193799634144.090100873
2454938.21921405633537.1340303912455577.91565348633171.952992133
#Sta/Elev= 30
       0 1928.44   148.4 1838.43   214.2 1802.78   266.8 1767.83   298.9 1737.08
   357.4 1690.33   371.3 1674.26   395.3 1652.64   529.1 1555.66  544.821541.917
   576.5 1511.19   612.4 1509.33   621.6  1505.5   630.9 1502.35   655.6 1501.92
   770.7 1502.14   783.2 1504.68   806.2 1510.45  969.611510.665 1394.281509.947
  1556.9 1507.31  1757.1 1509.97    1766 1511.42  1807.5 1527.72  1854.1 1538.63
  1902.5 1539.88 2243.071574.498  2420.1 1591.79    2480 1607.33  2529.7 1633.12
#Mann= 7 ,-1 , 0
       0      .1       0  544.82     .06       0   621.6    .045       0
   783.2    .025       0  969.61     .05       0 1394.28     .05       0
 2243.07      .1       0
#XS Ineff= 2 , 0
             564 1513.38     840         1510.65
Permanent Ineff=
       F       F
Bank Sta=621.6,783.2
XS Rating Curve= 0 ,0
Exp/Cntr(USF)=0,0
Exp/Cntr=0.5,0.3

Type RM Length L Ch R = 1 ,83212   ,1076.7,1063.3,963.6
XS GIS Cut Line= 4
2453501.57939424 634548.570861862453878.52564742634351.721151864
2455130.82486634633660.6530210252455692.05595441633317.213101456
#Sta/Elev= 30
       0 1891.04    72.8 1844.83   150.3 1790.01   168.3 1779.66   317.2 1679.46
   334.1 1666.57   351.9 1647.08   375.6 1625.09  434.581580.631   508.5 1538.01
   539.7  1510.5   576.3 1509.08   586.8 1505.36   626.5 1501.53   736.2 1501.29
   766.4 1505.63   788.1 1512.18   850.4 1507.81   944.61509.694 1489.371507.569
    1755 1509.13  1773.2 1515.05  1803.8 1530.79  1846.3 1541.33 2126.871566.941
  2216.6 1575.09 2310.711589.412 2341.491593.267  2404.2 1603.62  2513.6 1629.66
#Mann= 9 ,-1 , 0
       0      .1       0  434.58     .06       0   586.8    .045       0
   766.4    .025       0   944.6     .05       0 1489.37     .05       0
 2126.87      .1       0 2310.71     .05       0 2341.49      .1       0
Bank Sta=586.8,766.4
XS Rating Curve= 0 ,0
Exp/Cntr(USF)=0,0
Exp/Cntr=0.5,0.3

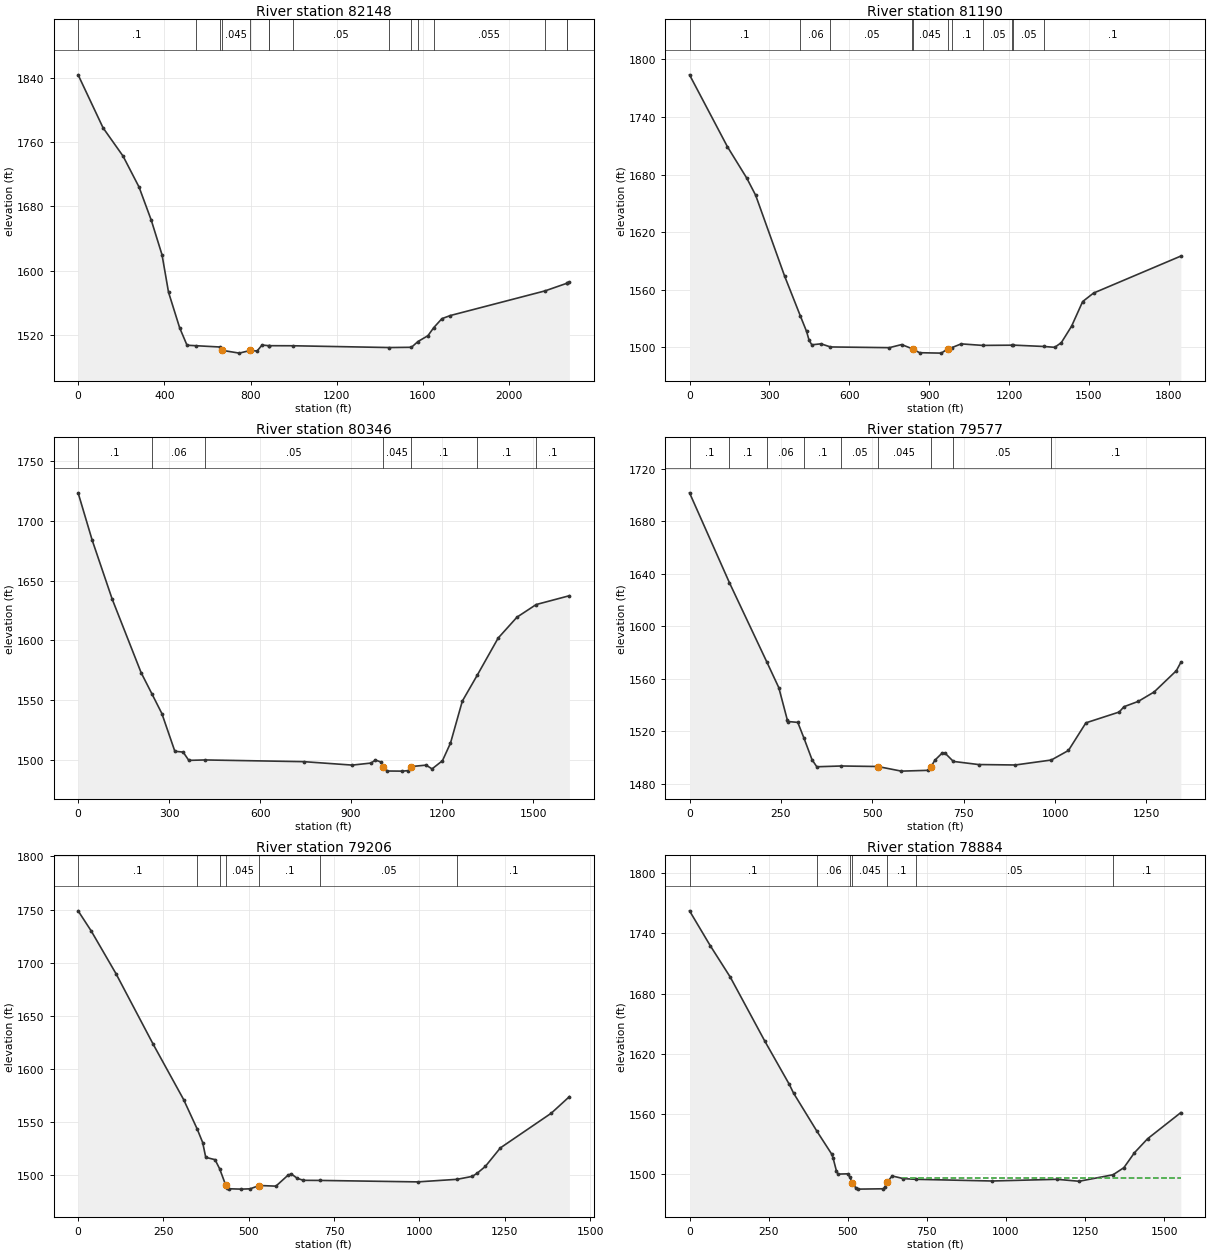
Type RM Length L Ch R = 1 ,82148   ,953.2,957.7,935.6
XS GIS Cut Line= 4
2454087.94023252635541.1959952472454410.43869358635315.028243336
2455189.46095016634716.1025299422456006.17783207634330.779693353
#Sta/Elev= 30
       0 1843.58   115.8 1777.71   208.6 1742.56   282.7 1704.14   339.7 1662.73
   389.4 1619.89   419.5 1573.46   471.2 1529.21   505.3 1507.56   546.71506.962
  659.541505.343   666.7 1501.28   747.9 1497.75   797.9 1501.04   830.6 1500.41
   853.4 1507.81  885.221506.995  885.68 1506.99  998.081506.899 1443.321504.688
 1546.661505.004    1577 1512.19  1623.1 1519.39    16501529.413  1687.9 1540.58
  1727.4  1544.5 2166.721575.118 2266.711584.465 2270.061584.715  2279.6 1585.74
#Mann= 15 ,-1 , 0
       0      .1       0   546.7     .06       0  659.54    .025       0
   666.7    .045       0   797.9    .025       0  885.22      .1       0
  885.68     .05       0  998.08     .05       0 1443.32     .05       0
 1546.66      .1       0    1577     .05       0    1650    .055       0
 2166.72      .1       0 2266.71    .055       0 2270.06      .1       0
Bank Sta=666.7,797.9
XS Rating Curve= 0 ,0
Exp/Cntr(USF)=0,0
Exp/Cntr=0.3,0.1

Type RM Length L Ch R = 1 ,81190   ,727.8,844.8,853.8
XS GIS Cut Line= 4
 2454640.7947372636332.783126936 2455264.8502008635859.506164604
2455717.18570462635478.3716197172456131.82658313635256.392159508
#Sta/Elev= 30
       0 1783.87   142.1 1709.11     215 1676.29   248.3  1658.5   356.8  1574.5
  416.571532.514   439.6 1516.61   449.2 1507.28   459.3 1502.75   493.8 1503.78
  529.021500.516   750.5 1499.77   796.6    1503  836.58 1498.59   838.9 1497.97
   864.5 1494.51   945.6 1494.08   969.5 1498.54  984.561499.761  1020.1 1503.71
 1100.311502.126 1212.181502.364 1216.071502.427 1331.821500.985  1371.5 1500.12
  1396.2 1505.02  1434.6 1522.08  1476.3 1547.79  1517.3 1556.64    1845 1595.15
#Mann= 11 ,-1 , 0
       0      .1       0  416.57     .06       0  529.02     .05       0
  836.58    .025       0   838.9    .045       0   969.5    .025       0
  984.56      .1       0 1100.31     .05       0 1212.18     .05       0
 1216.07     .05       0 1331.82      .1       0
Bank Sta=838.9,969.5
XS Rating Curve= 0 ,0
Exp/Cntr(USF)=0,0
Exp/Cntr=0.3,0.1

Type RM Length L Ch R = 1 ,80346   ,585.3,768.5,837.6
XS GIS Cut Line= 4
2455042.87074059636755.8005888432455901.47053951636399.795794169
2456177.89779185636202.9460841722456471.07821099636010.284665877
#Sta/Elev= 30
       0 1723.43    46.5 1683.77   112.4 1634.54   207.7 1573.09  243.921555.051
   276.1 1538.91   318.9 1507.36   346.3 1506.67   364.9 1499.74  418.411500.103
   744.7 1498.66   903.6 1495.79   965.5  1497.5   980.2    1500     997 1498.51
  1005.6 1494.61  1019.4 1490.85    1069 1490.75  1088.2 1491.17    1098 1494.56
  1147.1 1495.78  1166.8 1492.62  1201.1 1499.46  1227.6 1514.18  1266.6 1549.29
    13161571.035  1384.7 1601.99  1446.9  1619.5 1510.141630.038  1619.7 1637.41
#Mann= 7 ,-1 , 0
       0      .1       0  243.92     .06       0  418.41     .05       0
  1005.6    .045       0    1098      .1       0    1316      .1       0
 1510.14      .1       0
Bank Sta=1005.6,1098
XS Rating Curve= 0 ,0
Exp/Cntr(USF)=0,0
Exp/Cntr=0.3,0.1

Type RM Length L Ch R = 1 ,79577   ,367.5,371.2,143.2
XS GIS Cut Line= 4
2455356.99261825637254.2073013882455813.51641377637065.734174795
2456198.83925036 637095.052216712456626.04500397636914.955673521
#Sta/Elev= 30
       0 1701.74  109.271633.177  211.291572.933   244.2 1553.27   267.3 1528.88
   270.2 1527.46   296.2 1526.79  313.311514.604   335.1 1498.39   348.1 1492.99
  415.331493.578   515.2 1493.18   579.4 1489.66   651.6 1490.26   660.2 1492.88
   671.3 1498.03   691.7  1503.6   699.7 1503.16  721.721497.065   790.6 1494.68
     891 1494.34  989.591498.122  1036.5  1505.4  1084.3 1526.46  1175.4  1534.7
  1188.4 1538.75  1227.5  1542.8  1270.9 1549.98  1331.7 1566.19    1344 1572.57
#Mann= 9 ,-1 , 0
       0      .1       0  109.27      .1       0  211.29     .06       0
  313.31      .1       0  415.33     .05       0   515.2    .045       0
   660.2      .1       0  721.72     .05       0  989.59      .1       0
#XS Ineff= 2 , 0
                          693.32         1496.12
Permanent Ineff=
       F       F
Bank Sta=515.2,660.2
XS Rating Curve= 0 ,0
Exp/Cntr(USF)=0,0
Exp/Cntr=0.3,0.1

Type RM Length L Ch R = 1 ,79206   ,323.3,322.4,314.3
XS GIS Cut Line= 4
2455409.08225913637651.4800183482455755.61787461637465.933389586
2455962.99351852637362.2455676312456702.45140667637021.167205937
#Sta/Elev= 30
       0 1748.77    38.2 1729.95   110.8  1689.8   220.3 1623.14     309 1571.41
   348.7 1543.78   364.9 1530.99   373.9 1517.03   401.1 1514.85   414.5 1506.38
   432.4 1490.91   436.8 1488.27   441.3 1487.51   477.1 1487.16   503.9 1487.45
   530.7 1490.57   579.5 1489.97   615.3 1500.38   624.7 1501.39   642.3 1497.27
   659.9 1495.43   708.7 1495.34   995.1 1493.97  1110.4 1496.39  1154.8 1499.15
  1169.9 1502.33  1192.9 1508.49    1237 1525.92  1386.2 1558.56  1439.3 1574.14
#Mann= 7 ,-1 , 0
       0      .1       0   348.7     .06       0   414.5      .1       0
   432.4    .045       0   530.7      .1       0   708.7     .05       0
  1110.4      .1       0
#XS Ineff= 2 , 0
                          624.49         1497.08
Permanent Ineff=
       F       F
Bank Sta=432.4,530.7
XS Rating Curve= 0 ,0
Exp/Cntr(USF)=0,0
Exp/Cntr=0.5,0.3

Type RM Length L Ch R = 1 ,78884   ,120.8,120.6,126.9
XS GIS Cut Line= 4
2455497.32397608637969.6762878572455895.24538328637755.604644741
2456728.86554647637342.5722980222456885.01192145637274.573070209
#Sta/Elev= 30
       0 1762.46    65.2 1727.91   128.8 1696.44   237.8 1632.78     315 1589.83
   328.6 1581.02  402.391543.092   449.1  1520.3   453.5 1516.48   463.9 1503.83
   469.1 1500.33   499.8 1500.61  506.86 1497.16   513.8 1491.84   525.5 1486.62
   531.6 1485.37     612 1485.71   616.5 1487.05   625.1  1492.4   640.1  1498.5
   675.9 1495.83  714.731495.146   955.7 1493.47  1161.1 1495.14  1231.1  1493.2
 1338.351499.671  1372.5 1506.75    1406 1521.65  1447.2 1535.49  1552.5 1561.59
#Mann= 7 ,-1 , 0
       0      .1       0  402.39     .06       0  506.86      .1       0
   513.8    .045       0   625.1      .1       0  714.73     .05       0
 1338.35      .1       0
#XS Ineff= 2 , 0
             468    1498     670         1496.57
Permanent Ineff=
       F       F
Bank Sta=513.8,625.1
XS Rating Curve= 0 ,0
Exp/Cntr(USF)=0,0
Exp/Cntr=0.5,0.3

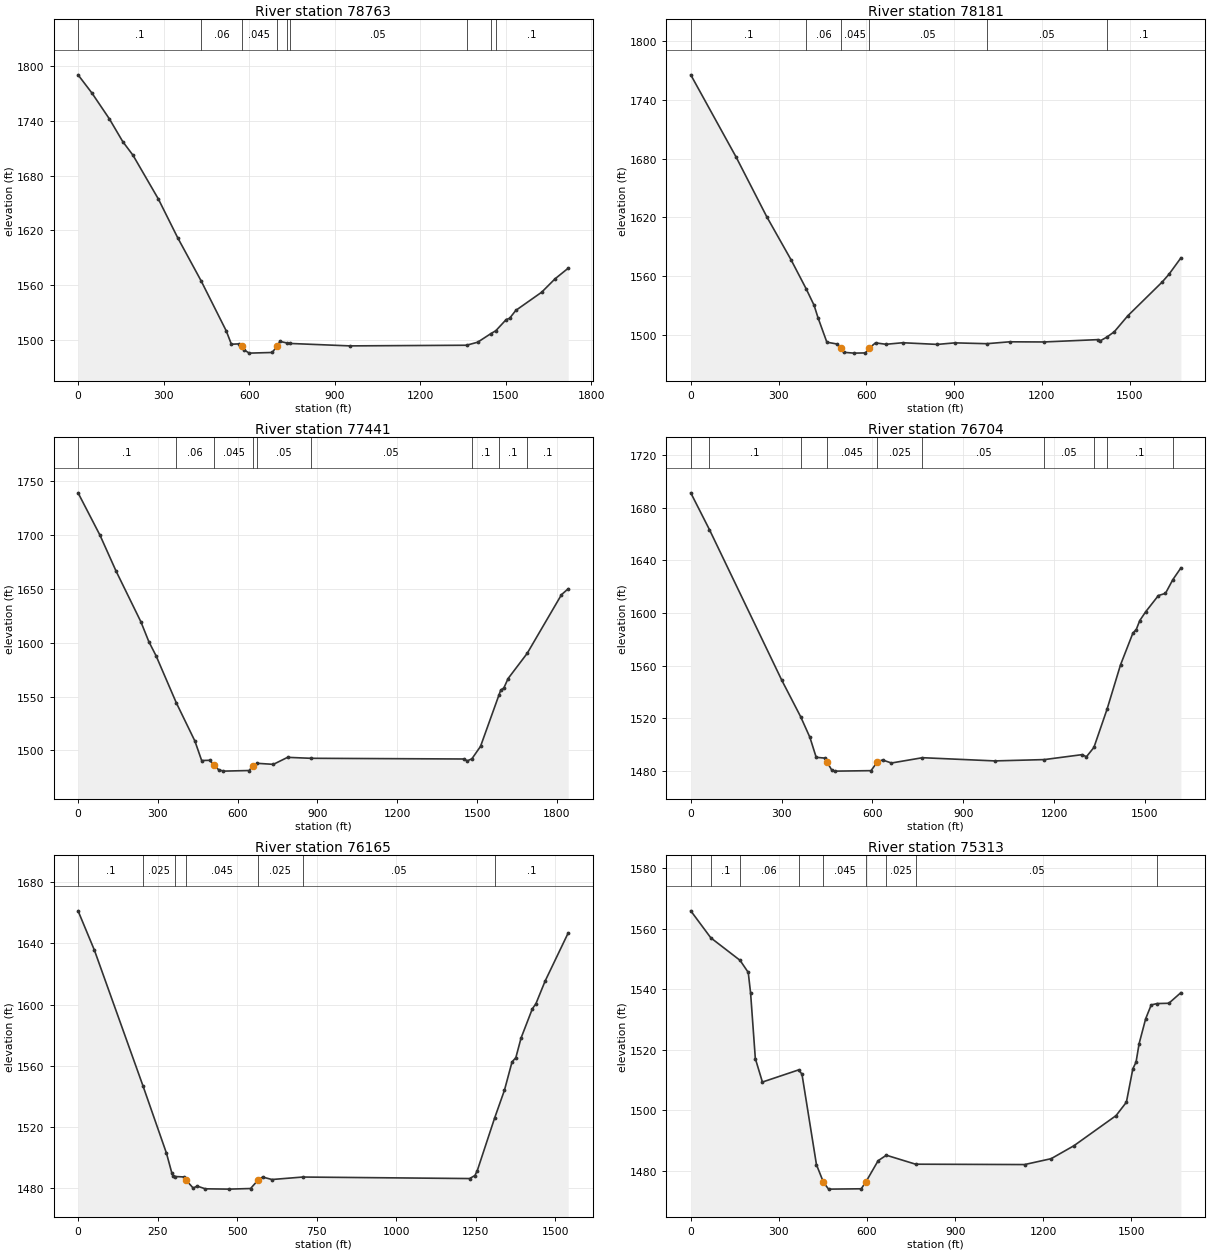
Type RM Length L Ch R = 1 ,78763   ,578.3,582,595.2
XS GIS Cut Line= 4
 2455487.2500164638098.1192737272455953.17065142637861.381221339
2456333.46262919637672.4944774132457038.63980651637360.201727455
#Sta/Elev= 30
       0 1790.47    48.8 1770.43   110.1 1742.01   156.7 1717.21   192.6 1702.25
   281.7 1654.14   349.4 1611.69  431.281564.519   519.7 1509.44   537.6 1494.86
   564.6 1495.26   573.4 1493.19   582.4 1488.64   600.2  1485.1   680.8 1485.82
   698.1 1492.92   707.7 1497.97   732.11496.283  743.441495.714     953 1493.04
 1361.991493.755  1401.2  1497.1 1447.93 1506.62 1464.661509.665  1501.2 1521.97
    1513  1523.3  1534.8 1531.98  1625.5 1551.95  1672.3 1566.61  1718.5 1578.28
#Mann= 9 ,-1 , 0
       0      .1       0  431.28     .06       0   573.4    .045       0
   698.1    .045       0   732.1      .1       0  743.44     .05       0
 1361.99     .05       0 1447.93     .05       0 1464.66      .1       0
Bank Sta=573.4,698.1
XS Rating Curve= 0 ,0
Exp/Cntr(USF)=0,0
Exp/Cntr=0.5,0.3

Type RM Length L Ch R = 1 ,78181   ,731.5,740.3,773.9
XS GIS Cut Line= 4
2455792.40363604638560.9825187492456130.73538457638414.159307123
 2457037.2091259638005.6077617312457324.47193126637884.319021693
#Sta/Elev= 30
       0 1765.22   155.2 1681.37   259.8  1620.7   342.7 1576.93  394.521547.263
   421.5 1530.55   434.6 1518.15   465.1 1493.01   500.5 1491.16   513.1 1486.69
   522.4 1482.73   557.5 1481.89     597 1482.11   610.1 1487.04   631.4 1492.34
   667.2  1490.9   724.2 1492.46   842.7 1490.77   902.4 1492.34 1011.591491.501
  1089.2 1493.41    1206 1493.26  1390.7 1495.62  1399.5 1494.47  1422.61498.349
  1447.3 1503.66  1493.5 1519.93  1610.6 1554.18    1634 1562.13  1674.9 1578.86
#Mann= 6 ,-1 , 0
       0      .1       0  394.52     .06       0   513.1    .045       0
   610.1     .05       0 1011.59     .05       0  1422.6      .1       0
Bank Sta=513.1,610.1
XS Rating Curve= 0 ,0
Exp/Cntr(USF)=0,0
Exp/Cntr=0.3,0.1

Type RM Length L Ch R = 1 ,77441   ,732.5,736.7,744
XS GIS Cut Line= 4
2456117.96814877639192.9606905262456488.21798678639046.137478901
2457573.43302923  638656.7367872 2457828.7777451638516.297193471
#Sta/Elev= 30
       0 1739.37    82.6 1699.92   142.8 1666.71   236.4 1619.43     266 1601.15
   293.4 1587.88  369.351544.266   439.2 1508.75   464.7  1490.6   494.5 1490.82
   512.3 1486.29   528.5 1482.01   546.7 1480.75   643.6 1481.32   656.1 1485.68
  672.591488.025   734.3 1487.05   787.7 1493.56  874.631492.678  1450.7 1492.03
  1463.4 1490.29 1480.731492.253  1513.1 1503.75 1583.081551.953  1589.3 1556.16
  1600.7 1557.96  1616.7 1566.77  1688.5 1590.19  1817.5 1644.75  1842.7 1650.18
#Mann= 9 ,-1 , 0
       0      .1       0  369.35     .06       0   512.3    .045       0
   656.1    .025       0  672.59     .05       0  874.63     .05       0
 1480.73      .1       0 1583.08      .1       0  1688.5      .1       0
Bank Sta=512.3,656.1
XS Rating Curve= 0 ,0
Exp/Cntr(USF)=0,0
Exp/Cntr=0.3,0.1

Type RM Length L Ch R = 1 ,76704   ,534.9,539.3,540.1
XS GIS Cut Line= 4
2456424.38180782639831.3224802012456705.26099527639741.951829647
 2457630.8855903639435.5381706032457930.91563145639256.796869494
#Sta/Elev= 30
       0 1691.22   61.751663.258   300.5 1548.97  363.091521.148   393.6 1505.49
   414.3 1490.36     444 1489.74  450.011486.943   466.1 1480.47   477.5 1479.87
   595.5 1480.23   616.5 1486.96   633.4 1488.36   662.9 1486.04  765.421490.065
    1004 1487.63 1167.761488.629  1292.9  1492.4  1306.9 1490.78 1331.651497.876
 1375.05 1526.89  1419.5 1560.56  1460.5 1584.75  1471.5 1587.41  1483.1 1594.21
  1502.4 1600.82  1544.6 1613.21    1568 1614.87 1592.521625.353    1619 1634.22
#Mann= 10 ,-1 , 0
       0      .1       0   61.75      .1       0  363.09     .06       0
  450.01    .045       0   616.5    .025       0  765.42     .05       0
 1167.76     .05       0 1331.65      .1       0 1375.05      .1       0
 1592.52      .1       0
Bank Sta=450.01,616.5
XS Rating Curve= 0 ,0
Exp/Cntr(USF)=0,0
Exp/Cntr=0.3,0.1

Type RM Length L Ch R = 1 ,76165   ,843.7,851.6,876.2
XS GIS Cut Line= 4
2456666.95928789640329.2446761472456877.61867849 640246.25764349
2457879.84668828639927.0767486522458116.04055046639812.171626511
#Sta/Elev= 30
       0 1661.22    51.4 1635.52  203.95 1546.97     278 1502.85   294.8 1489.96
     299 1487.72  304.631487.657   332.5 1487.37  340.461485.131   361.9  1480.1
   374.5 1481.41   399.7 1479.62   474.8 1479.41   542.4 1479.81  565.081485.131
   580.2 1487.31   609.6 1485.69  706.261487.306  1230.9 1486.32  1247.7  1488.3
  1255.2 1491.56  1309.71525.915  1340.4 1543.96  1364.3 1562.49  1376.3 1565.31
  1392.7 1578.11  1428.3 1597.29  1439.1 1600.38  1468.3 1615.32  1540.9 1646.78
#Mann= 7 ,-1 , 0
       0      .1       0  203.95    .025       0  304.63     .06       0
  340.46    .045       0  565.08    .025       0  706.26     .05       0
  1309.7      .1       0
Bank Sta=340.46,565.08
XS Rating Curve= 0 ,0
Exp/Cntr(USF)=0,0
Exp/Cntr=0.3,0.1

Type RM Length L Ch R = 1 ,75313   ,679.8,679.7,646.4
XS GIS Cut Line= 4
2456820.16611742641076.1279700672457120.19615856641044.209880583
 2458033.0535178640820.7832541972458396.91973791640597.356627811
#Sta/Elev= 30
       0 1565.83   68.361556.917  167.821549.502   195.7 1545.52   203.7  1538.7
   219.8 1517.12   243.9 1509.37  366.861513.366   378.5 1512.01   427.9 1482.12
   451.8 1476.29   469.1 1474.06   580.3 1474.17   596.7 1476.54   637.9 1483.44
  665.741485.243  765.371482.283  1136.2 1482.16  1226.8  1484.1  1304.5 1488.38
  1447.7  1498.3  1482.9 1502.72    1505 1513.77  1515.8 1515.94  1526.2 1522.02
  1548.6 1530.26  1567.4  1534.8 1587.35 1535.25  1627.4 1535.35  1668.5 1538.85
#Mann= 9 ,-1 , 0
       0     .12       0   68.36      .1       0  167.82     .06       0
  366.86      .1       0   451.8    .045       0   596.7      .1       0
  665.74    .025       0  765.37     .05       0 1587.35      .1       0
Bank Sta=451.8,596.7
XS Rating Curve= 0 ,0
Exp/Cntr(USF)=0,0
Exp/Cntr=0.3,0.1