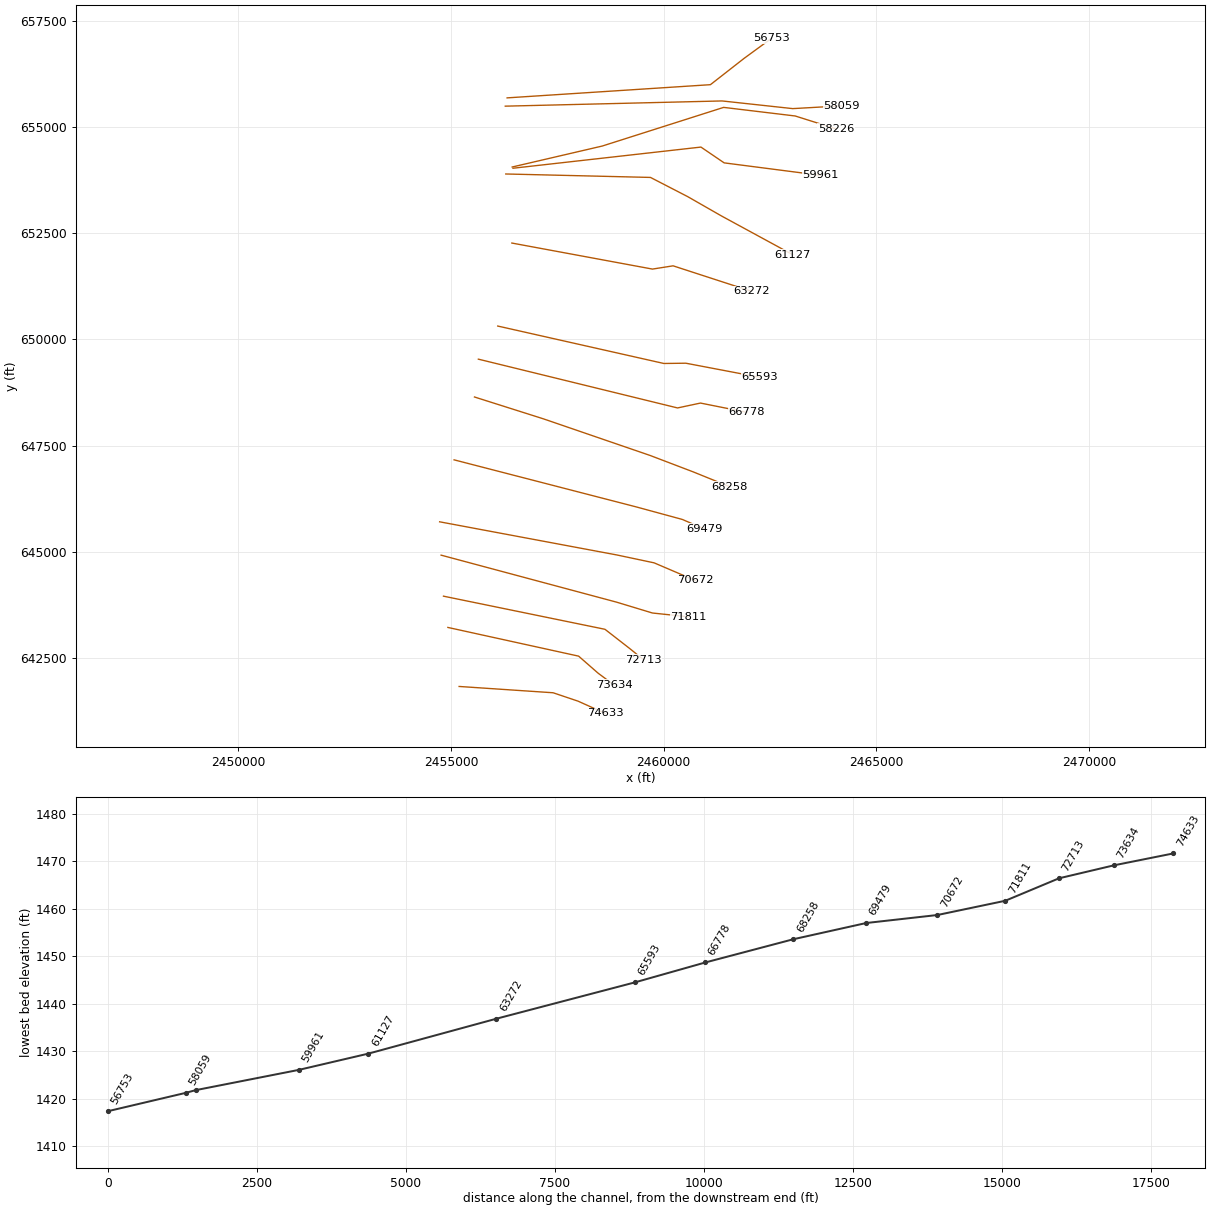
HEC-RAS study SBPOTOMC.prj: SBPOTOMC

--- SBPOTOMC.g01 (geometry) --- (continued)

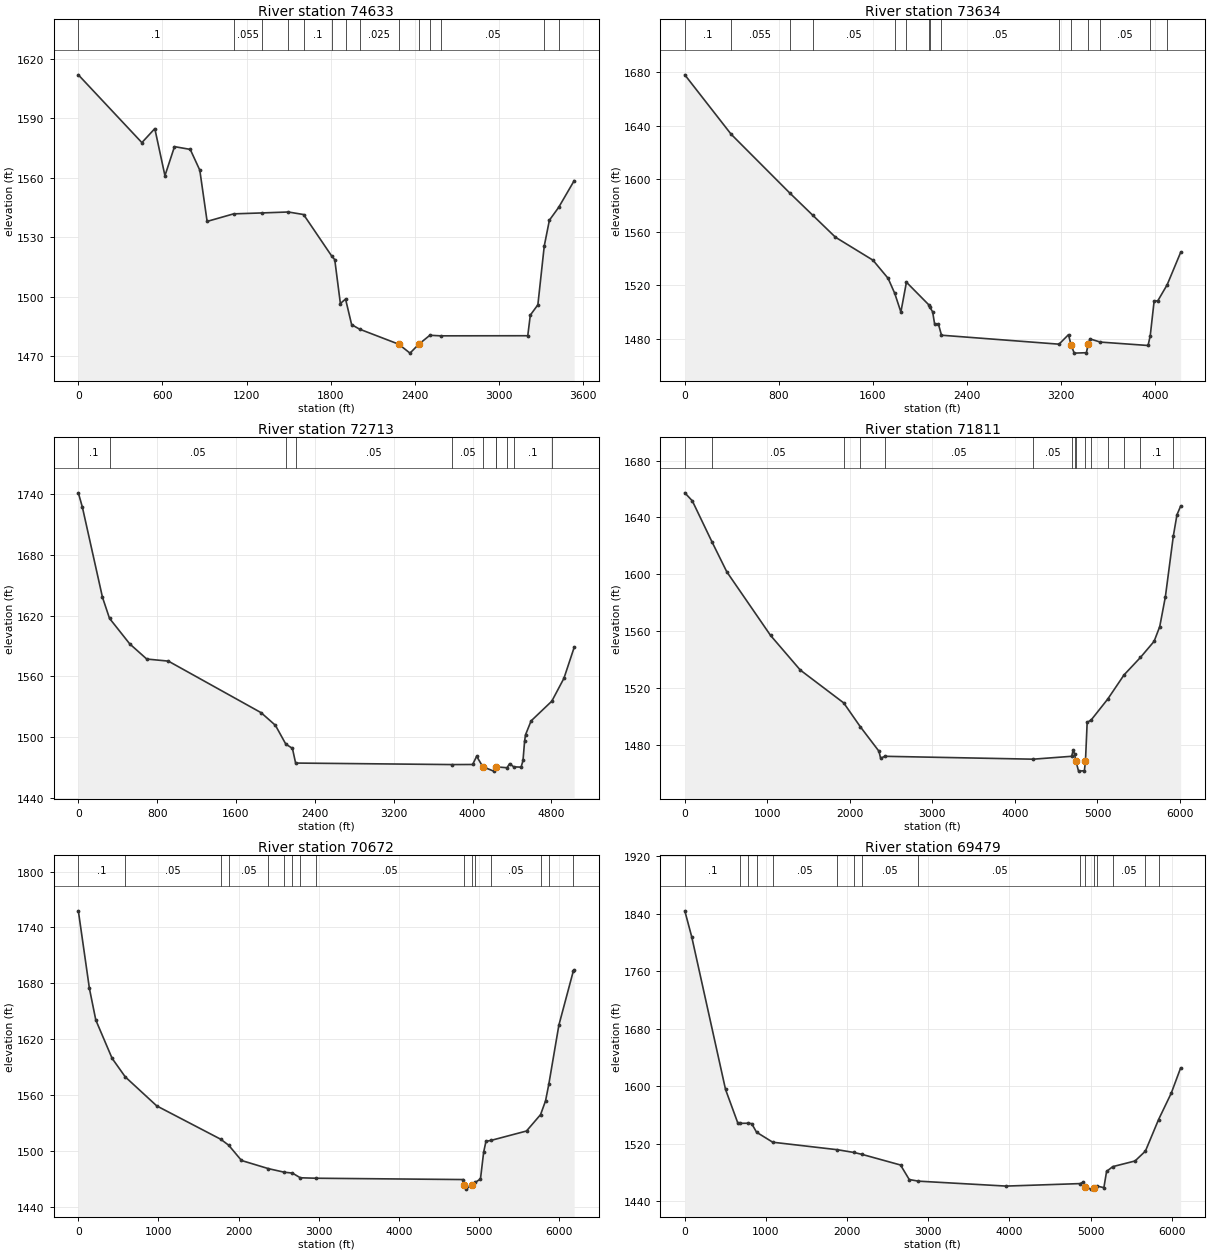
Type RM Length L Ch R = 1 ,74633   ,984.5,999,832.3
XS GIS Cut Line= 4
2455190.65434718641830.9027759732457401.07534602641682.571670264
2457988.36819251641484.6795154512458626.72998221641197.416710109
#Sta/Elev= 30
       0 1611.79   453.1 1577.65   545.3 1584.71   617.5    1561   685.6 1575.63
   797.9 1574.24     866 1563.79   918.2 1537.98  1107.2 1541.78 1306.711542.241
 1496.78 1542.72 1605.971541.439 1805.471520.643  1828.2  1518.7  1868.3 1496.63
 1905.231498.877  1948.5    1486 2004.981483.727 2284.07 1476.15  2364.7 1471.65
  2427.3 1476.12  2506.41480.646 2582.861480.356  3204.3 1480.41  3222.5 1490.79
  3276.4 1495.98 3321.981525.616  3358.6 1538.59 3424.811545.069  3535.1 1558.48
#Mann= 14 ,-1 , 0
       0      .1       0  1107.2    .055       0 1306.71      .1       0
 1496.78     .05       0 1605.97      .1       0 1805.47    .055       0
 1905.23     .05       0 2004.98    .025       0 2284.07    .045       0
  2427.3      .1       0  2506.4     .05       0 2582.86     .05       0
 3321.98     .05       0 3424.81     .05       0
Bank Sta=2284.07,2427.3
XS Rating Curve= 0 ,0
Exp/Cntr(USF)=0,0
Exp/Cntr=0.3,0.1

Type RM Length L Ch R = 1 ,73634   ,737.7,920.9,913.8
XS GIS Cut Line= 4
2454926.76545809643219.7916657032458001.13542832642544.360086337
2458460.75591688642142.1921588182458831.00575489641867.696589276
#Sta/Elev= 30
       0 1678.09  393.931633.522  891.281589.526 1090.221572.554  1281.8 1556.18
  1601.3 1538.92    1730 1525.31 1786.511514.027  1838.8 1500.01 1885.98 1522.39
 2074.031505.603 2084.921503.684  2109.1 1500.12  2125.5  1491.2  2158.3 1490.91
 2184.391482.594 3184.641475.859  3265.3 1483.01  3285.9 1475.57  3313.9 1469.14
  3417.2 1469.45  3433.3 1475.94  3447.5 1479.84 3535.881477.438  3942.3 1474.87
 3960.73 1482.22  3993.8 1508.19  4025.3 1508.46 4104.951520.501  4219.3 1544.74
#Mann= 15 ,-1 , 0
       0      .1       0  393.93    .055       0  891.28      .1       0
 1090.22     .05       0 1786.51      .1       0 1885.98    .055       0
 2074.03     .05       0 2084.92     .06       0 2184.39     .05       0
 3184.64     .05       0  3285.9    .045       0  3433.3      .1       0
 3535.88     .05       0 3960.73      .1       0 4104.95     .05       0
Bank Sta=3285.9,3433.3
XS Rating Curve= 0 ,0
Exp/Cntr(USF)=0,0
Exp/Cntr=0.3,0.1

Type RM Length L Ch R = 1 ,72713   ,742.5,902,909.6
XS GIS Cut Line= 4
2454822.59879141643955.902777255 2458620.3463643643176.338258103
2459194.87197503642729.4850053192459526.82010566 642461.37305367
#Sta/Elev= 30
       0 1741.34      41  1727.2   244.9 1638.17  316.281617.356   522.2 1592.05
   694.3 1577.14   913.5 1575.09  1854.2 1524.18  1999.9 1511.68 2105.521493.074
  2172.5 1488.91 2204.921474.385 3795.351472.884  4001.6 1472.97  4042.1 1481.12
 4104.131470.795  4214.4 1466.41  4234.7 1470.22 4236.791470.643 4349.981469.759
  4376.6 1473.82 4417.951470.646  4493.1 1470.35  4512.5 1476.92  4528.6  1496.1
  4538.1 1502.35  4594.5 1516.03 4804.781535.524  4927.9 1558.16  5031.5  1588.6
#Mann= 11 ,-1 , 0
       0      .1       0  316.28     .05       0 2105.52     .06       0
 2204.92     .05       0 3795.35     .05       0 4104.13    .045       0
  4234.7     .06       0 4236.79    .055       0 4349.98     .06       0
 4417.95      .1       0 4804.78      .1       0
Bank Sta=4104.13,4234.7
XS Rating Curve= 0 ,0
Exp/Cntr(USF)=0,0
Exp/Cntr=0.3,0.1

Type RM Length L Ch R = 1 ,71811   ,1014.6,1139.8,1143.8
XS GIS Cut Line= 4
2454767.04323581644921.1805556272458894.84193386643814.700047776
2459737.47949623643559.3553318982460586.50067651643469.984681353
#Sta/Elev= 30
       0  1657.3    90.8 1651.68  328.381622.948   509.1 1601.75  1039.1 1557.06
  1399.4 1532.72  1925.61509.623 2125.251492.992  2351.9 1475.72  2372.6 1470.78
 2424.731472.103  4221.61470.075 4687.241472.108  4706.3  1476.5 4722.441473.697
 4738.07  1468.9  4770.8 1461.68  4841.9 1461.97 4854.96 1469.01  4875.3 1495.96
 4922.851497.573 5123.271512.231 5322.43 1529.34 5521.381541.627  5686.2  1552.9
  5754.6 1563.26  5822.9 1584.19 5919.26 1626.92  5963.4 1641.88  6007.7 1647.93
#Mann= 15 ,-1 , 0
       0      .1       0  328.38     .05       0  1925.6     .06       0
 2125.25     .05       0 2424.73     .05       0  4221.6     .05       0
 4687.24    .055       0 4722.44      .1       0 4738.07    .045       0
 4854.96      .1       0 4922.85      .1       0 5123.27      .1       0
 5322.43     .06       0 5521.38      .1       0 5919.26      .1       0
Bank Sta=4738.07,4854.96
XS Rating Curve= 0 ,0
Exp/Cntr(USF)=0,0
Exp/Cntr=0.3,0.1

Type RM Length L Ch R = 1 ,70672   ,1262.6,1192.2,1168.1
XS GIS Cut Line= 4
2454732.32101357645705.9027783422458901.22555177644925.449561805
2459775.78120363644740.3246427922460746.09112394644325.389479518
#Sta/Elev= 30
       0 1757.92   138.3 1674.46   218.1  1640.5   421.6 1599.33  586.061579.357
   979.1 1548.17  1778.21512.301 1877.551505.878  2037.2 1489.47 2374.281480.688
 2572.97 1476.84 2672.311475.948 2771.661470.882 2970.351470.395  4807.1 1468.97
  4818.4 1463.49  4838.7 1458.68  4919.6 1463.42 4957.871466.022  5020.9  1469.6
  5060.6  1498.4  5089.2 1509.99 5157.351511.174  5595.7 1521.18 5771.341538.815
  5833.4 1553.61 5873.671571.244  5999.9 1635.04 6180.671693.343  6190.6  1694.4
#Mann= 16 ,-1 , 0
       0      .1       0  586.06     .05       0  1778.2     .06       0
 1877.55     .05       0 2374.28     .05       0 2572.97     .05       0
 2672.31     .05       0 2771.66     .05       0 2970.35     .05       0
  4818.4    .045       0  4919.6     .05       0 4957.87      .1       0
 5157.35     .05       0 5771.34     .06       0 5873.67      .1       0
 6180.67     .05       0
Bank Sta=4818.4,4919.6
XS Rating Curve= 0 ,0
Exp/Cntr(USF)=0,0
Exp/Cntr=0.3,0.1

Type RM Length L Ch R = 1 ,69479   ,1336.8,1221.3,1199.6
XS GIS Cut Line= 4
2455072.59879154647164.2361125652459360.84604032646055.349929541
 2460439.6774649645761.7035062912460956.75051452645538.276879892
#Sta/Elev= 30
       0 1843.96    84.8 1808.08   502.1  1595.6     655 1548.43  684.931548.502
  784.67 1548.63   824.4 1548.03  884.411536.117 1083.891522.223 1881.81 1511.78
 2081.281508.025 2181.021505.423  2658.8 1490.53  2766.2 1470.34  2879.21468.089
  3960.3 1461.23 4874.561464.701  4909.8 1466.83  4932.6 1459.42  5011.6    1457
  5044.8 1459.12 5074.291461.387    5165 1459.07  5198.2 1481.65 5274.021488.271
  5548.8 1496.14 5676.721509.873  5838.31553.579  5995.2 1590.46  6110.7 1625.48
#Mann= 16 ,-1 , 0
       0      .1       0  684.93     .05       0  784.67     .06       0
  884.41     .05       0 1083.89     .05       0 1881.81     .05       0
 2081.28     .06       0 2181.02     .05       0  2879.2     .05       0
 4874.56    .025       0  4932.6    .045       0  5044.8     .05       0
 5074.29      .1       0 5274.02     .05       0 5676.72     .06       0
  5838.3      .1       0
Bank Sta=4932.6,5044.8
XS Rating Curve= 0 ,0
Exp/Cntr(USF)=0,0
Exp/Cntr=0.3,0.1

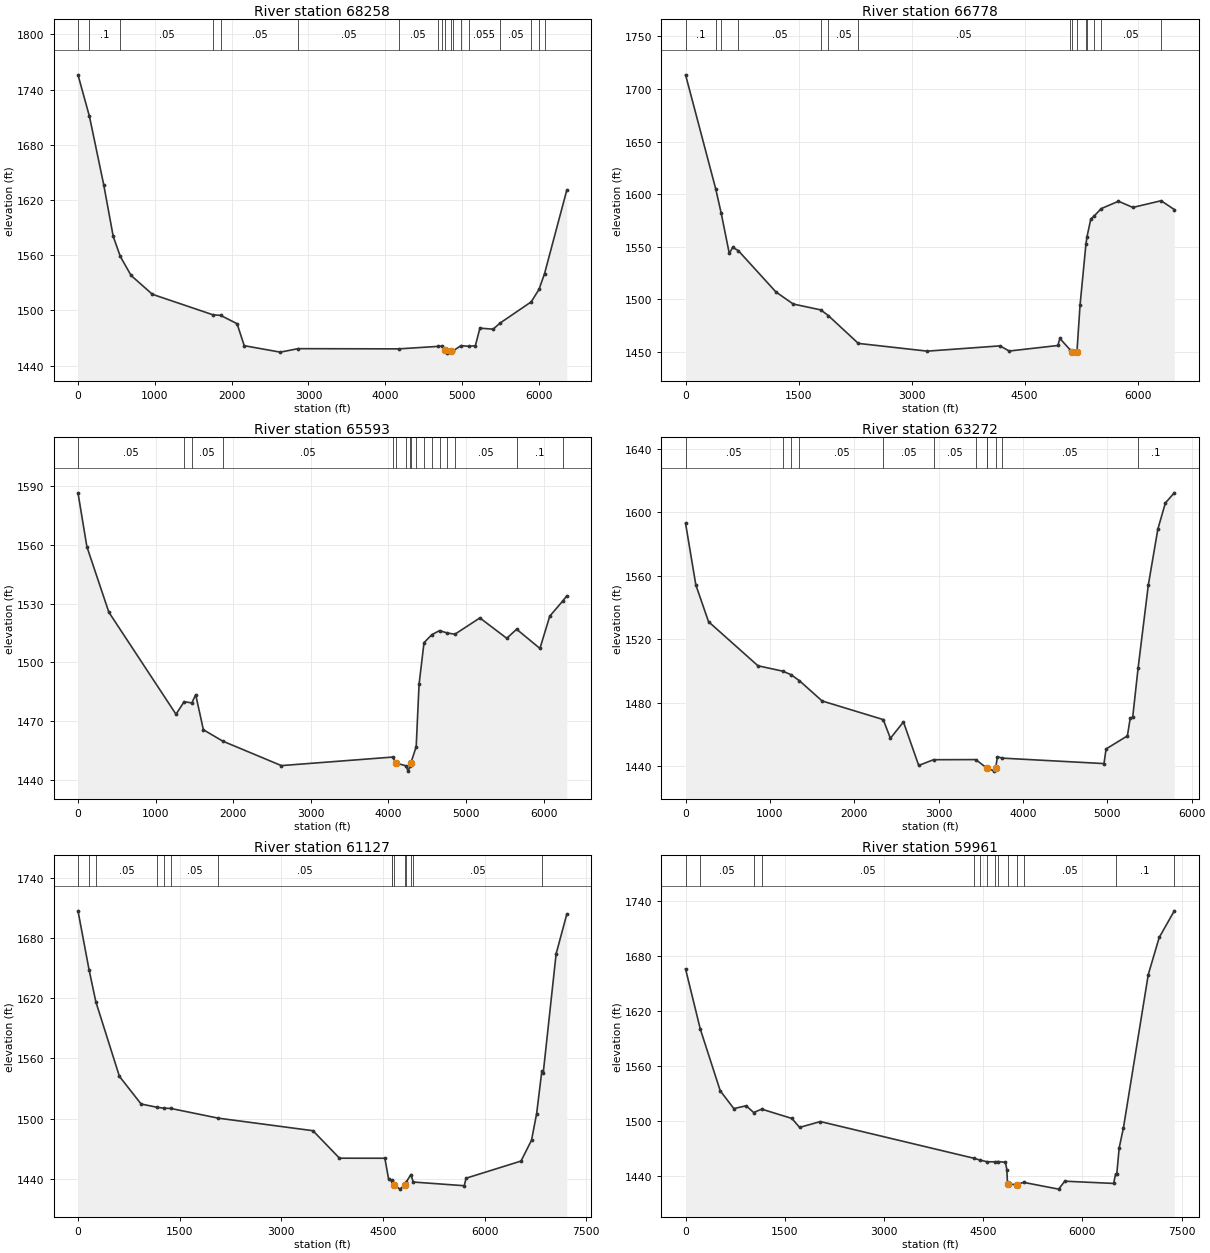
Type RM Length L Ch R = 1 ,68258   ,1146.1,1480.2,1516.6
XS GIS Cut Line= 5
2455551.76545848648643.4027801312457174.35631143648128.829810515
2459680.02693518647268.2373299152460701.40579864646878.836638212
2461550.42697892646534.121271789
#Sta/Elev= 30
       0 1756.11   149.41710.856   334.6 1636.82   458.5 1580.55  550.951558.676
   691.3 1537.99   968.6 1517.54 1755.82 1495.29 1856.591494.624  2070.6 1485.58
  2163.8 1461.68  2633.1 1454.65 2864.281458.444 4174.281458.213  4680.21460.889
 4733.321461.302    4774 1456.55  4807.2 1453.59  4859.9 1455.67 4883.011456.082
 4984.421461.725 5085.831461.021  5172.1 1461.59  5231.2 1480.75  5403.3 1479.63
 5491.681486.139 5899.211509.337 6001.091522.993 6072.961540.137    6361 1630.45
#Mann= 18 ,-1 , 0
       0      .1       0   149.4      .1       0  550.95     .05       0
 1755.82     .06       0 1856.59     .05       0 2864.28     .05       0
 4174.28     .05       0  4680.2    .025       0 4733.32     .05       0
    4774    .045       0  4859.9     .05       0 4883.01     .12       0
 4984.42      .1       0 5085.83    .055       0 5491.68     .05       0
 5899.21    .055       0 6001.09     .12       0 6072.96      .1       0
Bank Sta=4774,4859.9
XS Rating Curve= 0 ,0
Exp/Cntr(USF)=0,0
Exp/Cntr=0.3,0.1

Type RM Length L Ch R = 1 ,66778   ,923.4,1184.5,1117
XS GIS Cut Line= 4
2455643.13234217649533.8623660472460327.12476928648385.825006461
2460866.70232828 648500.628742422461957.33781989648282.501644098
#Sta/Elev= 30
       0 1713.45  400.021604.994  472.58 1581.97   580.3 1543.54   625.6 1549.26
  698.911546.306  1199.5 1506.87  1428.7 1495.41 1794.841489.807 1894.471484.417
 2292.991457.943  3207.8 1450.58  4173.1 1455.59  4295.1 1450.69  4941.2 1455.95
  4968.2 1462.66 5100.671452.091  5123.3 1450.04    5157 1448.69  5194.8 1450.11
  5235.3 1494.03 5313.751552.255 5327.781559.336  5378.4 1576.31  5417.21578.698
 5516.58 1586.17  5745.5 1593.18  5936.7  1587.3 6311.631593.676  6486.5 1585.31
#Mann= 15 ,-1 , 0
       0      .1       0  400.02     .05       0  472.58      .1       0
  698.91     .05       0 1794.84     .06       0 1894.47     .05       0
 2292.99     .05       0 5100.67      .1       0  5123.3    .045       0
  5194.8      .1       0 5313.75      .1       0 5327.78      .1       0
  5417.2      .1       0 5516.58     .05       0 6311.63      .1       0
Bank Sta=5123.3,5194.8
XS Rating Curve= 0 ,0
Exp/Cntr(USF)=0,0
Exp/Cntr=0.3,0.1

Type RM Length L Ch R = 1 ,65593   ,2101.9,2321,2187.7
BEGIN DESCRIPTION:
Mannings N in channel placed 0.1 because of island in the channel
END DESCRIPTION:
XS GIS Cut Line= 4
2456098.81729508650313.2230666592460005.59144789649432.283796908
2460522.66449753649438.6674148052462265.39218334649106.719284174
#Sta/Elev= 30
       0 1586.53   114.7 1559.05   397.7  1525.6  1262.9 1473.51 1367.311479.916
 1466.811479.298  1516.3 1483.54  1615.5 1465.61 1864.821459.804  2620.1 1447.31
 4054.481451.664  4095.5 1448.64  4222.1 1447.24    4254 1444.49    4278 1447.36
  4286.9 1448.47 4356.941456.943    4394  1488.8 4457.761510.055 4558.051514.117
  4657.41516.205 4756.751514.993 4856.11 1514.38  5177.6 1522.68  5523.8 1512.29
 5650.931516.904  5951.3 1507.11  6077.5 1523.58 6247.04 1531.43    6296 1533.92
#Mann= 17 ,-1 , 0
       0     .05       0 1367.31     .06       0 1466.81     .05       0
 1864.82     .05       0 4054.48    .025       0  4095.5    .045       0
  4222.1      .1       0    4278    .045       0  4286.9     .12       0
 4356.94      .1       0 4457.76     .05       0 4558.05      .1       0
  4657.4     .05       0 4756.75      .1       0 4856.11     .05       0
 5650.93      .1       0 6247.04      .1       0
Bank Sta=4095.5,4286.9
XS Rating Curve= 0 ,0
Exp/Cntr(USF)=0,0
Exp/Cntr=0.3,0.1

Type RM Length L Ch R = 1 ,63272   ,2165.3,2145.3,1505.7
XS GIS Cut Line= 4
2456430.76542571652266.6101430632459737.47949623651653.782824976
2460222.63445638651730.3862397372462067.50002854651130.326157442
#Sta/Elev= 30
       0 1592.92     122  1554.1   272.5 1530.96   858.4 1503.21 1151.391499.825
 1250.731497.593 1350.071493.792  1619.1 1481.04 2343.491469.318  2428.6 1457.53
  2583.2 1467.83  2764.3 1440.42 2939.541444.036 3440.071444.119 3574.391438.687
  3579.6 1438.68  3661.4 1436.85  3675.8 1438.69  3697.3 1445.91 3753.681445.041
  4960.6  1441.6  4985.8 1450.83  5238.2 1459.04  5271.8 1470.21  5301.2 1470.82
 5365.591501.944  5486.3 1554.06  5599.5 1589.31  5688.2 1605.73  5794.2 1612.14
#Mann= 12 ,-1 , 0
       0     .05       0 1151.39    .055       0 1250.73     .05       0
 1350.07     .05       0 2343.49     .05       0 2939.54     .05       0
 3440.07      .1       0 3574.39    .025       0  3579.6    .045       0
  3675.8    .055       0 3753.68     .05       0 5365.59      .1       0
Bank Sta=3579.6,3675.8
XS Rating Curve= 0 ,0
Exp/Cntr(USF)=0,0
Exp/Cntr=0.3,0.1

Type RM Length L Ch R = 1 ,61127   ,1167.3,1166.2,1375.3
XS GIS Cut Line= 5
 2456287.6170302653892.0007420632459691.26286565653810.924353123
2460567.34982285  653358.20880342461358.91844201652904.971932754
2463034.87641117651993.264600256
#Sta/Elev= 30
       0 1707.48  163.631648.592  263.88 1616.58   611.3 1542.17   931.4 1514.52
 1166.161511.273 1266.411510.348 1366.66 1510.14 2068.431500.414  3467.1 1487.86
  3858.4  1460.4  4527.6 1460.36  4582.6 1439.81 4627.821438.136 4639.071437.621
 4666.72 1433.71  4749.6 1429.51  4823.6 1433.43    48401436.213 4911.661444.069
 4946.091436.608  5698.9 1432.91  5726.2 1440.43  6536.7 1457.54  6691.5 1478.37
  6767.1 1504.91 6843.431547.208  6864.6 1545.64  7054.7 1664.55  7210.8 1703.82
#Mann= 15 ,-1 , 0
       0      .1       0  163.63      .1       0  263.88     .05       0
 1166.16     .02       0 1266.41    .035       0 1366.66     .05       0
 2068.43     .05       0 4627.82    .025       0 4639.07      .1       0
 4666.72    .045       0  4823.6    .025       0    4840      .1       0
 4911.66      .1       0 4946.09     .05       0 6843.43      .1       0
Bank Sta=4666.72,4823.6
XS Rating Curve= 0 ,0
Exp/Cntr(USF)=0,0
Exp/Cntr=0.3,0.1

Type RM Length L Ch R = 1 ,59961   ,1598.2,1734.7,1378
XS GIS Cut Line= 4
2456457.51444175654027.1829953852460877.70445258654525.343944728
2461423.30930186654153.7000618852463684.80186555653861.129345604
#Sta/Elev= 30
       0 1666.01  222.91 1600.47   524.5 1533.24   729.8 1513.89   916.1 1516.93
 1029.761509.591 1151.121513.275  1607.3 1503.12  1724.1 1493.37  2038.7 1499.72
 4365.211459.637 4451.611457.722 4561.24 1455.91 4670.881455.872 4726.16 1456.14
  4836.2 1455.32  4856.6 1447.48  4867.8 1431.58 5006.82 1431.04 5109.291433.464
  5640.2 1426.09  5732.9 1434.74    6471 1432.31 6500.431442.128  6519.4 1442.94
  6555.7 1471.13  6620.3 1493.08  6995.4    1660  7160.7 1700.37  7388.6 1729.41
#Mann= 14 ,-1 , 0
       0      .1       0  222.91     .05       0 1029.76     .06       0
 1151.12     .05       0 4365.21     .05       0 4451.61     .12       0
 4561.24     .05       0 4670.88     .12       0 4726.16     .05       0
  4867.8    .045       0 5006.82     .12       0 5109.29     .05       0
 6500.43      .1       0  7388.6     .05       0
Bank Sta=4867.8,5006.82
XS Rating Curve= 0 ,0
Exp/Cntr(USF)=0,0
Exp/Cntr=0.5,0.3

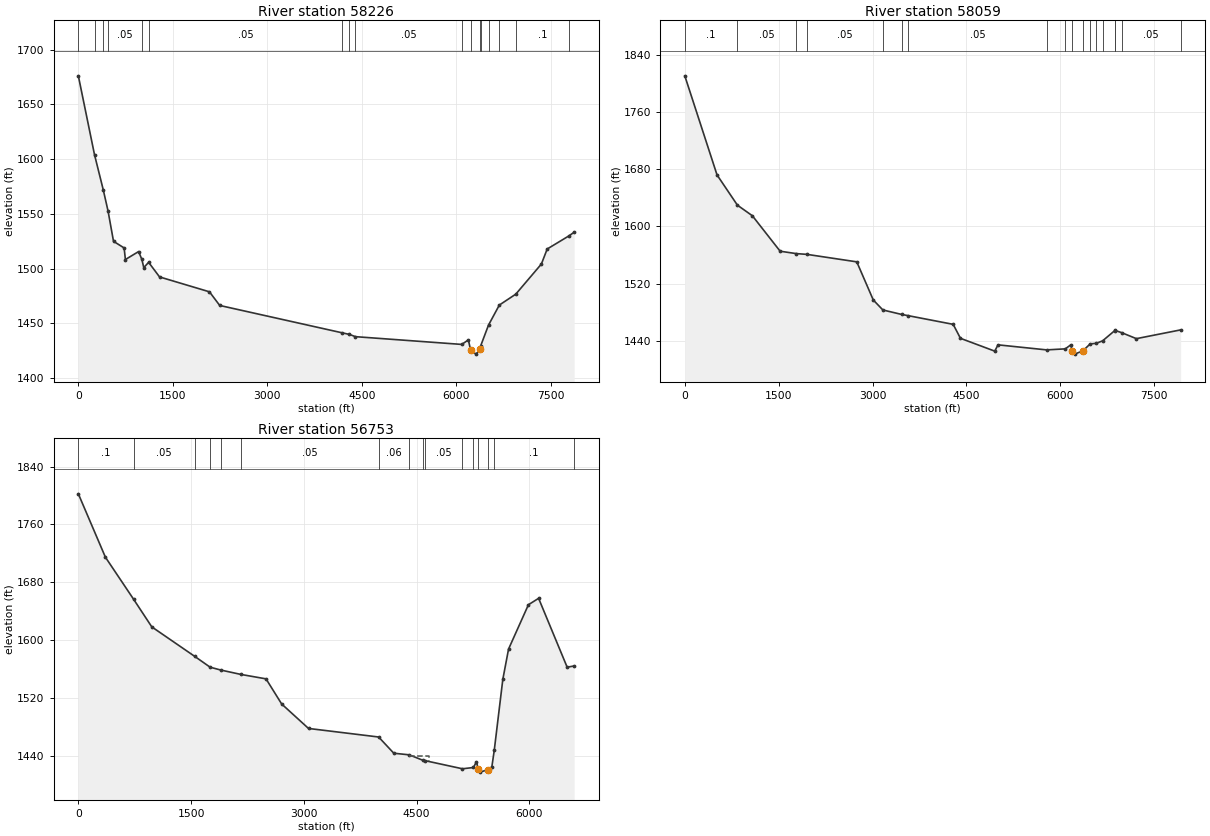
Type RM Length L Ch R = 1 ,58226   ,163.4,167.1,160.7
XS GIS Cut Line= 5
2456438.65961003654056.1606545842458557.70254034654549.884345434
2461411.30671253655459.2870712422463094.25605394655257.044231931
2464054.90954067654953.679972964
#Sta/Elev= 30
       01675.974  257.181603.863  395.331571.973  471.911552.506 558.658 1524.84
 727.0511518.778 747.587 1508.21 957.0511515.484 1008.721508.3241039.1931500.824
 1116.091505.6461289.7291492.3142082.4061478.7082244.9821466.261 4194.541441.206
 4305.891439.798 4400.291437.761 6088.511430.6816193.552 1434.846227.4721425.823
6314.4151421.8126382.9041426.148 6386.711429.033 6513.241448.322 6684.911466.615
 6946.251476.5797352.9641504.1037445.2481517.829 7787.221529.696 7873.281533.134
#Mann= 17 ,-1 , 0
       0      .1       0  257.18     .05       0  395.33      .1       0
  471.91     .05       0 1008.72     .06       0 1116.09     .05       0
 4194.54     .05       0 4305.89     .05       0 4400.29     .05       0
 6088.51    .025       06227.472    .045       06382.904      .1       0
 6386.71      .1       0 6513.24     .02       0 6684.91     .05       0
 6946.25      .1       0 7787.22     .05       0
#XS Ineff= 2 , 0
            6197 1425.99    6412         1426.13
Permanent Ineff=
       F       F
Bank Sta=6227.472,6382.904
XS Rating Curve= 0 ,0
Exp/Cntr(USF)=0,0
Exp/Cntr=0.5,0.3

Type RM Length L Ch R = 1 ,58059   ,731.1,1305.7,1403.5
XS GIS Cut Line= 4
2456275.78318573 655488.17890543 2461375.1919198655610.969200726
2463036.47238557655430.3952370552464184.92279451655495.401863976
#Sta/Elev= 30
       0 1810.84   515.1 1672.09  840.821629.758  1079.3 1614.97  1523.4 1565.31
  1779.5 1561.98 1952.231560.886  2747.8 1550.42  3011.8    1497 3164.671483.074
 3467.781476.738 3568.821475.099  4288.2 1462.94  4404.2 1443.37  4952.4 1425.43
  5004.4 1434.23  5780.81427.171 6079.161428.615  6166.7 1434.21  6189.3  1425.9
    6227 1421.24  6359.8 1425.74 6476.981435.571 6576.431436.404 6675.881439.864
 6870.011454.189 6877.121454.404 6978.831451.334  7215.5 1442.91  7922.2 1455.16
#Mann= 18 ,-1 , 0
       0      .1       0  840.82     .05       0  1779.5    .035       0
 1952.23     .05       0 3164.67     .06       0 3467.78    .055       0
 3568.82     .05       0  5780.8     .06       0 6079.16      .1       0
  6189.3    .045       0  6359.8      .1       0 6476.98     .05       0
 6576.43    .035       0 6675.88     .06       0 6870.01     .05       0
 6877.12    .035       0 6978.83     .05       0  7922.2     .05       0
Bank Sta=6189.3,6359.8
XS Rating Curve= 0 ,0
Exp/Cntr(USF)=0,0
Exp/Cntr=0.5,0.3

Type RM Length L Ch R = 1 ,56753   ,1966.8,1362,1330.9
XS GIS Cut Line= 4
2456319.12093702655683.1987861942461100.71949502655993.786003708
2461895.24493517656614.9604387352462538.08824584657084.452744279
#Sta/Elev= 30
       0  1802.3     360 1714.69  734.211656.635   977.3 1618.27 1549.381577.406
 1753.181562.512  1891.6 1558.67 2160.761552.547  2496.9 1546.38  2705.3 1511.59
  3062.1 1477.79 3994.911465.958  4196.8 1443.52 4402.491441.295  4588.81433.558
 4606.291433.401  5110.61422.006 5256.851423.786  5295.4 1431.64  5322.3 1421.47
  5343.9 1417.38  5449.2 1420.78  5501.4  1424.7 5533.431447.658  5647.2 1545.69
  5723.4 1587.56  5987.8 1648.91  6123.3 1657.75  6502.9 1562.56  6596.2 1564.18
#Mann= 16 ,-1 , 0
       0      .1       0  734.21     .05       0 1549.38    .055       0
 1753.18    .035       0  1891.6     .06       0 2160.76     .05       0
 3994.91     .06       0 4402.49     .05       0  4588.8     .06       0
 4606.29     .05       0  5110.6     .06       0 5256.85      .1       0
  5322.3    .045       0  5449.2     .12       0 5533.43      .1       0
  6596.2      .1       0
#XS Ineff= 1 ,-1
 4401.87 4663.55 1439.79
Permanent Ineff=
       F
Bank Sta=5322.3,5449.2
XS Rating Curve= 0 ,0
Exp/Cntr(USF)=0,0
Exp/Cntr=0.3,0.1