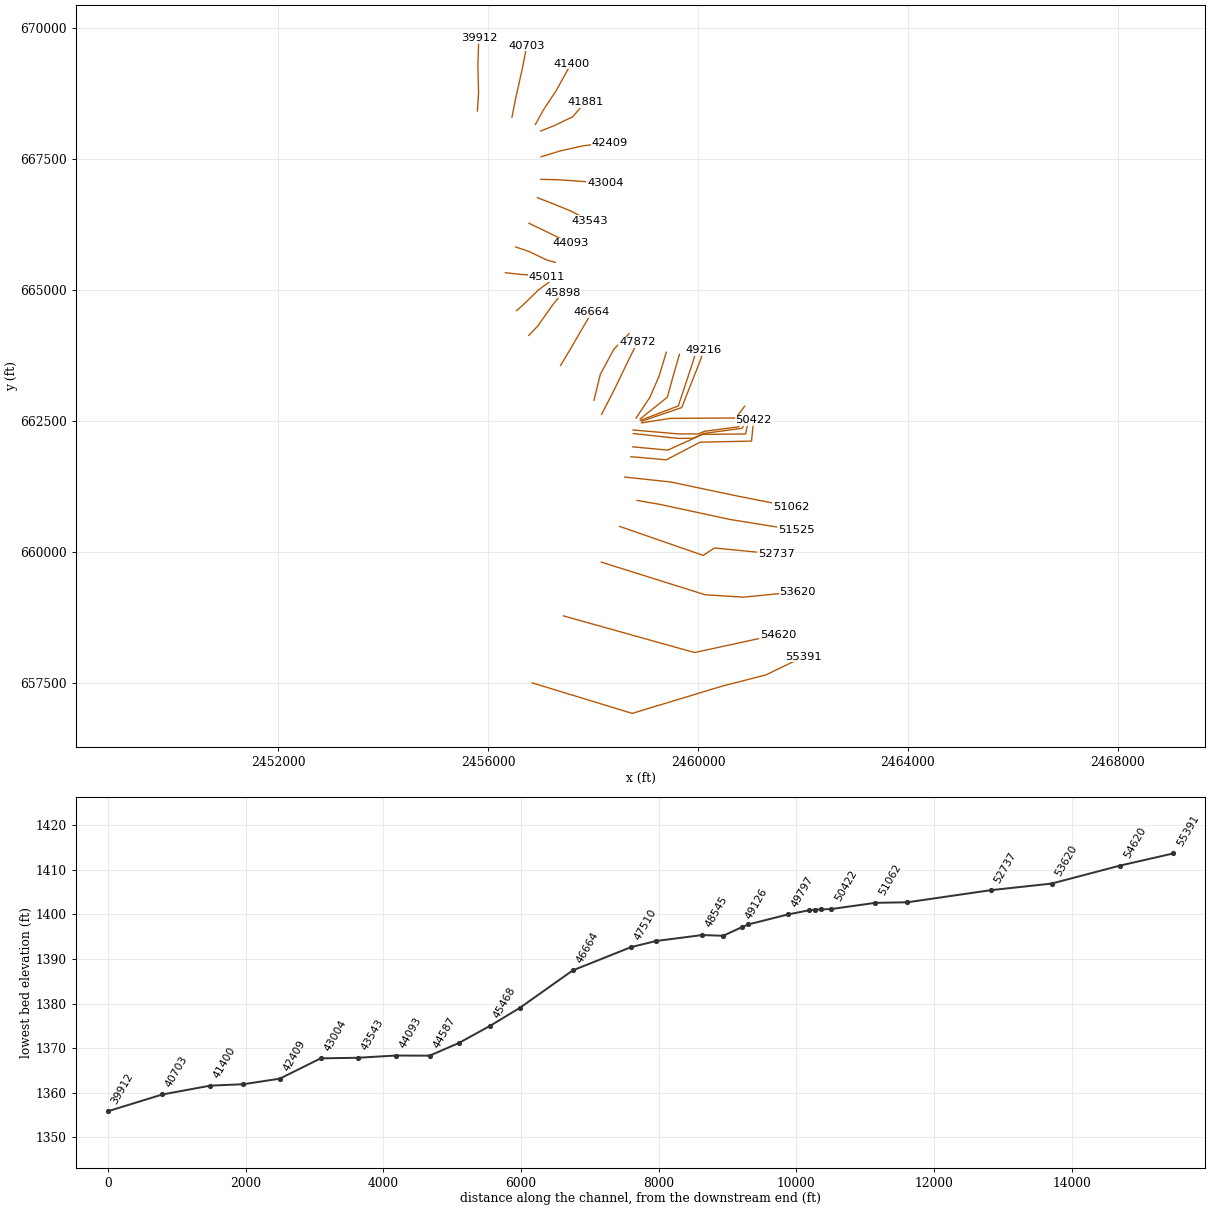
HEC-RAS study SBPOTOMC.prj: SBPOTOMC

--- SBPOTOMC.g01 (geometry) --- (continued)

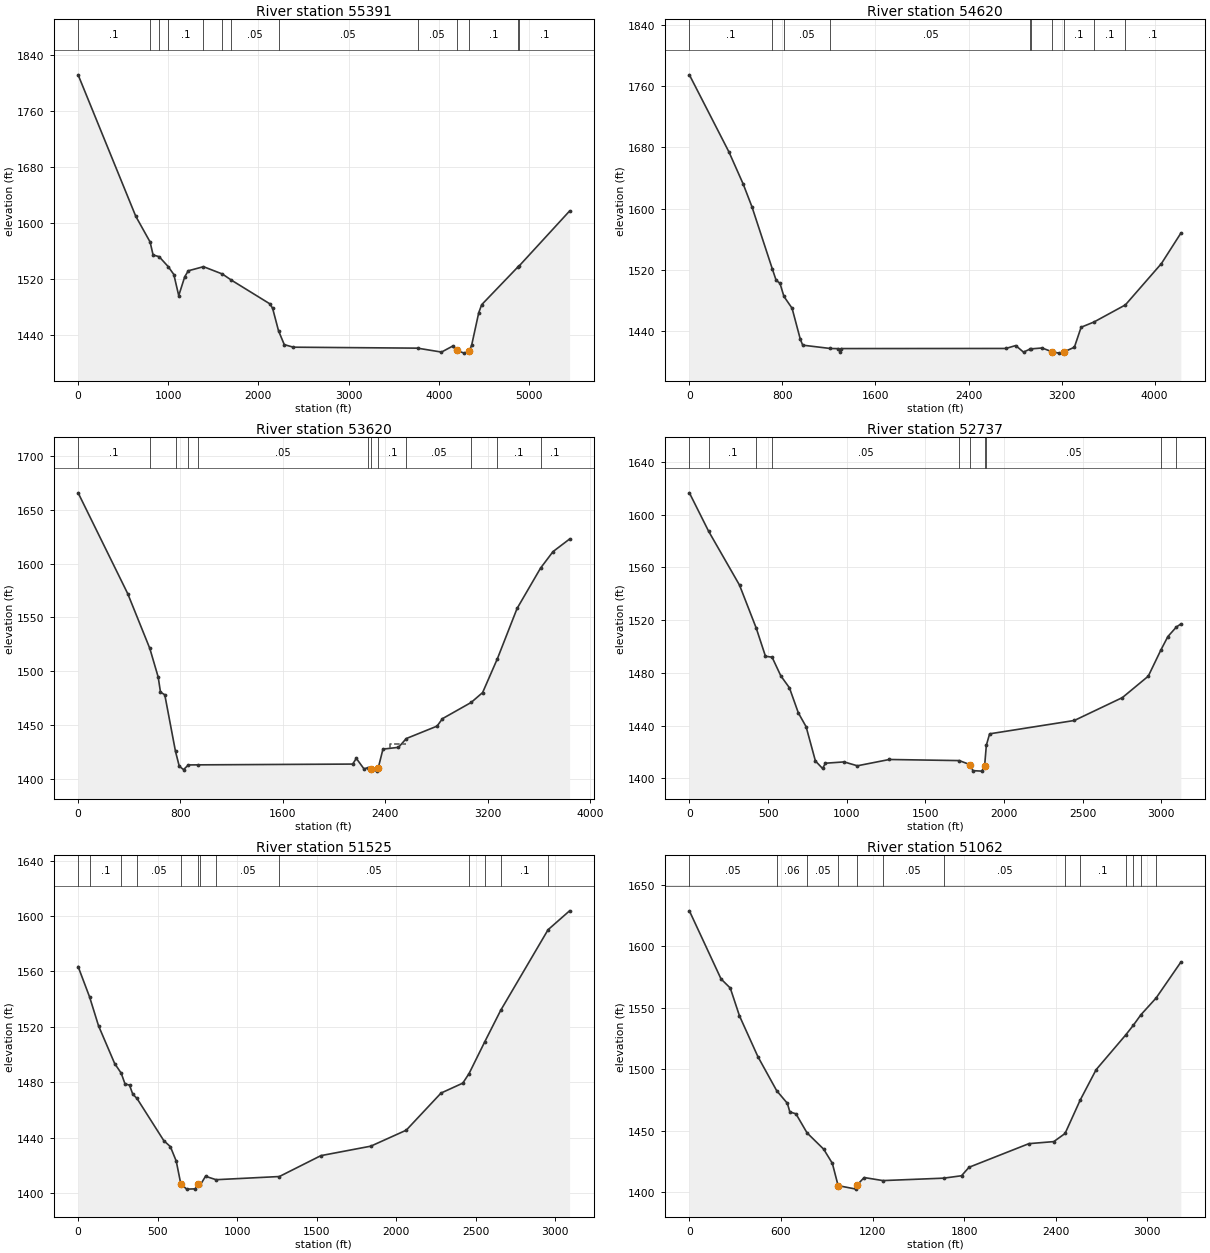
Type RM Length L Ch R = 1 ,55391   ,1076.9,771.8,770.2
XS GIS Cut Line= 5
2456839.23266634657501.4117542982458745.09598331656919.745928684
2460456.43658221657437.971911256 2461294.7487957657653.214236342
2462019.77557493658004.399082534
#Sta/Elev= 30
       0 1810.99   639.5 1609.09  798.451572.382   831.7 1553.85  898.691551.411
  998.921537.294  1061.8 1525.96  1116.1  1495.8    1183 1522.83  1222.4 1531.27
 1390.791537.122 1600.331526.652 1700.561517.904  2128.1 1483.99  2157.4 1477.78
 2223.261445.574  2286.9 1425.86  2387.2  1422.2 3765.211420.827  4030.9 1415.21
  4154.7 1423.75  4200.7 1417.48  4282.8 1413.72  4338.7 1417.04    4365 1424.72
  4443.9 1471.34  4476.7 1482.86 4879.981536.917 4891.641538.073  5451.8 1616.59
#Mann= 13 ,-1 , 0
       0      .1       0  798.45     .06       0  898.69    .055       0
  998.92      .1       0 1390.79     .05       0 1600.33      .1       0
 1700.56     .05       0 2223.26     .05       0 3765.21     .05       0
  4200.7    .045       0  4338.7      .1       0 4879.98      .1       0
 4891.64      .1       0
Bank Sta=4200.7,4338.7
XS Rating Curve= 0 ,0
Exp/Cntr(USF)=0,0
Exp/Cntr=0.3,0.1

Type RM Length L Ch R = 1 ,54620   ,1227.8,999.5,1024.6
XS GIS Cut Line= 4
2457432.50806046658780.2682965992459934.70806687658080.352210889
2461142.06331472 658342.820743032461527.01716186658412.812351601
#Sta/Elev= 30
       0 1774.89   340.5 1673.95   462.6 1632.09   538.1 1602.29  712.581521.357
   745.8 1506.23     779  1502.3  812.521485.225   882.9 1469.68   953.5 1429.27
   974.3 1421.42 1212.281417.056  1278.5 1416.88  1294.1 1412.98  1306.5 1416.96
  2721.1  1417.1  2805.5  1420.9  2872.5 1412.32 2932.53 1416.58 2935.371416.527
  3032.2 1417.72  3114.9 1412.96  3175.1    1411  3220.5 1412.64  3309.9 1418.71
  3367.8 1444.85  3477.41451.628 3748.421474.075  4058.1 1528.11  4225.1 1567.82
#Mann= 10 ,-1 , 0
       0      .1       0  712.58     .06       0  812.52     .05       0
 1212.28     .05       0 2932.53     .05       0 2935.37      .1       0
  3114.9    .045       0  3220.5      .1       0  3477.4      .1       0
 3748.42      .1       0
Bank Sta=3114.9,3220.5
XS Rating Curve= 0 ,0
Exp/Cntr(USF)=0,0
Exp/Cntr=0.3,0.1

Type RM Length L Ch R = 1 ,53620   ,759.9,883.5,915.3
XS GIS Cut Line= 4
2458156.74226682659805.6374871962460139.23736629659182.567598791
2460864.26414553659137.2534250892461895.16159725659239.210315919
#Sta/Elev= 30
       0 1665.74   387.8 1571.94  560.361520.999   625.9 1494.34   643.6 1480.42
   677.2 1477.96  761.061425.204   790.4 1411.51   823.9 1408.35  861.411412.696
  935.471412.771  2145.7  1413.5  2173.8 1418.83  2233.9 1409.03 2265.291410.208
    2290 1409.37  2334.1 1406.94  2345.1 1409.82  2382.2 1427.39  2503.6 1429.07
 2564.691437.248  2804.7 1448.79  2847.2 1455.73 3071.341470.797  3160.8 1479.98
 3276.851511.611  3430.1 1558.19 3613.651595.729    3711 1611.08  3840.5 1622.76
#Mann= 12 ,-1 , 0
       0      .1       0  560.36     .06       0  761.06     .05       0
  861.41     .05       0  935.47     .05       0 2265.29      .1       0
    2290    .045       0  2345.1      .1       0 2564.69     .05       0
 3071.34      .1       0 3276.85      .1       0 3613.65      .1       0
#XS Ineff= 1 ,-1
 2435.25 2563.42 1432.18
Permanent Ineff=
       F
Bank Sta=2290,2345.1
XS Rating Curve= 0 ,0
Exp/Cntr(USF)=0,0
Exp/Cntr=0.3,0.1

Type RM Length L Ch R = 1 ,52737   ,682.8,1211.3,829.5
XS GIS Cut Line= 4
2458505.62463119660487.5009044872460098.98876273659934.249469924
 2460311.4373136660075.8818371722461488.75636635659960.805538783
#Sta/Elev= 30
       0 1616.57  122.521587.388   318.8 1546.56     4251513.979   483.9 1492.58
  525.831491.904   581.3 1477.76     636  1468.7   692.8 1449.65   742.2 1439.15
   801.5 1413.13   846.8 1407.47     865 1411.46   983.5 1412.45  1068.2 1409.51
  1271.5 1414.29 1716.061413.456  1787.3 1410.24  1802.3 1405.82  1859.5 1405.46
  1877.3  1409.5 1888.271425.129  1909.1 1433.75  2447.7 1443.88  2753.2 1461.24
  2917.9  1477.5 2997.221497.164  3042.5 1507.56 3096.741514.805  3124.9 1517.09
#Mann= 10 ,-1 , 0
       0     .05       0  122.52      .1       0     425     .06       0
  525.83     .05       0 1716.06      .1       0  1787.3    .045       0
  1877.3      .1       0 1888.27     .05       0 2997.22      .1       0
 3096.74      .1       0
Bank Sta=1787.3,1877.3
XS Rating Curve= 0 ,0
Exp/Cntr(USF)=0,0
Exp/Cntr=0.3,0.1

Type RM Length L Ch R = 1 ,51525   ,461.4,463,463.9
XS GIS Cut Line= 4
2458836.45487235660983.8060034532459289.59660938660904.506199474
2460603.70764674660621.292613836 2461872.5045104660417.378832176
#Sta/Elev= 30
       0 1563.55   72.17 1541.58   128.2 1520.81   229.7  1493.5  270.821486.526
   294.7  1478.8   323.1 1477.87   343.4  1471.4  370.14 1468.25   538.9 1437.73
   579.9 1433.45   616.7 1423.04   645.3 1406.65   682.2 1402.74   735.4 1402.93
   755.8 1406.17  767.821405.665   800.8 1412.03  867.271409.548 1265.061411.847
  1526.1 1426.94  1839.8 1433.78  2062.6 1445.32  2281.4 1472.16  2418.1 1479.33
 2457.551486.264 2556.871509.354 2656.181531.891 2954.131590.175  3089.4 1603.83
#Mann= 13 ,-1 , 0
       0     .05       0   72.17      .1       0  270.82     .06       0
  370.14     .05       0   645.3    .045       0   755.8     .05       0
  767.82      .1       0  867.27     .05       0 1265.06     .05       0
 2457.55      .1       0 2556.87     .12       0 2656.18      .1       0
 2954.13     .12       0
Bank Sta=645.3,755.8
XS Rating Curve= 0 ,0
Exp/Cntr(USF)=0,0
Exp/Cntr=0.3,0.1

Type RM Length L Ch R = 1 ,51062   ,554.7,640.3,917
XS GIS Cut Line= 4
2458604.40772794661429.2922262272459479.41272295661335.205667624
2460761.34208392 661064.70681164 2461771.3496749660866.573296408
#Sta/Elev= 30
       0 1628.83   207.5 1573.45   267.9 1566.06   328.2 1543.45   448.9 1510.29
  571.971482.627     642 1472.35   658.1 1465.37   698.1 1463.84  770.891448.327
   879.7 1435.11   936.6 1423.58   974.3 1405.48  1091.9 1402.62  1100.1  1406.2
  1145.1 1412.04 1268.051409.559 1665.761411.536  1782.8  1413.5  1831.9 1420.38
  2224.2 1439.59  2387.2 1441.25 2461.011447.839 2560.381475.055  2664.5  1499.7
 2858.491527.962 2907.771535.735 2957.861544.353 3057.231557.932  3219.5 1587.12
#Mann= 13 ,-1 , 0
       0     .05       0  571.97     .06       0  770.89     .05       0
   974.3    .045       0  1100.1      .1       0 1268.05     .05       0
 1665.76     .05       0 2461.01     .12       0 2560.38      .1       0
 2858.49      .1       0 2907.77     .12       0 2957.86      .1       0
 3057.23     .12       0
Bank Sta=974.3,1100.1
XS Rating Curve= 0 ,0
Exp/Cntr(USF)=0,0
Exp/Cntr=0.5,0.3

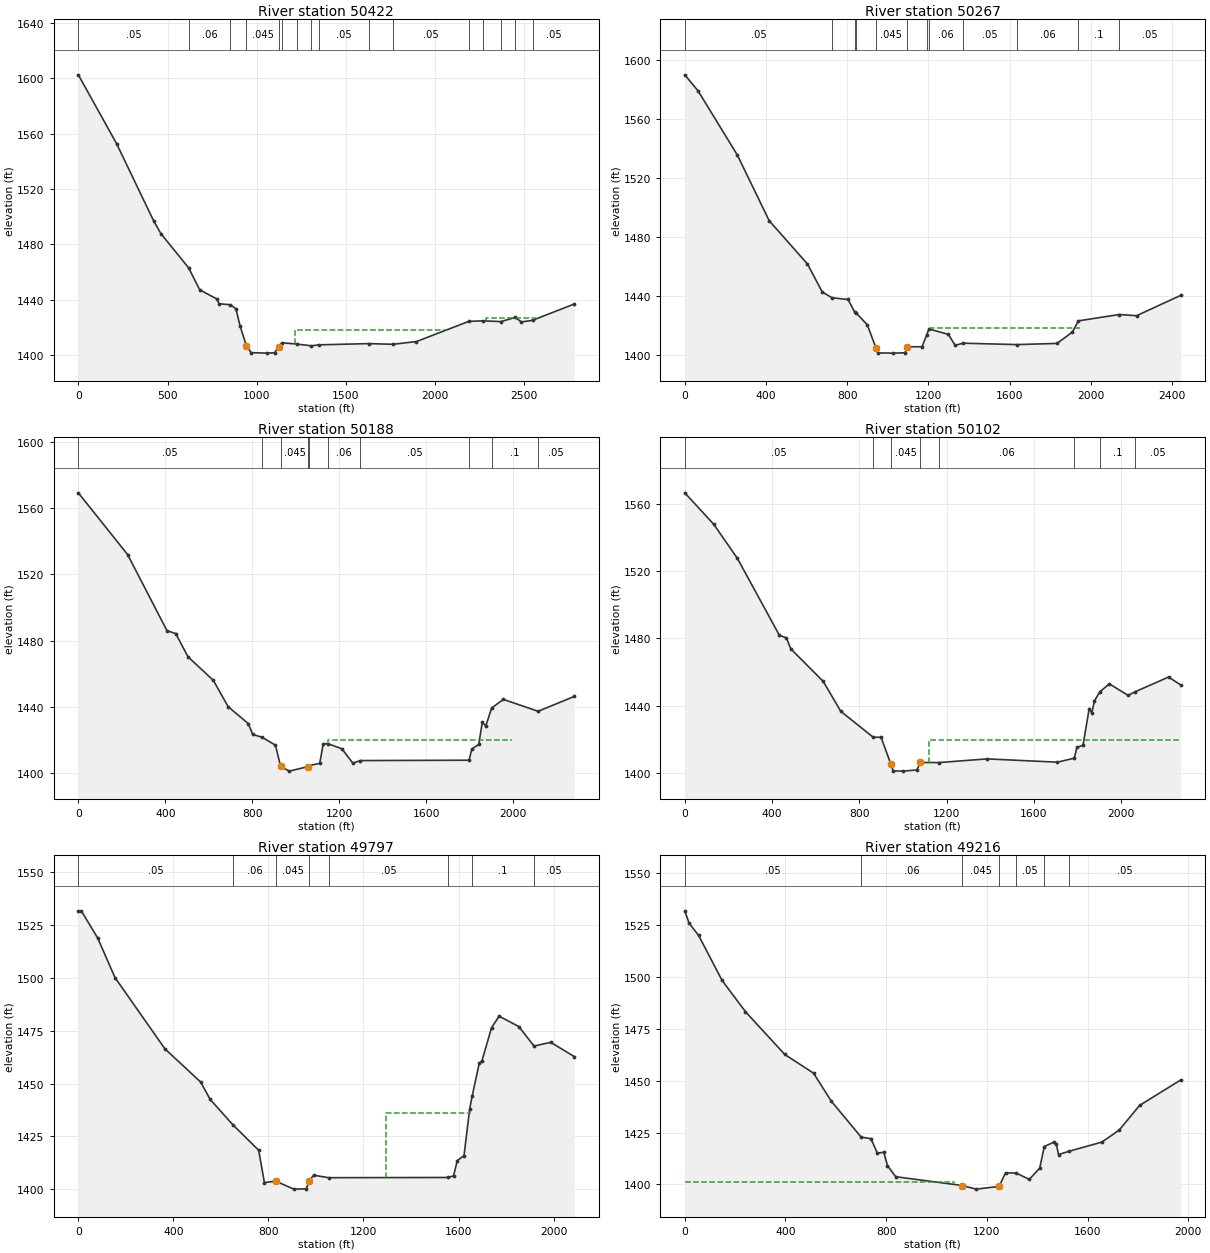
Type RM Length L Ch R = 1 ,50422   ,164,155.1,145.5
XS GIS Cut Line= 5
2458721.28063192661818.3055934282459395.57130594661758.101068961
2460039.75971773662095.2464059722461020.41839018 662116.04941746
2461060.10519367662508.704964611
#Sta/Elev= 30
       01602.644 214.314 1552.88 423.1411496.698   463.3 1487.65  618.941462.862
 680.5551447.028  777.711440.364 788.9081436.964  852.831436.238 883.7171433.298
 906.2911420.991   942.41406.454 969.4961401.5581059.2561401.2281100.4231401.535
    11231405.859 1142.011408.717 1225.091407.797 1306.161406.512 1349.181407.231
  1629.81408.122 1763.321407.6251895.1491409.594 2189.05 1424.21 2268.231424.608
 2369.211424.052 2448.391427.0412484.2781423.786 2546.071424.9782779.5891436.733
#Mann= 16 ,-1 , 0
       0     .05       0  618.94     .06       0  852.83      .1       0
   942.4    .045       0    1123      .1       0 1142.01     .06       0
 1225.09      .1       0 1306.16     .06       0 1349.18     .05       0
  1629.8     .06       0 1763.32     .05       0 2189.05     .06       0
 2268.23    .055       0 2369.21     .05       0 2448.39     .06       0
 2546.07     .05       0
#XS Ineff= 3 ,-1
       0     849    1435    1216 2060.75 1418.17 2285.05 2565.42 1426.82
Permanent Ineff=
       F       F       F
Bank Sta=942.4,1123
XS Rating Curve= 0 ,0
Exp/Cntr(USF)=0,0
Exp/Cntr=0.5,0.3

Type RM Length L Ch R = 1 ,50267   ,132.1,79.4,35.9
XS GIS Cut Line= 5
2458752.99373075662006.0479322752459424.61250147  661943.8184245
2460086.95631354662243.6963725062460907.34299476662251.739891965
2460953.16811935662467.087688934
#Sta/Elev= 30
       0 1589.75  66.0331578.742 258.8551535.381 415.5241490.913 604.3291461.527
 676.8371442.622  725.491438.617 804.1721437.481  835.891429.228  844.681428.229
 899.0671420.313 941.3821404.678 953.4621401.2811023.7151401.1331085.1881401.365
1093.969 1405.381093.9691405.3811168.6141405.492 1192.271413.691 1202.261417.502
1298.0311413.8541331.7221406.406 1370.461407.871 1636.16 1406.921833.3721407.718
1909.3751415.445  1938.51422.995 2140.051427.304 2225.21  1426.52442.1581440.246
#Mann= 12 ,-1 , 0
       0     .05       0  725.49     .06       0  835.89     .05       0
  844.68    .055       0 941.382    .045       01093.969     .06       0
 1192.27      .1       0 1202.26     .06       0 1370.46     .05       0
 1636.16     .06       0  1938.5      .1       0 2140.05     .05       0
#XS Ineff= 1 ,-1
 1209.44 1944.44 1418.46
Permanent Ineff=
       F
Bank Sta=941.382,1093.969
XS Rating Curve= 0 ,0
Exp/Cntr(USF)=0,0
Exp/Cntr=0.5,0.3

Type RM Length L Ch R = 1 ,50188   ,87,85.3,38.5
XS GIS Cut Line= 6
2458765.47016644662259.8110958782459634.50029789662165.972161496
 2459901.7372632662170.0521151642460109.81490031662261.851072713
2460839.49775751662359.1615176152460925.89060745662512.073470475
#Sta/Elev= 30
       01569.341 226.5841532.035 407.6311486.053 447.8631484.251 504.1891470.266
 620.8631455.992 689.258 1440.04 781.7931429.843  801.911423.276  844.211421.636
  906.751416.797 930.3331403.962 970.3381401.111    10581403.885 1062.061404.507
1110.3541405.7951126.3561417.595 1147.291417.7461212.797 1414.581262.3461405.957
 1297.43 1407.49 1797.241407.7111809.5761414.3841841.8591417.2971858.0011430.692
1874.143  1428.4 1900.991439.2311954.851 1444.48 2114.77 1437.29 2280.551446.232
#Mann= 10 ,-1 , 0
       0     .05       0  844.21    .055       0 930.333    .045       0
    1058     .06       0 1062.06      .1       0 1147.29     .06       0
 1297.43     .05       0 1797.24     .06       0 1900.99      .1       0
 2114.77     .05       0
#XS Ineff= 2 ,-1
  -57.08  864.911419.974 1148.39 1993.571420.127
Permanent Ineff=
       F       F
Bank Sta=930.333,1058
XS Rating Curve= 0 ,0
Exp/Cntr(USF)=0,0
Exp/Cntr=0.5,0.3

Type RM Length L Ch R = 1 ,50102   ,300.9,305.5,234.2
XS GIS Cut Line= 6
2458758.70911313662327.8880626352459629.77922142662252.408919762
2460001.05500528662252.4089197622460129.57354585662303.408340622
2460771.65252026662387.4303664712460909.53166971662584.578665008
#Sta/Elev= 30
       01566.583 132.5311547.871 240.9351527.591 433.6551481.757 465.7751480.227
  485.851473.726 634.404 1454.34 714.7041436.566  862.971421.174   899.31421.097
   943.31405.474   955.31401.129   999.31400.961  1063.31401.659  1079.31406.096
 1164.691406.0541385.0591408.2451707.7871406.281  1785.11408.7071796.5381415.053
1824.7761416.3541853.0151438.2291865.1171435.641 1877.221442.751 1902.281448.273
1945.7991452.8462031.4311446.044 2063.141448.1692217.0941456.954 2272.011452.251
#Mann= 8 ,-1 , 0
       0     .05       0  862.97     .06       0   943.3    .045       0
  1079.3      .1       0 1164.69     .06       0  1785.1     .06       0
 1902.28      .1       0 2063.14     .05       0
#XS Ineff= 2 , 0
                         1118.04         1419.68
Permanent Ineff=
       F       F
Bank Sta=943.3,1079.3
XS Rating Curve= 0 ,0
Exp/Cntr(USF)=0,0
Exp/Cntr=0.5,0.3

Type RM Length L Ch R = 1 ,49797   ,201.1,580.3,1004.4
XS GIS Cut Line= 4
 2458922.3217186662463.5317454282459473.87101086662549.160402674
2460723.04201069662556.7158724312460889.18416278662781.275324612
#Sta/Elev= 30
       01531.742  12.5721531.799  81.3871518.916 154.2491500.216 364.218 1466.48
 514.5141450.773 554.9931442.504  650.181430.528 759.0341418.418 783.0351403.162
 831.1151403.778 907.0371400.028 959.0381400.151  971.811404.089 991.0391406.608
 1053.031405.443 1556.591405.5451579.0491406.351 1595.051413.558 1623.051415.855
1647.0511437.958  1657.31443.9891687.0511459.5371699.0521460.9151739.0521476.511
1771.0531481.9191853.9281476.994 1917.861467.7741988.434 1469.532086.6891462.812
#Mann= 8 ,-1 , 0
       0     .05       0  650.18     .06       0 831.115    .045       0
  971.81      .1       0 1053.03     .05       0 1556.59     .06       0
  1657.3      .1       0 1917.86     .05       0
#XS Ineff= 1 ,-1
 1293.72 1654.211435.848
Permanent Ineff=
       F
Bank Sta=831.115,971.81
XS Rating Curve= 0 ,0
Exp/Cntr(USF)=0,0
Exp/Cntr=0.5,0.3

Type RM Length L Ch R = 1 ,49216   ,112,90.7,148.9
XS GIS Cut Line= 4
2458930.70829003662496.4484086692459689.57967242662755.525466638
2460048.61559528663667.3951116162460103.69496981663846.913073044
#Sta/Elev= 30
       0 1531.79    16.9 1525.87      55 1519.92     148  1498.3     241 1483.21
   397.3 1462.61   511.5 1453.62   581.7 1440.17  700.84 1422.79   739.3  1422.1
   765.1 1415.05   790.4 1415.57   805.1 1409.12   837.8 1403.75  1102.1 1399.51
    1158 1397.77  1248.3 1399.07  1274.2  1405.6 1316.481405.498  1368.6 1402.47
  1409.9 1407.87 1428.221418.293  1467.5 1420.47  1476.1 1419.31  1484.7 1414.42
 1528.19 1416.06  1656.7 1420.41  1725.5 1426.17  1806.5 1438.06  1969.7 1450.32
#Mann= 7 ,-1 , 0
       0     .05       0  700.84     .06       0  1102.1    .045       0
  1248.3     .06       0 1316.48     .05       0 1428.22     .06       0
 1528.19     .05       0
#XS Ineff= 2 , 0
            1070    1401    1278            1401
Permanent Ineff=
       F       F
Bank Sta=1102.1,1248.3
XS Rating Curve= 0 ,0
Exp/Cntr(USF)=0,0
Exp/Cntr=0.5,0.3

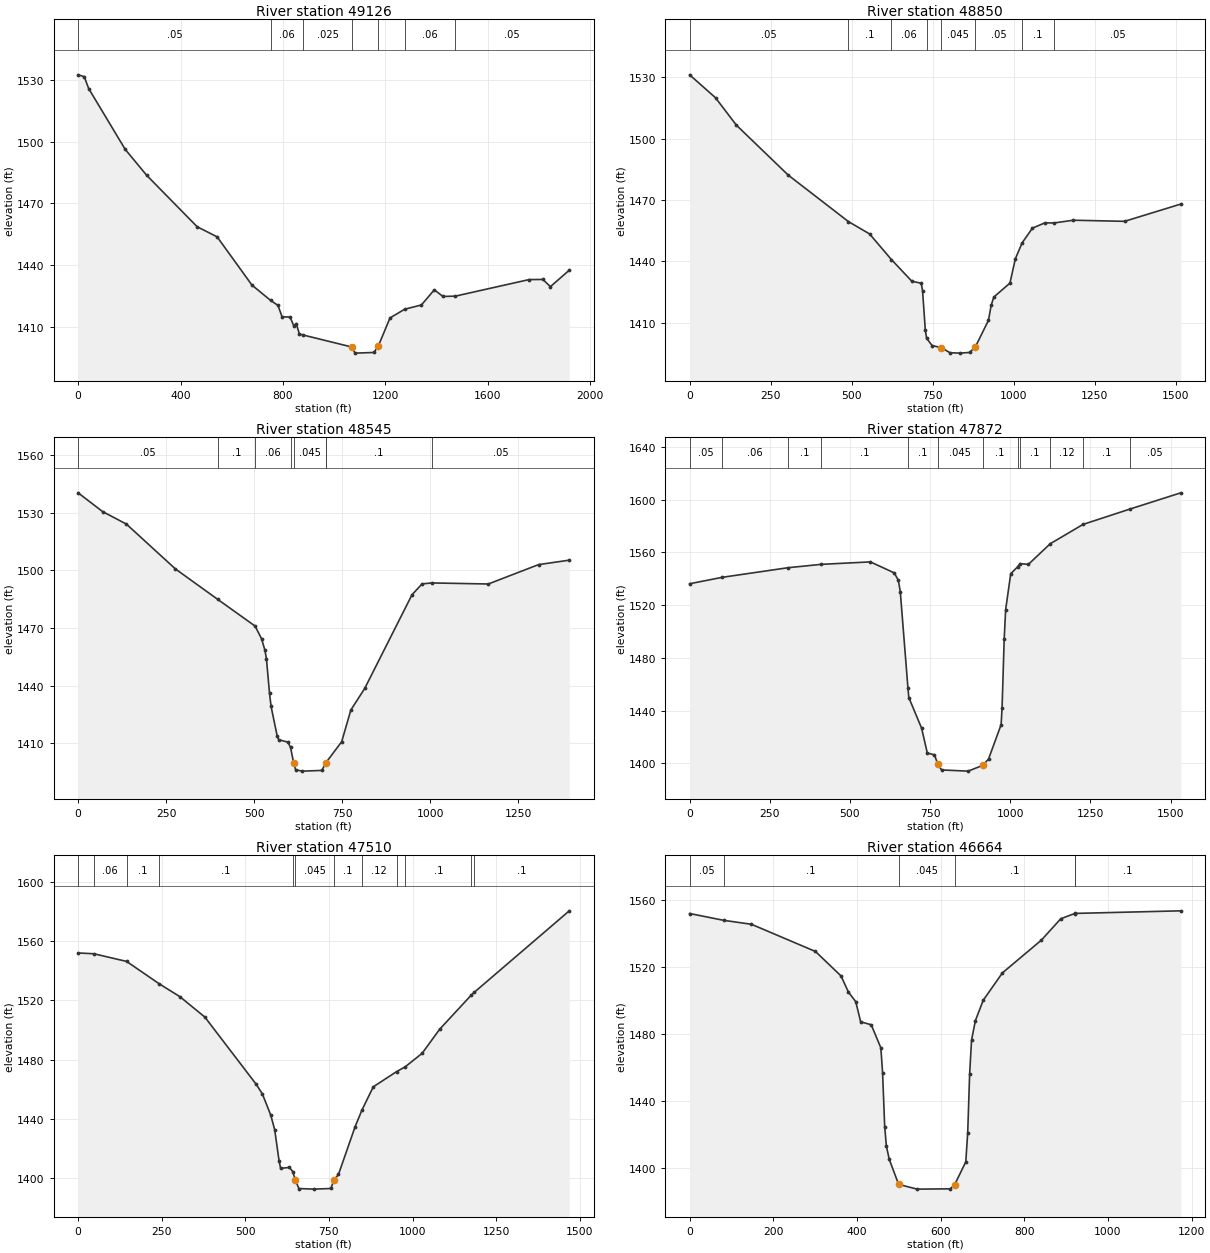
Type RM Length L Ch R = 1 ,49126   ,274.8,275.4,307.9
XS GIS Cut Line= 4
2458900.10863751 662510.728246512459624.30041372662786.125119154
2459887.45742536663579.6761077372459977.21640607663873.432771891
#Sta/Elev= 30
       0 1532.53    23.9 1531.65    41.3 1525.86   183.8  1496.3   268.1 1483.62
     465 1458.63   542.9 1453.73     679 1430.24  751.891422.796   780.5 1420.38
   796.3 1414.88     828 1414.69     843 1410.16   851.5 1411.58   864.1 1406.47
  879.441405.964  1070.6 1400.09  1081.1 1397.17  1154.9 1397.49  1171.7 1400.47
  1218.1 1414.31 1275.341418.531  1340.6 1420.59  1390.9 1427.96  1424.6 1424.74
 1472.83 1424.88  1760.6 1432.93    1815 1433.01  1844.2 1429.49    1918 1437.53
#Mann= 7 ,-1 , 0
       0     .05       0  751.89     .06       0  879.44    .025       0
  1070.6    .045       0  1171.7     .05       0 1275.34     .06       0
 1472.83     .05       0
Bank Sta=1070.6,1171.7
XS Rating Curve= 0 ,0
Exp/Cntr(USF)=0,0
Exp/Cntr=0.5,0.3

Type RM Length L Ch R = 1 ,48850   ,310.4,305.3,302.1
XS GIS Cut Line= 4
2458898.06866067662539.2879221912459416.22277661662953.403219575
2459520.26159517663334.878887609 2459646.7401589663773.473907005
#Sta/Elev= 30
       0 1531.22    79.9 1520.02   144.2 1506.64   304.7 1482.15  490.011459.493
   555.2 1453.47  622.381440.966   685.6 1430.34   714.6 1429.38   718.7 1425.57
     727  1406.6  731.12 1402.47     748 1398.94   775.8 1397.91   803.4 1395.41
   834.8 1395.22   863.9 1395.56   881.6 1398.31   921.9 1411.26   930.2 1418.59
   938.5 1422.64   988.2 1429.45  1004.8  1441.3 1025.581449.061  1057.5  1456.3
  1096.2 1458.89 1123.851458.824  1183.6 1460.17  1341.8 1459.63  1515.2 1468.07
#Mann= 8 ,-1 , 0
       0     .05       0  490.01      .1       0  622.38     .06       0
  731.12      .1       0   775.8    .045       0   881.6     .05       0
 1025.58      .1       0 1123.85     .05       0
Bank Sta=775.8,881.6
XS Rating Curve= 0 ,0
Exp/Cntr(USF)=0,0
Exp/Cntr=0.3,0.1

Type RM Length L Ch R = 1 ,48545   ,677.4,673.2,667.7
XS GIS Cut Line= 4
2458817.60787106662552.8007919152459082.50777871662950.150653391
2459257.10089966663353.5209673152459395.57130594663811.075353258
#Sta/Elev= 30
       0 1540.41    69.8 1530.61   137.1 1524.13   276.3 1500.77  396.821484.853
  502.641470.983   520.9 1464.44   530.7 1458.35     535  1453.8   543.7 1435.86
   548.1 1429.09   565.5 1413.64   569.9 1411.76     596 1410.47  603.431407.706
   612.1 1399.77   617.8 1396.09   636.5 1395.38   691.9 1395.74   703.4 1399.42
  704.211399.855   748.6 1410.71   774.7 1427.24     814 1438.46   948.4 1487.31
     977 1492.95 1004.521493.454  1165.1  1492.9  1307.7 1502.99  1395.1 1505.32
#Mann= 8 ,-1 , 0
       0     .05       0  396.82      .1       0  502.64     .06       0
  603.43      .1       0   612.1    .045       0   703.4      .1       0
  704.21      .1       0 1004.52     .05       0
Bank Sta=612.1,703.4
XS Rating Curve= 0 ,0
Exp/Cntr(USF)=0,0
Exp/Cntr=0.3,0.1

Type RM Length L Ch R = 1 ,47872   ,372.3,361.7,356
XS GIS Cut Line= 4
2458161.37855438662625.0462212742458420.25800959 663130.76422679
2458661.07610745663630.4617798592458841.68968085663997.709379103
#Sta/Elev= 30
       0 1536.17  101.911541.057  307.351548.348  410.071550.878   563.8 1552.76
   638.4 1544.41     651  1538.8   657.1 1530.25   680.9  1457.4   683.7 1449.88
   723.7 1426.56   741.4 1407.77   763.6 1406.41   773.8 1399.59   785.8 1394.94
   868.7 1394.04   914.6 1398.44   932.4 1403.23   971.6 1429.27   974.6 1441.93
   981.2  1494.1   985.7 1516.37  1001.6 1543.79 1022.91 1548.95 1030.131551.439
  1056.7 1550.88 1124.861566.527 1227.051581.172 1372.65 1592.77  1532.1 1605.14
#Mann= 12 ,-1 , 0
       0     .05       0  101.91     .06       0  307.35      .1       0
  410.07      .1       0   680.9      .1       0   773.8    .045       0
   914.6      .1       0 1022.91     .12       0 1030.13      .1       0
 1124.86     .12       0 1227.05      .1       0 1372.65     .05       0
Bank Sta=773.8,914.6
XS Rating Curve= 0 ,0
Exp/Cntr(USF)=0,0
Exp/Cntr=0.3,0.1

Type RM Length L Ch R = 1 ,47510   ,873.6,846.5,739.7
XS GIS Cut Line= 4
2458016.62439775662895.2992129392458137.03344672663390.314192006
2458397.91971947663871.9503878552458685.56355866664166.283618651
#Sta/Elev= 30
       0 1551.94   47.171551.396  145.061546.226  242.951531.082   304.2 1522.48
   378.9 1508.73   532.9 1463.27     551 1456.87   576.1 1442.57   587.9 1432.68
   601.1 1411.55   605.6 1406.68   632.1 1407.29  641.721404.518   649.8 1398.77
   660.2 1393.05   705.9 1392.66   755.8 1393.09   764.9 1398.74   778.5 1402.53
   828.5 1434.85  848.821445.997   882.6 1461.65  952.361471.904   978.61475.231
  1028.7 1484.24  1081.3 1500.52 1175.531523.486 1184.791525.431  1468.8 1580.35
#Mann= 12 ,-1 , 0
       0      .1       0   47.17     .06       0  145.06      .1       0
  242.95      .1       0  641.72    .025       0   649.8    .045       0
   764.9      .1       0  848.82     .12       0  952.36      .1       0
   978.6      .1       0 1175.53      .1       0 1184.79      .1       0
Bank Sta=649.8,764.9
XS Rating Curve= 0 ,0
Exp/Cntr(USF)=0,0
Exp/Cntr=0.3,0.1

Type RM Length L Ch R = 1 ,46664   ,758.1,765.8,745.9
XS GIS Cut Line= 4
2457378.71973632  663558.21635052457577.39466706663889.341235064
 2457764.0286929664214.4456671812457974.74452854664569.652361532
#Sta/Elev= 30
       0  1551.7   81.051547.657   147.8 1545.28   300.8 1529.07     362 1514.48
   379.5  1504.9   397.1 1499.17   408.8 1487.16   434.1 1485.39   457.1 1471.61
   461.2  1456.9   466.3 1424.51   470.3 1413.11   477.2 1405.15   499.6 1390.26
   543.6 1387.43   623.2 1387.61  633.56 1390.14   660.1 1403.69   664.7 1421.17
   669.3 1456.04   673.9  1476.3   683.1 1487.91   701.8 1500.02   747.7 1516.34
   840.6 1535.79   887.1 1548.58  920.241551.677  921.53 1551.76    1174  1553.3
#Mann= 6 ,-1 , 0
       0     .05       0   81.05      .1       0   499.6    .045       0
  633.56      .1       0  920.24      .1       0  921.53      .1       0
Bank Sta=499.6,633.56
XS Rating Curve= 0 ,0
Exp/Cntr(USF)=0,0
Exp/Cntr=0.3,0.1

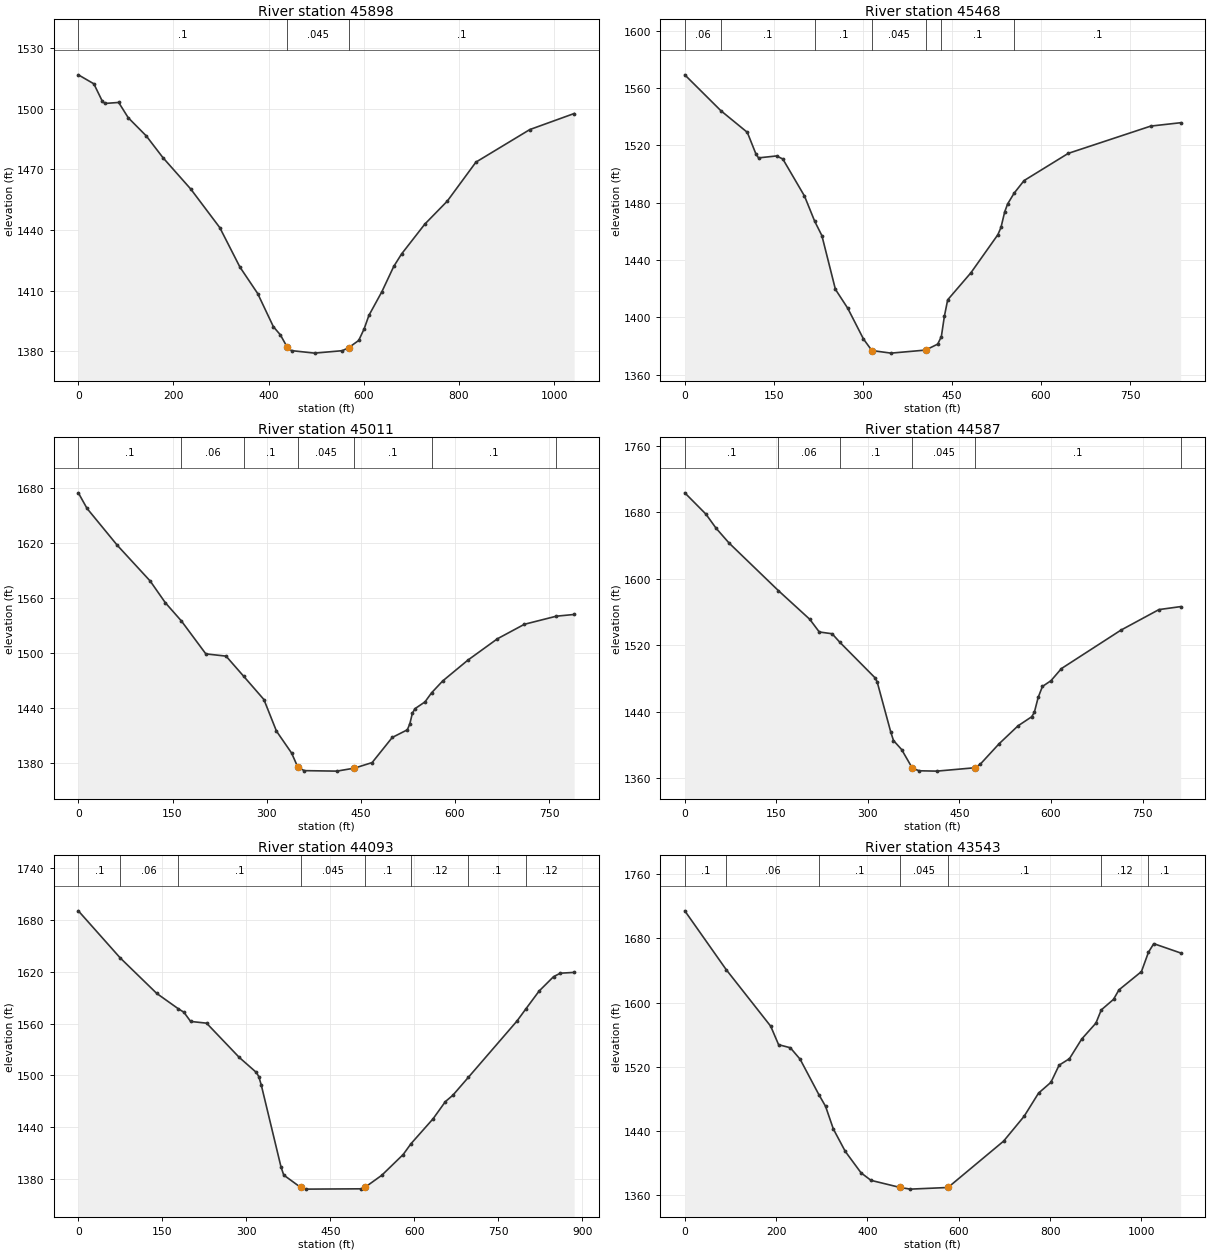
Type RM Length L Ch R = 1 ,45898   ,461.8,429.6,422.2
XS GIS Cut Line= 4
2456772.28558183664130.8938281272456943.45306534664310.839131304
2457228.73220452664714.6188359942457417.45532736664947.231057174
#Sta/Elev= 30
       0 1516.69    32.6 1512.25      50 1503.84    55.8 1502.53    84.8 1503.03
   104.9 1495.47   142.9 1486.46   177.7 1475.77   236.6 1460.12   297.4  1441.1
   339.7  1421.6     377 1408.53     410 1392.12   424.7 1388.09   439.4 1381.86
   448.2 1380.28   496.7 1379.04     555 1380.25   568.6 1381.79   589.4 1385.31
   600.9 1391.09   610.8 1397.69   638.2 1409.47     663  1421.9   679.4 1428.06
   728.4 1442.86   775.6 1454.23   835.8 1473.51   949.1 1489.62  1042.3 1497.55
#Mann= 3 ,-1 , 0
       0      .1       0   439.4    .045       0   568.6      .1       0
Bank Sta=439.4,568.6
XS Rating Curve= 0 ,0
Exp/Cntr(USF)=0,0
Exp/Cntr=0.3,0.1

Type RM Length L Ch R = 1 ,45468   ,521.4,457.2,404.3
XS GIS Cut Line= 4
2456539.67336065664604.8960901542456684.50738515664732.174475328
  2456952.230885664995.5090653432457167.28746685665153.509819352
#Sta/Elev= 30
       0 1569.32   60.871544.235   105.3 1529.17   119.8 1514.08   124.2 1511.34
   154.5 1512.68   165.1 1510.57   201.6  1484.7  218.891467.009   230.9 1457.08
   253.7 1419.57   274.5 1406.33     301 1384.86   315.1 1376.82   347.4 1375.02
   405.6 1377.15     426 1381.31  432.151386.552   437.2 1400.61   442.8 1412.22
     482 1431.15   527.3 1457.67   532.6 1462.76   538.9 1473.71   543.8 1479.18
  554.691486.672   571.5 1495.49   645.9 1514.48   784.9 1533.53   835.2 1535.88
#Mann= 7 ,-1 , 0
       0     .06       0   60.87      .1       0  218.89      .1       0
   315.1    .045       0   405.6      .1       0  432.15      .1       0
  554.69      .1       0
Bank Sta=315.1,405.6
XS Rating Curve= 0 ,0
Exp/Cntr(USF)=0,0
Exp/Cntr=0.3,0.1

Type RM Length L Ch R = 1 ,45011   ,444.9,423.7,395.4
XS GIS Cut Line= 4
2456329.00568863665329.0662126952456596.72918848 665298.34384386
2456908.34178667665276.3992946922457114.62054885665250.065835691
#Sta/Elev= 30
       0 1674.39    13.8 1657.45    62.1 1617.18   114.5 1578.25   138.6 1554.62
   164.11534.833   203.1 1498.89   235.3 1496.46  263.521474.389   295.6 1449.14
   315.6 1414.75   339.7 1390.86   349.5 1375.61   359.7 1371.68   411.8 1371.14
   439.9 1374.42     468 1380.46   500.1 1407.86   524.1 1416.17   528.1 1422.85
   532.1 1434.22   536.2 1439.17   552.2 1446.59  562.671456.461   580.3 1469.33
   620.6 1492.14   667.6 1515.37   710.5 1531.14  761.481539.972   789.8 1541.85
#Mann= 7 ,-1 , 0
       0      .1       0   164.1     .06       0  263.52      .1       0
   349.5    .045       0   439.9      .1       0  562.67      .1       0
  761.48      .1       0
Bank Sta=349.5,439.9
XS Rating Curve= 0 ,0
Exp/Cntr(USF)=0,0
Exp/Cntr=0.3,0.1

Type RM Length L Ch R = 1 ,44587   ,486.5,494.6,490.2
XS GIS Cut Line= 4
2456522.11772131665820.6241140572456781.06340149665732.845917385
2457119.00945868665570.4562535432457277.01021269665526.567155207
#Sta/Elev= 30
       0 1703.56    34.5 1677.99    51.3 1660.89    72.5  1643.1  153.391585.714
   204.8 1551.16   220.3 1535.93   241.4 1533.78  254.091523.438   312.1  1480.4
   315.2 1475.67   337.4 1415.47   341.9 1405.16   355.2 1394.33   372.9 1371.69
   384.1 1368.71   412.9 1368.29     475 1372.35   483.9 1376.51   514.9 1401.26
   545.9 1422.85   568.2 1433.73   572.6 1438.97   578.9 1457.03   585.9 1470.31
   599.9 1477.23     617 1491.83   714.5 1538.14   776.8 1562.91   812.3 1566.48
#Mann= 6 ,-1 , 0
       0      .1       0  153.39     .06       0  254.09      .1       0
   372.9    .045       0     475      .1       0   812.3      .1       0
Bank Sta=372.9,475
XS Rating Curve= 0 ,0
Exp/Cntr(USF)=0,0
Exp/Cntr=0.3,0.1

Type RM Length L Ch R = 1 ,44093   ,543.8,549.8,554.3
XS GIS Cut Line= 4
2456776.67449166666272.6818269162457057.56472101666136.625622075
2457347.23277002  665996.18050742457575.45608137665890.846671394
#Sta/Elev= 30
       0 1690.74   74.791636.172   140.1 1595.01  178.451577.313   188.5 1573.27
   200.5  1562.6     229 1560.59   287.3 1520.96   317.9 1503.52   322.3 1498.64
   326.8 1488.62   361.9 1394.08   366.8 1384.61   397.2 1370.25   407.1 1368.32
   504.6 1368.68   511.9 1370.44   541.8 1384.33   580.1 1408.43  593.96 1420.88
   633.5 1449.85   655.5 1469.77   668.7 1477.03  696.421497.796   783.3 1563.08
  799.511577.433   822.9 1597.87   848.6 1614.45   860.7 1618.48   885.4 1619.41
#Mann= 8 ,-1 , 0
       0      .1       0   74.79     .06       0  178.45      .1       0
   397.2    .045       0   511.9      .1       0  593.96     .12       0
  696.42      .1       0  799.51     .12       0
Bank Sta=397.2,511.9
XS Rating Curve= 0 ,0
Exp/Cntr(USF)=0,0
Exp/Cntr=0.3,0.1

Type RM Length L Ch R = 1 ,43543   ,500.8,538.9,564.2
XS GIS Cut Line= 4
 2456939.0641555666759.8508184442457224.34329468666650.128072604
2457575.45608137666505.2940480962457930.95777789666320.959835086
#Sta/Elev= 30
       0 1714.46   90.57 1641.29   188.2  1570.7   205.4 1547.74   231.1 1543.91
   252.5 1529.68  293.511485.638   308.3 1470.95   325.3 1442.76   351.5 1414.78
   386.1 1388.05   407.8 1378.74   471.5 1369.91   493.8 1367.82   576.4 1369.86
   698.2 1427.59   743.1 1458.52   774.8 1487.44   801.8 1500.83   819.8 1522.24
   842.4 1530.28   869.4 1554.87   900.4 1574.61   912.1 1591.04   938.9 1604.15
   950.8 1615.98  1000.1 1638.78 1015.531662.963  1027.1 1673.56  1085.9 1661.97
#Mann= 7 ,-1 , 0
       0      .1       0   90.57     .06       0  293.51      .1       0
   471.5    .045       0   576.4      .1       0   912.1     .12       0
 1015.53      .1       0
Bank Sta=471.5,576.4
XS Rating Curve= 0 ,0
Exp/Cntr(USF)=0,0
Exp/Cntr=0.3,0.1

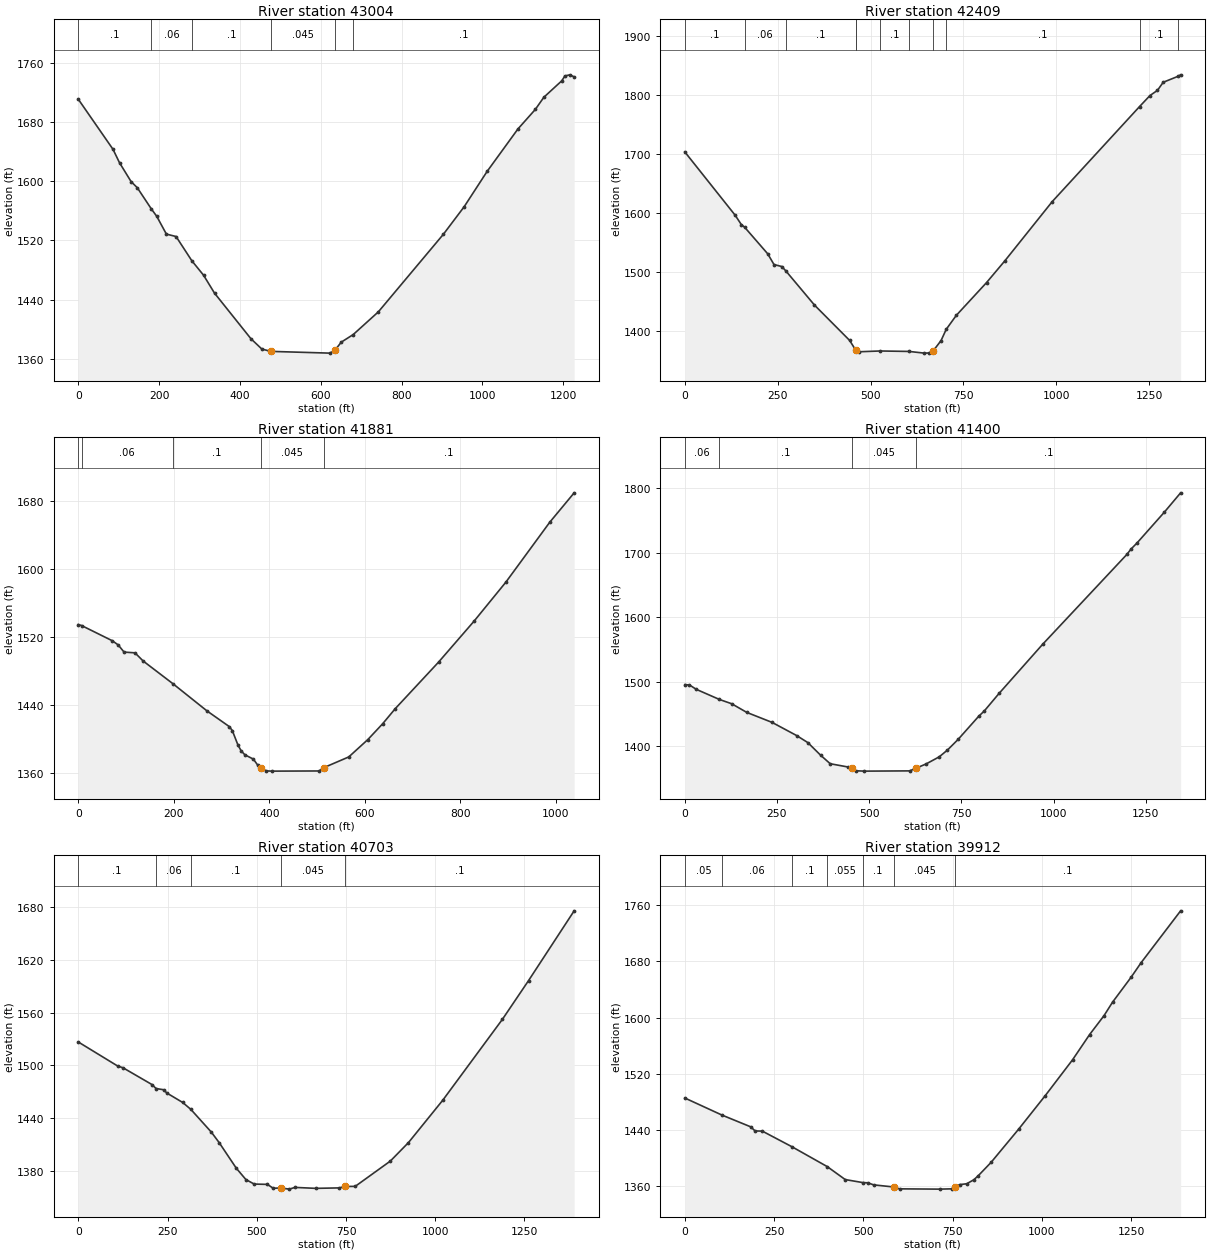
Type RM Length L Ch R = 1 ,43004   ,577.9,594.9,644.6
XS GIS Cut Line= 4
2457004.89780301667110.9636051312457338.45495036667102.185785464
2457790.51266322667071.4634166282458229.40364658 667036.35213796
#Sta/Elev= 30
       0 1710.54    85.9 1642.89   101.9 1624.86   130.5 1599.45   145.9  1591.1
   180.81562.377   193.9 1552.62   217.9 1528.46   241.9 1525.18  281.021492.358
     310 1472.88     337 1448.74   427.1 1387.18   454.2 1373.17   476.7 1370.04
   622.6 1367.69   634.7 1371.33   650.7 1382.49  680.251392.758   742.5 1423.43
   903.4 1528.19   954.7 1565.28  1011.7 1613.14    1088  1670.5    1131 1696.87
  1152.2 1713.33  1196.3 1735.43  1204.3 1742.05  1216.4 1743.58  1227.1 1740.81
#Mann= 6 ,-1 , 0
       0      .1       0   180.8     .06       0  281.02      .1       0
   476.7    .045       0   634.7    .025       0  680.25      .1       0
Bank Sta=476.7,634.7
XS Rating Curve= 0 ,0
Exp/Cntr(USF)=0,0
Exp/Cntr=0.3,0.1

Type RM Length L Ch R = 1 ,42409   ,517.5,528.4,557.7
BEGIN DESCRIPTION:
Mannings N in channel placed 0.1 because of island in the channel
END DESCRIPTION:
XS GIS Cut Line= 4
2457009.28671284667541.0767688222457364.78840936667650.799514662
2457812.45721238667751.7444408342458312.79293341667808.800268671
#Sta/Elev= 30
       0 1703.51   135.5 1596.41   152.2 1580.53  161.111576.037   223.2  1531.1
   240.1 1512.92   261.1  1509.6  271.951502.175     349 1444.42   443.8 1384.52
  459.711368.423   460.8 1367.61   468.4 1365.41   525.8 1366.76   603.7 1365.98
   644.7 1363.12     657 1363.38   669.3 1367.52   689.8 1384.46  703.581403.363
   730.8 1427.02   812.1  1482.4   861.2 1519.07     989 1619.46 1224.051780.223
    1252 1798.82  1272.1 1807.54  1287.6 1821.23 1327.221831.266  1334.5 1833.85
#Mann= 11 ,-1 , 0
       0      .1       0  161.11     .06       0  271.95      .1       0
  459.71    .025       0   460.8    .045       0   525.8      .1       0
   603.7    .045       0   669.3      .1       0  703.58      .1       0
 1224.05      .1       0 1327.22      .1       0
Bank Sta=460.8,669.3
XS Rating Curve= 0 ,0
Exp/Cntr(USF)=0,0
Exp/Cntr=0.3,0.1

Type RM Length L Ch R = 1 ,41881   ,416.6,480.6,534.3
XS GIS Cut Line= 4
2457000.50889317668032.6346701832457263.84348319668137.968506189
2457610.56736004668304.7470798662457851.95740089668585.637309215
#Sta/Elev= 30
       0 1534.16    6.661533.088    71.2 1515.17    83.5 1510.26    95.8 1501.83
   118.7 1500.96   135.8 1491.35   198.11464.688   269.5 1432.69   316.5 1414.14
   322.7 1409.38   334.4 1392.58   341.1 1385.71     349 1381.03   366.7    1376
   375.6 1369.09   382.4 1365.95   393.4 1362.17   405.7 1361.88   504.3 1362.07
   514.3 1365.99   566.5 1378.56   606.4 1398.93   637.5 1417.56   664.1 1435.44
   754.6 1490.01   828.9 1538.13   895.7 1584.11   987.6 1654.53  1038.7 1689.09
#Mann= 5 ,-1 , 0
       0      .1       0    6.66     .06       0   198.1      .1       0
   382.4    .045       0   514.3      .1       0
Bank Sta=382.4,514.3
XS Rating Curve= 0 ,0
Exp/Cntr(USF)=0,0
Exp/Cntr=0.3,0.1

Type RM Length L Ch R = 1 ,41400   ,619.4,697.1,728
XS GIS Cut Line= 4
  2456899.563967668159.9130553572457053.17581117668436.414374873
2457298.95476186668809.471710728 2457579.8449912669318.585251423
#Sta/Elev= 30
       0 1495.54    12.6 1495.16    30.9  1488.4   93.991472.611     127 1466.03
   168.1 1452.57   236.8 1437.06   303.1 1416.75   333.7 1405.75   368.3 1386.23
   394.3 1373.02   443.4 1367.88   452.1 1365.95   463.6 1362.12   486.9 1361.56
     610 1361.94   628.2  1366.4   654.2 1372.65     690 1383.74   711.8 1394.01
   740.9 1410.58   796.6 1446.35   812.3 1454.91   852.3 1482.08   970.2 1558.04
  1198.7 1697.38  1209.7 1705.55  1226.2 1715.12  1299.8 1762.53  1344.5 1792.89
#Mann= 4 ,-1 , 0
       0     .06       0   93.99      .1       0   452.1    .045       0
   628.2      .1       0
Bank Sta=452.1,628.2
XS Rating Curve= 0 ,0
Exp/Cntr(USF)=0,0
Exp/Cntr=0.3,0.1

Type RM Length L Ch R = 1 ,40703   ,748.2,790.5,819.5
XS GIS Cut Line= 4
2456451.89516397668295.9692601982456522.11772131668651.470956719
2456653.78501632669239.5848744192456732.78539332669656.531308609
#Sta/Elev= 30
       0 1526.68   110.5 1499.33   125.3  1497.4   206.8 1478.25  217.721473.861
   239.5 1472.42   247.6 1468.84   292.5 1457.98  315.341450.139   372.5 1424.43
   394.6 1412.43   442.8 1383.25   469.6 1370.42   492.9 1365.31   529.8 1364.97
   546.2 1360.53   566.7  1360.9   566.7 1360.91   591.3 1359.57   606.9 1361.53
   665.1 1360.45   731.4 1360.97   747.1 1362.61   775.8 1362.68   874.2  1391.4
   925.1 1412.43  1021.3 1460.61  1188.3 1552.43  1261.5 1596.37  1389.4 1675.69
#Mann= 5 ,-1 , 0
       0      .1       0  217.72     .06       0  315.34      .1       0
   566.7    .045       0   747.1      .1       0
Bank Sta=566.7,747.1
XS Rating Curve= 0 ,0
Exp/Cntr(USF)=0,0
Exp/Cntr=0.3,0.1

Type RM Length L Ch R = 1 ,39912   ,713.7,788.2,830
XS GIS Cut Line= 4
2455793.55868894668414.469825705 2455815.5032381668761.193702558
 2455802.3365086669305.4185219232455819.89214794669801.365333118
#Sta/Elev= 30
       0 1485.57  104.381461.191   184.8 1444.46   196.8 1438.63   216.9 1438.45
  300.271416.084  398.81 1387.88   449.1 1369.42  497.921365.163   512.4  1364.8
   528.8 1361.86   585.2 1358.85   601.2 1356.21   713.3 1355.81   749.2 1356.23
   757.2 1358.52   769.2 1362.22   789.2 1363.45   809.2 1369.16   821.3 1374.77
   857.3 1393.81   934.4 1441.07  1009.1 1488.94  1085.4 1539.86  1133.4 1575.97
  1173.5 1602.74  1197.5 1622.01  1249.3 1657.41  1277.5 1678.27  1388.1  1752.1
#Mann= 7 ,-1 , 0
       0     .05       0  104.38     .06       0  300.27      .1       0
  398.81    .055       0  497.92      .1       0   585.2    .045       0
   757.2      .1       0
Bank Sta=585.2,757.2
XS Rating Curve= 0 ,0
Exp/Cntr(USF)=0,0
Exp/Cntr=0.3,0.1