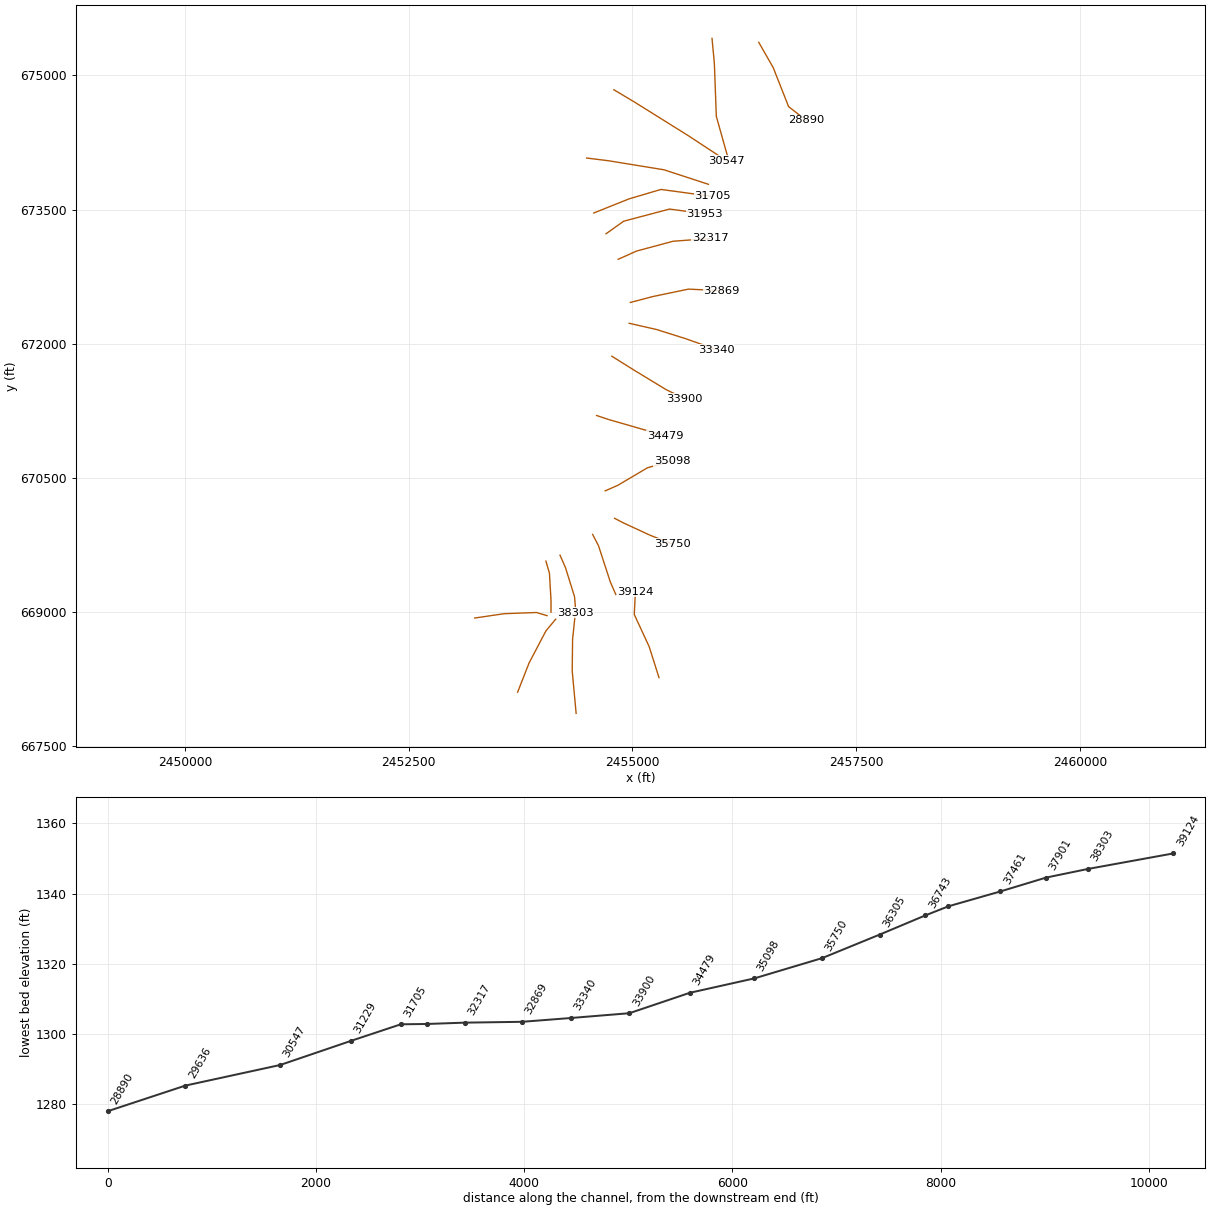
HEC-RAS study SBPOTOMC.prj: SBPOTOMC

--- SBPOTOMC.g01 (geometry) --- (continued)

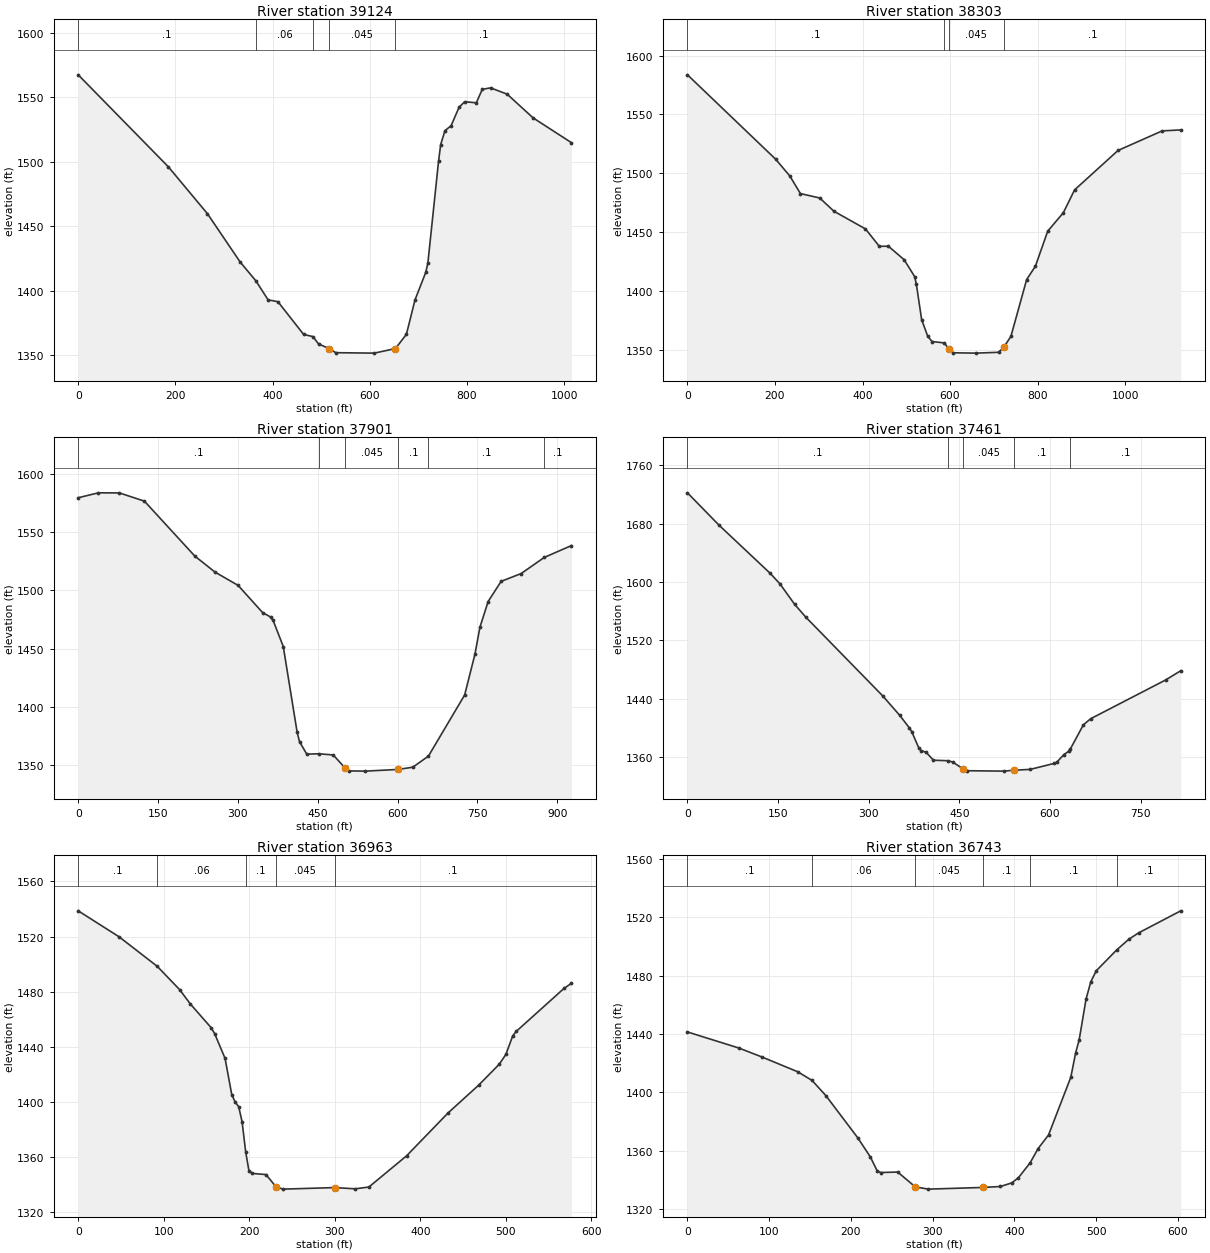
Type RM Length L Ch R = 1 ,39124   ,866.2,821.4,790.2
XS GIS Cut Line= 4
2455297.61187774668265.246891363 2455187.8891319668611.970768216
2455021.11055823 668971.861374572455034.27728773669226.418144918
#Sta/Elev= 30
       0 1567.37   185.3 1496.11     266 1459.62   333.2 1422.21  365.781407.492
   390.8  1392.8     411 1391.38   463.9 1365.99  483.011364.296   494.7 1358.57
   516.8 1354.98     530 1351.81   609.4 1351.47   652.9 1355.02   675.5  1366.1
   693.1 1392.73   715.2 1414.07   719.6 1421.25   741.6 1500.32     746 1513.25
   754.8 1524.04   767.4 1527.89   783.8 1542.16   795.4 1546.53   819.4 1545.66
   831.5  1556.1   848.6 1557.26   882.8 1552.37   936.1 1533.99  1015.2 1514.72
#Mann= 5 ,-1 , 0
       0      .1       0  365.78     .06       0  483.01      .1       0
   516.8    .045       0   652.9      .1       0
Bank Sta=516.8,652.9
XS Rating Curve= 0 ,0
Exp/Cntr(USF)=0,0
Exp/Cntr=0.3,0.1

Type RM Length L Ch R = 1 ,38303   ,455.4,401.8,367.6
XS GIS Cut Line= 4
2454371.55190286667865.8560965072454327.66280452668339.858358534
2454332.05171435668695.3600550552454362.77408319668989.417013905
#Sta/Elev= 30
       0 1583.74   201.9 1511.84     234 1497.64   258.1 1482.74   302.3 1478.99
   334.5 1467.77   406.8 1452.67   438.5 1437.85     459 1438.01   495.1 1426.51
   519.1 1412.16   523.1 1405.49   535.1 1375.56   549.2 1361.22   559.1 1356.91
  587.211355.697   596.7 1350.76   607.1 1347.34   659.1 1347.04   710.9 1347.74
     723 1352.14   739.1 1361.29   775.1 1409.62   795.1    1421   823.1 1450.68
   859.1 1466.58   884.6 1485.88   983.9 1519.42  1084.8 1536.07  1127.2 1536.89
#Mann= 4 ,-1 , 0
       0      .1       0  587.21     .06       0   596.7    .045       0
     723      .1       0
Bank Sta=596.7,723
XS Rating Curve= 0 ,0
Exp/Cntr(USF)=0,0
Exp/Cntr=0.3,0.1

Type RM Length L Ch R = 1 ,37901   ,552.8,440.1,374.7
XS GIS Cut Line= 4
2453717.60433765668102.8572275212453844.88272282668427.636555206
2454033.60584567 668787.527161562454143.32859151668919.194456567
#Sta/Elev= 30
       0  1579.8    37.9 1584.03    77.4 1583.95   124.4 1576.86   219.1 1529.58
   257.1 1515.79   300.3 1504.42   346.6 1480.89   361.5 1477.17   366.1 1474.29
   385.2 1451.78   411.2 1378.19   415.7 1369.92   429.3 1359.22  451.781359.497
     479 1358.51   500.8 1347.54   507.9 1344.78   539.3 1344.58   600.9 1346.03
   628.5 1347.95   657.91357.507   725.9 1410.08   745.4  1445.5   754.5 1468.24
     770 1490.51   794.5 1507.89     832 1514.56  875.321528.429   926.6 1538.68
#Mann= 6 ,-1 , 0
       0      .1       0  451.78     .06       0   500.8    .045       0
   600.9      .1       0   657.9      .1       0  875.32      .1       0
Bank Sta=500.8,600.9
XS Rating Curve= 0 ,0
Exp/Cntr(USF)=0,0
Exp/Cntr=0.3,0.1

Type RM Length L Ch R = 1 ,37461   ,633,497.6,364.2
XS GIS Cut Line= 4
2453239.21316579668932.3611860682453568.38140331668980.639194238
2453928.27200966668993.8059237382454046.77257517 668958.69464507
#Sta/Elev= 30
       0 1722.42    52.1 1678.15     137 1611.94   153.2  1597.4   177.4 1569.41
   195.4 1552.25     323 1443.96   351.1 1417.33   367.1 1400.11   371.1  1394.9
   383.1 1372.01   387.1 1368.74   395.1 1366.35   407.1 1355.59  431.22 1354.89
   439.1 1353.08   456.8  1343.3   463.1 1341.19   523.9 1340.62   540.5 1341.91
   567.2    1343   607.2 1351.24   611.3 1352.94   623.2 1363.43   631.3 1368.03
  633.781371.176   655.3 1404.19   667.3  1412.5   791.4 1465.68   816.4 1478.37
#Mann= 5 ,-1 , 0
       0      .1       0  431.22     .06       0   456.8    .045       0
   540.5      .1       0  633.78      .1       0
Bank Sta=456.8,540.5
XS Rating Curve= 0 ,0
Exp/Cntr(USF)=0,0
Exp/Cntr=0.3,0.1

Type RM Length L Ch R = 1 ,36963   ,209.1,220.4,244.2
XS GIS Cut Line= 4
2454033.60584567669568.7531119382454073.10603417669432.696907097
2454090.66167351669134.2510384132454090.66167351668998.194833572
#Sta/Elev= 30
       0 1538.68    47.8  1519.8   92.421498.337   118.6 1481.38   131.1 1470.99
   155.5 1453.68   159.5 1449.45   171.7 1431.43   179.5 1405.16   183.6 1399.54
   187.6 1396.37   191.6 1385.33   195.81363.456   199.6  1349.7   203.6 1347.83
   219.6 1346.97   231.3 1338.03   239.6  1336.4   299.8 1337.52   323.8 1336.63
   339.8 1337.91   383.9 1360.61   432.5 1391.83   468.1 1411.93   492.1 1427.08
     500  1434.3     508 1447.82     512    1451   567.9 1482.26   576.7 1486.02
#Mann= 5 ,-1 , 0
       0      .1       0   92.42     .06       0   195.8      .1       0
   231.3    .045       0   299.8      .1       0
Bank Sta=231.3,299.8
XS Rating Curve= 0 ,0
Exp/Cntr(USF)=0,0
Exp/Cntr=0.3,0.1

Type RM Length L Ch R = 1 ,36743   ,446.8,438,439.1
XS GIS Cut Line= 4
2454191.60659968669634.5867594422454253.05133735669494.141644767
2454353.99626352669169.3623170822454362.77408319669059.639571242
#Sta/Elev= 30
       0 1441.38    62.9 1430.39    91.4  1424.2     135 1414.11  152.431408.207
   169.3 1397.85   208.4 1368.91   223.7 1355.89   232.1 1346.36   236.3 1345.17
   257.2 1345.51   278.7 1335.37   294.7 1333.82   361.8 1334.98   382.9 1335.62
   396.9 1338.11   404.9 1341.62  419.181351.786     429 1361.61   441.7 1370.84
     469 1410.39     475 1427.32   479.2 1435.86   487.6 1463.79   493.4 1475.62
   500.1 1483.25  525.15 1497.54     540 1504.87   552.1 1509.24   603.5 1524.29
#Mann= 6 ,-1 , 0
       0      .1       0  152.43     .06       0   278.7    .045       0
   361.8      .1       0  419.18      .1       0  525.15      .1       0
Bank Sta=278.7,361.8
XS Rating Curve= 0 ,0
Exp/Cntr(USF)=0,0
Exp/Cntr=0.3,0.1

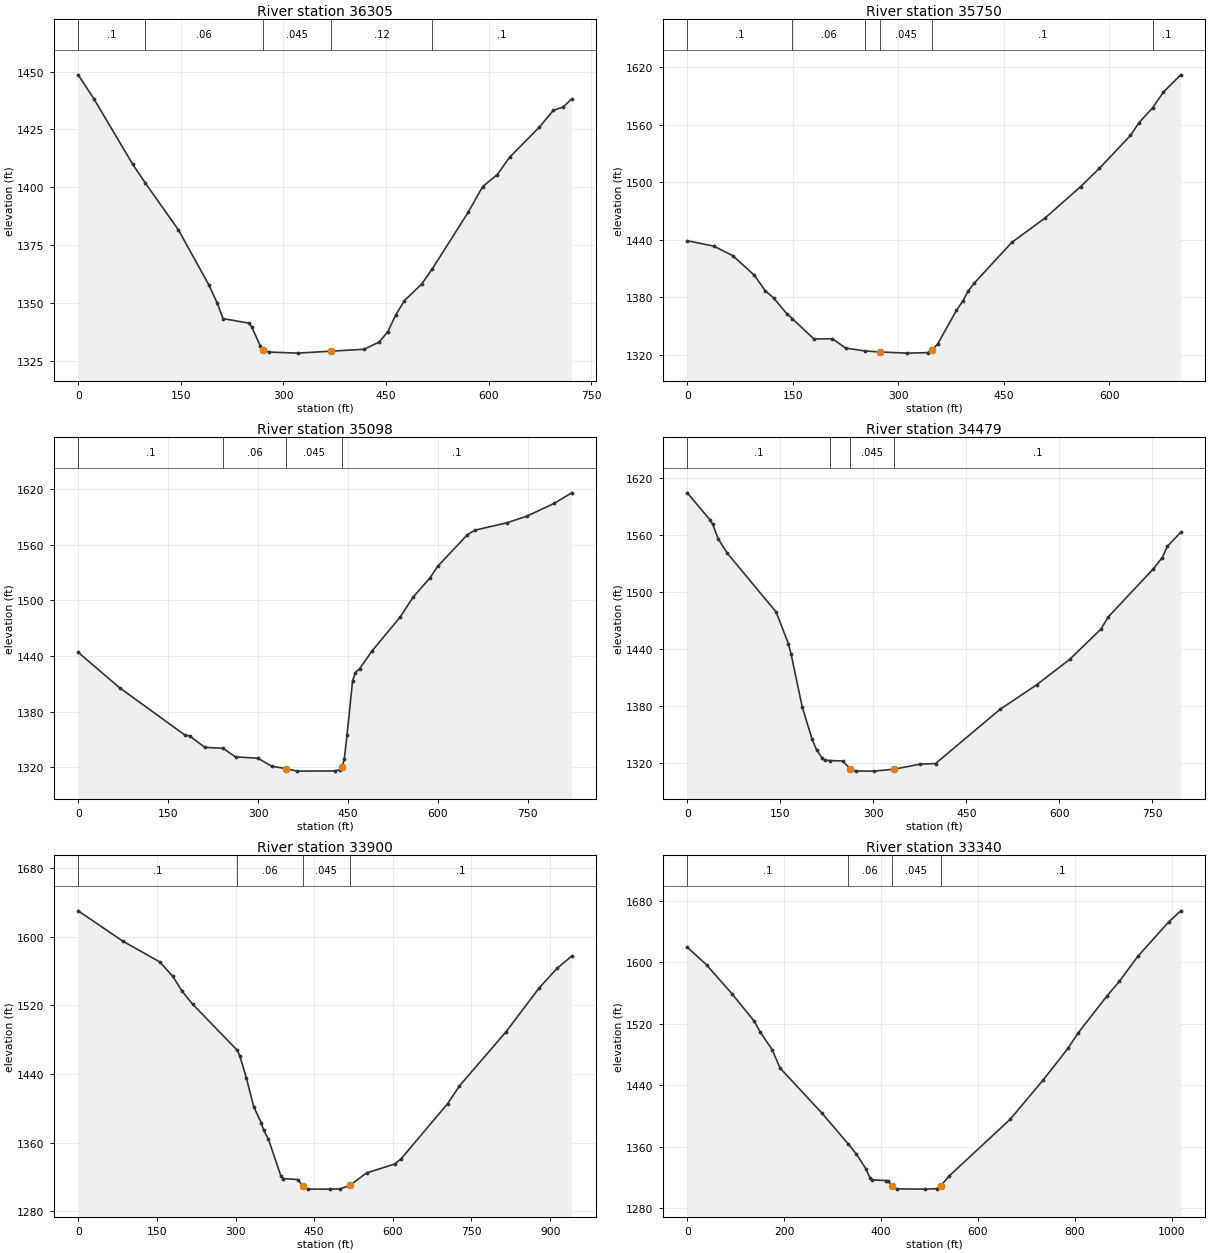
Type RM Length L Ch R = 1 ,36305   ,459.3,554.9,610.4
XS GIS Cut Line= 4
2454555.88611587669867.1989806222454621.71976337669739.920595448
2454753.38705838669336.1408907582454814.83179605669195.695776083
#Sta/Elev= 30
       0 1448.58    22.9 1438.23    79.5 1410.02   97.791401.976   146.6 1381.55
   190.7 1357.98   203.3 1349.95   211.7 1343.25   249.6 1341.33   253.8 1339.59
   266.4 1331.33   270.6 1329.73     279 1328.82   321.1 1328.36   370.2 1329.21
   417.9 1330.03     440 1333.17   452.7 1337.68   464.1 1344.81   476.8 1351.01
     502 1358.18  517.661364.789     570 1389.18   591.3 1400.32   612.5 1405.44
   630.7    1413   674.2 1426.01   694.5 1433.21   709.1 1434.74   721.3 1438.17
#Mann= 5 ,-1 , 0
       0      .1       0   97.79     .06       0   270.6    .045       0
   370.2     .12       0  517.66      .1       0
Bank Sta=270.6,370.2
XS Rating Curve= 0 ,0
Exp/Cntr(USF)=0,0
Exp/Cntr=0.3,0.1

Type RM Length L Ch R = 1 ,35750   ,531.6,651.7,705.8
XS GIS Cut Line= 4
2454801.66506655670047.1442837982454893.83217305669998.866275629
2455196.66695157669858.4211609542455442.44590225669761.865144615
#Sta/Elev= 30
       0 1438.96    37.3 1433.39    64.4 1423.52    95.4 1402.96   110.7 1386.88
   122.8 1379.21     142 1362.35  149.41 1357.57     180 1336.44   206.5 1336.59
   225.2 1326.92  252.561323.898   273.4 1322.89   312.3 1321.63   341.7 1322.11
   348.7 1325.12   356.4 1331.48   382.8 1366.25   391.7 1375.82   399.9 1386.92
   408.2 1394.74   461.6 1437.21   508.9 1462.67   559.4 1495.41   586.2 1514.54
   630.4 1548.87   642.7 1562.33   661.8 1577.69   677.2 1594.06   701.9 1612.16
#Mann= 6 ,-1 , 0
       0      .1       0  149.41     .06       0  252.56      .1       0
   273.4    .045       0   348.7      .1       0   661.8      .1       0
Bank Sta=273.4,348.7
XS Rating Curve= 0 ,0
Exp/Cntr(USF)=0,0
Exp/Cntr=0.3,0.1

Type RM Length L Ch R = 1 ,35098   ,688.5,618.8,544
XS GIS Cut Line= 4
2454696.33123054670354.3679721492454836.77634522670415.812709819
2455170.33349257670613.3136523312455442.44590225670687.925119502
#Sta/Elev= 30
       0 1443.97      69 1405.76   177.4 1355.06   186.2  1353.6   211.4 1341.45
  241.081340.552   262.5  1331.2   299.7 1329.79   322.9 1321.11   346.8 1318.54
   364.8 1315.85   428.5 1316.09   437.3 1317.48   440.2 1319.99   443.8 1328.81
   448.4 1354.46   457.7 1413.46   462.4 1422.21   469.4 1426.29   490.3 1445.61
   536.6 1481.66   558.8 1503.61     587 1524.45   599.4 1536.57   649.2 1570.81
   661.6 1575.68   715.6 1583.75   748.7  1590.9   794.4 1604.76   823.1    1616
#Mann= 4 ,-1 , 0
       0      .1       0  241.08     .06       0   346.8    .045       0
   440.2      .1       0
Bank Sta=346.8,440.2
XS Rating Curve= 0 ,0
Exp/Cntr(USF)=0,0
Exp/Cntr=0.3,0.1

Type RM Length L Ch R = 1 ,34479   ,597.9,579.7,556.9
XS GIS Cut Line= 4
 2454599.7752142671197.0386601972454731.44250921671153.149561862
2455157.16676307671030.2600865212455363.44552525670973.204258685
#Sta/Elev= 30
       0 1604.63    36.9 1575.92    41.1 1571.45    49.5 1556.55    64.1  1541.4
   143.3 1479.16     163 1445.83   167.2 1435.46   185.3 1379.42   201.4 1345.18
   208.8  1333.7   217.2 1325.81   221.3 1323.34   230.21322.899   250.5 1322.39
   262.8 1314.29   271.3 1311.89   300.4 1311.75   333.9 1313.83   375.4 1319.06
   400.4 1319.72   504.4 1376.75   563.3 1402.53   616.7 1429.31   667.2  1461.2
     679 1474.08   751.7 1524.64   766.1 1536.52   774.4 1548.49   795.9 1563.06
#Mann= 4 ,-1 , 0
       0      .1       0   230.2     .06       0   262.8    .045       0
   333.9      .1       0
Bank Sta=262.8,333.9
XS Rating Curve= 0 ,0
Exp/Cntr(USF)=0,0
Exp/Cntr=0.3,0.1

Type RM Length L Ch R = 1 ,33900   ,543.5,559.3,575.2
XS GIS Cut Line= 4
2454770.94269771671859.7640450692455029.88837789671697.374381226
2455376.61225475671486.7067092142455582.89101692671385.761783042
#Sta/Elev= 30
       0 1629.98    84.6 1594.87   155.6 1570.42   180.4 1553.76   197.8 1536.65
   218.1 1521.36  303.49 1467.52   308.1  1461.2   320.7  1435.4   334.7 1401.96
   348.8 1383.48   353.5 1374.75   362.8 1364.16   386.2  1321.8   390.9 1318.28
   418.7  1317.1   428.3 1309.74   437.7 1306.01   479.8 1305.94   498.6 1306.13
   517.7 1310.21     550 1324.85   603.2 1335.06   615.6 1341.06   704.5  1405.5
   727.1 1426.18   816.2 1489.34   878.5  1539.8   913.1 1562.94     941  1577.2
#Mann= 4 ,-1 , 0
       0      .1       0  303.49     .06       0   428.3    .045       0
   517.7      .1       0
Bank Sta=428.3,517.7
XS Rating Curve= 0 ,0
Exp/Cntr(USF)=0,0
Exp/Cntr=0.3,0.1

Type RM Length L Ch R = 1 ,33340   ,416.9,471,504.5
XS GIS Cut Line= 4
2454964.05473039 672228.432471092455271.27841874672158.209913752
2455591.66883659 672057.264987582455938.39271344 671934.37551224
#Sta/Elev= 30
       0 1619.52    39.7 1596.62      93 1558.35   138.2 1523.25   150.5 1509.25
   175.1 1486.23   191.5 1462.31   277.7 1403.74  331.991363.631   349.3  1350.1
   369.1  1330.7   377.5 1319.02   381.1 1316.57     411 1315.79   415.2 1314.54
   422.6 1309.05     432 1304.88   490.7 1304.58   515.1 1305.16   523.6 1309.02
   540.6 1321.57   667.1 1395.82     735 1446.82   785.9 1487.79   807.1 1507.98
   866.5 1556.02     892    1575   930.2 1607.61   993.8 1652.37  1018.9 1666.95
#Mann= 4 ,-1 , 0
       0      .1       0  331.99     .06       0   422.6    .045       0
   523.6      .1       0
Bank Sta=422.6,523.6
XS Rating Curve= 0 ,0
Exp/Cntr(USF)=0,0
Exp/Cntr=0.3,0.1

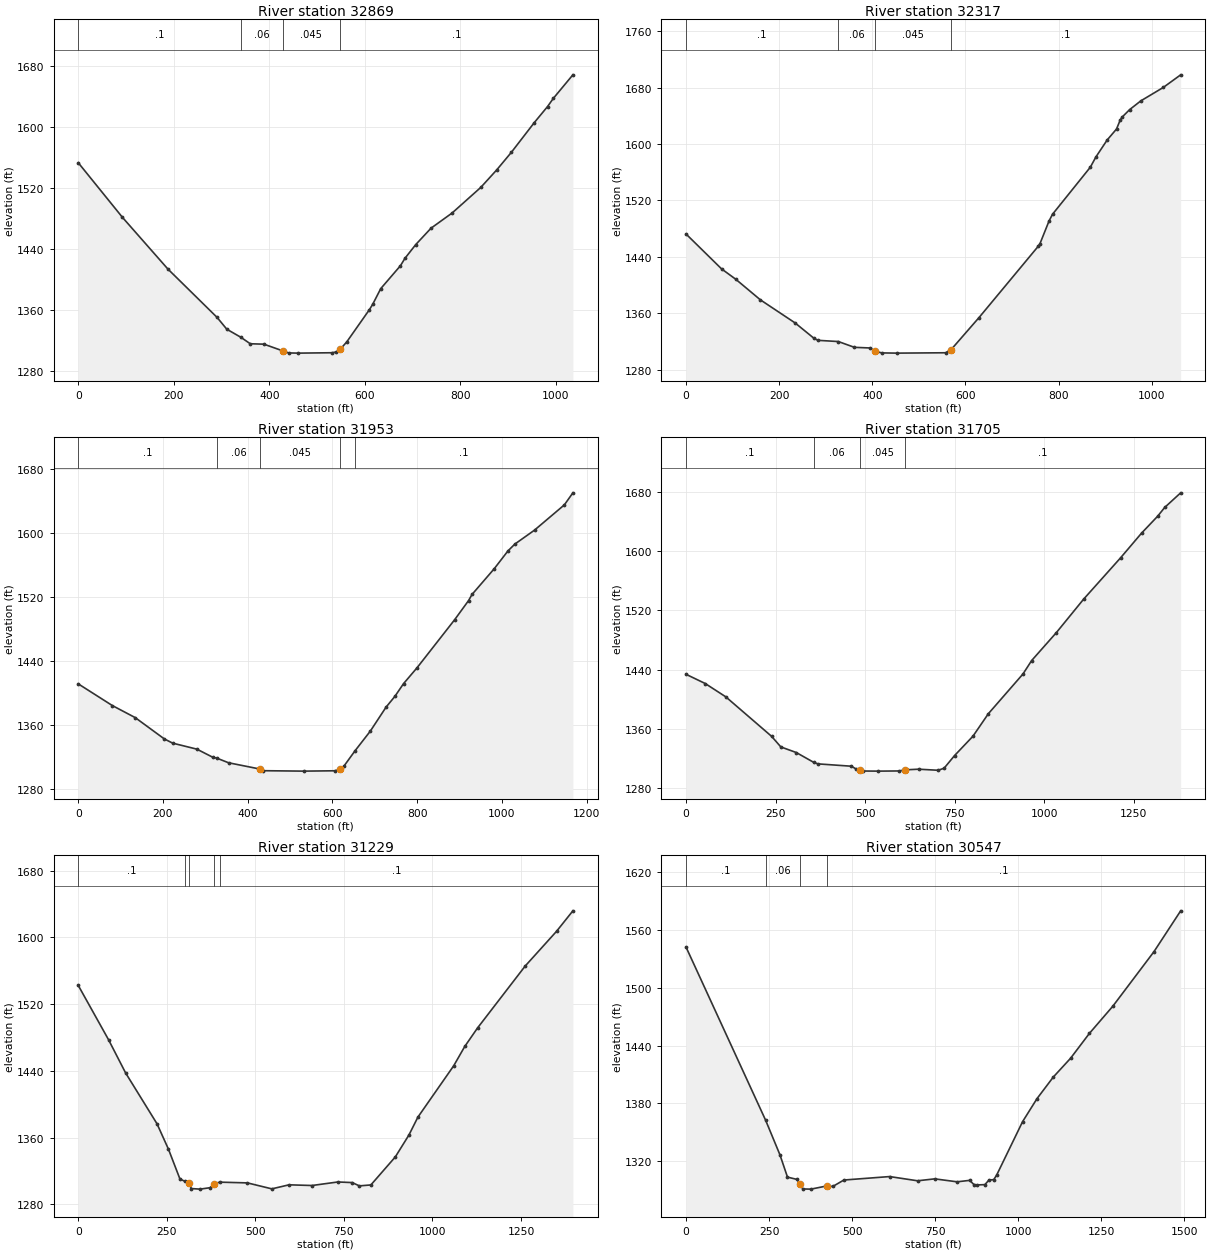
Type RM Length L Ch R = 1 ,32869   ,548.7,552.2,557.1
XS GIS Cut Line= 4
2454977.22145989 672461.04469227 2455227.3893204672526.878339773
2455626.78011526672610.2676266112455995.44854128672592.711987277
#Sta/Elev= 30
       0 1553.51    92.6 1481.72   187.7 1413.91   290.7  1350.4   311.1 1334.87
   340.21324.417   360.2 1315.78   388.8 1315.25   428.3 1306.45   440.7 1303.75
     461 1303.49   531.8    1304     540 1304.97   548.2 1308.29   562.4 1318.36
   609.7  1360.6   616.5  1367.5   633.4 1388.19   674.7 1418.29   684.1 1427.98
   706.7 1446.03   738.7 1467.56   782.8 1487.47   842.9 1521.13   876.3 1544.12
   906.9 1567.15     955 1606.26   982.7 1627.29     995 1638.18  1035.8 1668.98
#Mann= 4 ,-1 , 0
       0      .1       0   340.2     .06       0   428.3    .045       0
   548.2      .1       0
Bank Sta=428.3,548.2
XS Rating Curve= 0 ,0
Exp/Cntr(USF)=0,0
Exp/Cntr=0.3,0.1

Type RM Length L Ch R = 1 ,32317   ,362.6,363.8,359.7
XS GIS Cut Line= 4
2454841.16525505672943.8247739642455047.44401723673035.991880469
2455455.61263175673145.7146263092455868.17015611673176.436995144
#Sta/Elev= 30
       0 1472.22    76.2 1422.79   106.9 1407.97   159.5  1378.9   234.3 1346.04
   274.9 1324.17   283.3  1321.4  327.091319.675   361.6 1311.47     395 1310.57
   406.6 1305.86   420.3 1303.56   453.1 1303.25   557.4 1303.77     569 1308.06
   629.3 1353.79     756 1454.55     760 1458.42   779.5 1490.61     787 1500.24
   868.3 1567.08   880.3 1581.65   904.4 1605.62   924.5 1621.21   932.5 1634.07
   936.5 1638.09   952.6 1648.69   976.6  1661.1  1024.8 1680.12  1062.3 1698.08
#Mann= 4 ,-1 , 0
       0      .1       0  327.09     .06       0   406.6    .045       0
     569      .1       0
Bank Sta=406.6,569
XS Rating Curve= 0 ,0
Exp/Cntr(USF)=0,0
Exp/Cntr=0.3,0.1

Type RM Length L Ch R = 1 ,31953   ,225.4,248.2,234.1
XS GIS Cut Line= 4
2454705.10905021673229.1039131472454902.60999272673369.549027822
2455416.11244325673505.6052326632455806.72541844 673452.93831466
#Sta/Elev= 30
       0 1411.63    80.5 1384.59   134.4  1369.6   203.2    1343   222.9 1337.75
   280.1 1330.25     317 1320.31   327.61318.954   354.8 1313.29     430 1305.35
     437  1303.4   532.1 1302.87   606.7 1303.31   617.8 1305.36   627.3  1309.2
  653.871328.566   689.4 1352.69   726.6  1382.6   747.4 1396.02     768 1411.99
   799.7 1431.66   888.6 1491.65   921.5 1515.54   929.6 1523.12   982.1 1555.24
  1014.4 1577.39  1030.8 1585.95  1077.1 1603.29  1147.6 1634.81  1167.7  1649.8
#Mann= 5 ,-1 , 0
       0      .1       0   327.6     .06       0     430    .045       0
   617.8    .025       0  653.87      .1       0
Bank Sta=430,617.8
XS Rating Curve= 0 ,0
Exp/Cntr(USF)=0,0
Exp/Cntr=0.3,0.1

Type RM Length L Ch R = 1 ,31705   ,474.2,476.6,284.4
XS GIS Cut Line= 4
2454569.05284537673461.7161343272454964.05473039673619.716888336
2455319.55642691673725.0507243422455898.89252494673646.050347337
#Sta/Elev= 30
       0 1433.59    53.5 1421.15   110.9 1403.16   238.8 1349.78   264.6 1335.48
   307.7 1327.91  356.011314.736     368 1312.59   461.6 1309.41   474.1 1305.83
   486.6 1304.64     495 1302.93   536.4 1302.78   595.1 1303.02   611.8 1304.52
   649.3 1305.39   703.6 1303.94   720.3 1306.68   749.5 1323.74     801 1349.99
   843.8 1380.28   940.7  1434.1   964.9 1452.24  1033.6 1489.82    1110 1535.19
  1213.1    1591  1271.8 1624.42  1316.2 1646.99  1336.4 1659.11  1380.9 1678.81
#Mann= 4 ,-1 , 0
       0      .1       0  356.01     .06       0   486.6    .045       0
   611.8      .1       0
Bank Sta=486.6,611.8
XS Rating Curve= 0 ,0
Exp/Cntr(USF)=0,0
Exp/Cntr=0.3,0.1

Type RM Length L Ch R = 1 ,31229   ,702.3,681.6,530.5
XS GIS Cut Line= 4
2454490.05246836674076.1635110282454735.83141904674045.441142193
2455354.66770558673944.4962160212455850.61451677673782.106552178
#Sta/Elev= 30
       0 1542.36    85.4 1477.34   133.7 1437.42   222.4 1376.39   254.7 1345.95
   287.1 1310.19   300.41307.599   311.7 1305.12   319.5 1298.76   343.9 1298.08
   372.2 1299.79   384.4 1304.82  399.71 1306.45   477.6 1305.56   546.5 1298.41
   595.1 1303.24     660 1302.43   732.9 1306.66   773.5 1305.94   793.7 1301.98
   826.2  1303.1   895.1 1336.66   933.7 1363.02     959 1384.46  1060.1 1446.04
  1091.3  1469.2  1127.3 1491.34    1262 1565.69  1350.4 1607.28  1396.6 1631.87
#Mann= 5 ,-1 , 0
       0      .1       0   300.4     .06       0   311.7    .045       0
   384.4     .06       0  399.71      .1       0
Bank Sta=311.7,384.4
XS Rating Curve= 0 ,0
Exp/Cntr(USF)=0,0
Exp/Cntr=0.3,0.1

Type RM Length L Ch R = 1 ,30547   ,975.2,911.4,609.8
XS GIS Cut Line= 4
2454792.88724688674839.8338220722455021.11055823674703.777617231
2455618.00229559674330.7202813762456052.50436912674045.441142193
#Sta/Elev= 30
       0 1541.96  239.651362.519   282.5  1326.9   305.4 1303.64   334.3 1301.23
   343.1  1296.3   351.7 1291.37   376.1 1291.19   423.3 1294.45   441.7 1293.93
   475.2 1300.62     613 1304.21   697.1 1299.83   748.8 1301.83   816.2 1298.77
   853.9 1300.27   866.7 1295.97   876.1 1295.54   899.7 1295.85   911.9  1300.5
   926.5 1301.05   935.2  1305.7  1013.3 1361.11  1056.7 1384.95  1105.8 1407.33
  1157.8  1426.8  1214.5 1452.57  1284.9 1480.68  1409.1 1537.35  1489.4  1579.6
#Mann= 4 ,-1 , 0
       0      .1       0  239.65     .06       0   343.1    .045       0
   423.3      .1       0
Bank Sta=343.1,423.3
XS Rating Curve= 0 ,0
Exp/Cntr(USF)=0,0
Exp/Cntr=0.3,0.1

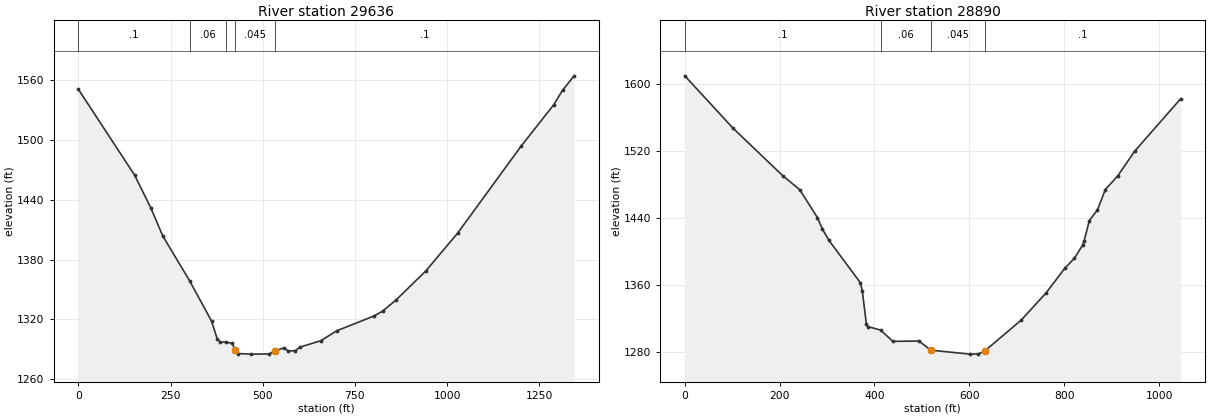
Type RM Length L Ch R = 1 ,29636   ,712.8,745.7,769.7
XS GIS Cut Line= 4
2455890.11470528675414.7810102722455916.44816428675133.890780922
2455938.39271344674541.3879533882456065.67109862674089.330240529
#Sta/Elev= 30
       0 1550.64   152.6 1464.62   196.7  1431.7   228.9  1403.7  302.111358.592
   361.2  1318.5   377.2 1300.06   385.2 1297.49  401.461297.254   417.2 1296.25
   425.2 1289.51   433.2  1285.9   469.3 1285.31   517.3 1285.47   533.3  1288.4
   557.3 1291.58   569.3 1288.52   588.3 1288.75   601.3 1292.37   657.4 1298.71
   701.4 1308.79   801.5 1323.44   825.5 1328.46   861.5 1339.49   941.8 1368.39
  1028.5 1406.43    1201 1493.73  1288.8 1534.84    1314 1550.03  1344.7 1564.06
#Mann= 5 ,-1 , 0
       0      .1       0  302.11     .06       0  401.46      .1       0
   425.2    .045       0   533.3      .1       0
Bank Sta=425.2,533.3
XS Rating Curve= 0 ,0
Exp/Cntr(USF)=0,0
Exp/Cntr=0.3,0.1

Type RM Length L Ch R = 1 ,28890   ,457.3,545.3,585.9
XS GIS Cut Line= 4
2456412.39497547675370.8919119362456574.78463931675085.612772753
2456745.95212282674651.1106992282456943.45306534674497.498855053
#Sta/Elev= 30
       0 1609.64   101.3 1547.48     207 1490.36   242.2 1474.05   279.7 1440.72
     290  1427.2   303.8  1413.7   369.9 1363.31   374.2 1353.81   382.8 1314.26
   385.8 1310.88   412.81306.649   438.7 1293.21   493.8 1293.66   518.5  1282.7
   601.7 1278.01   619.2 1278.24   632.1 1281.59   709.5 1318.63   761.1 1350.53
   801.3 1380.23   821.7  1392.4   838.7 1407.73   841.9 1412.49     853 1437.15
   870.1 1449.82   886.8 1474.16   912.9 1490.36   948.3 1519.67  1045.5 1582.28
#Mann= 4 ,-1 , 0
       0      .1       0   412.8     .06       0   518.5    .045       0
   632.1      .1       0
Bank Sta=518.5,632.1
XS Rating Curve= 0 ,0
Exp/Cntr(USF)=0,0
Exp/Cntr=0.3,0.1