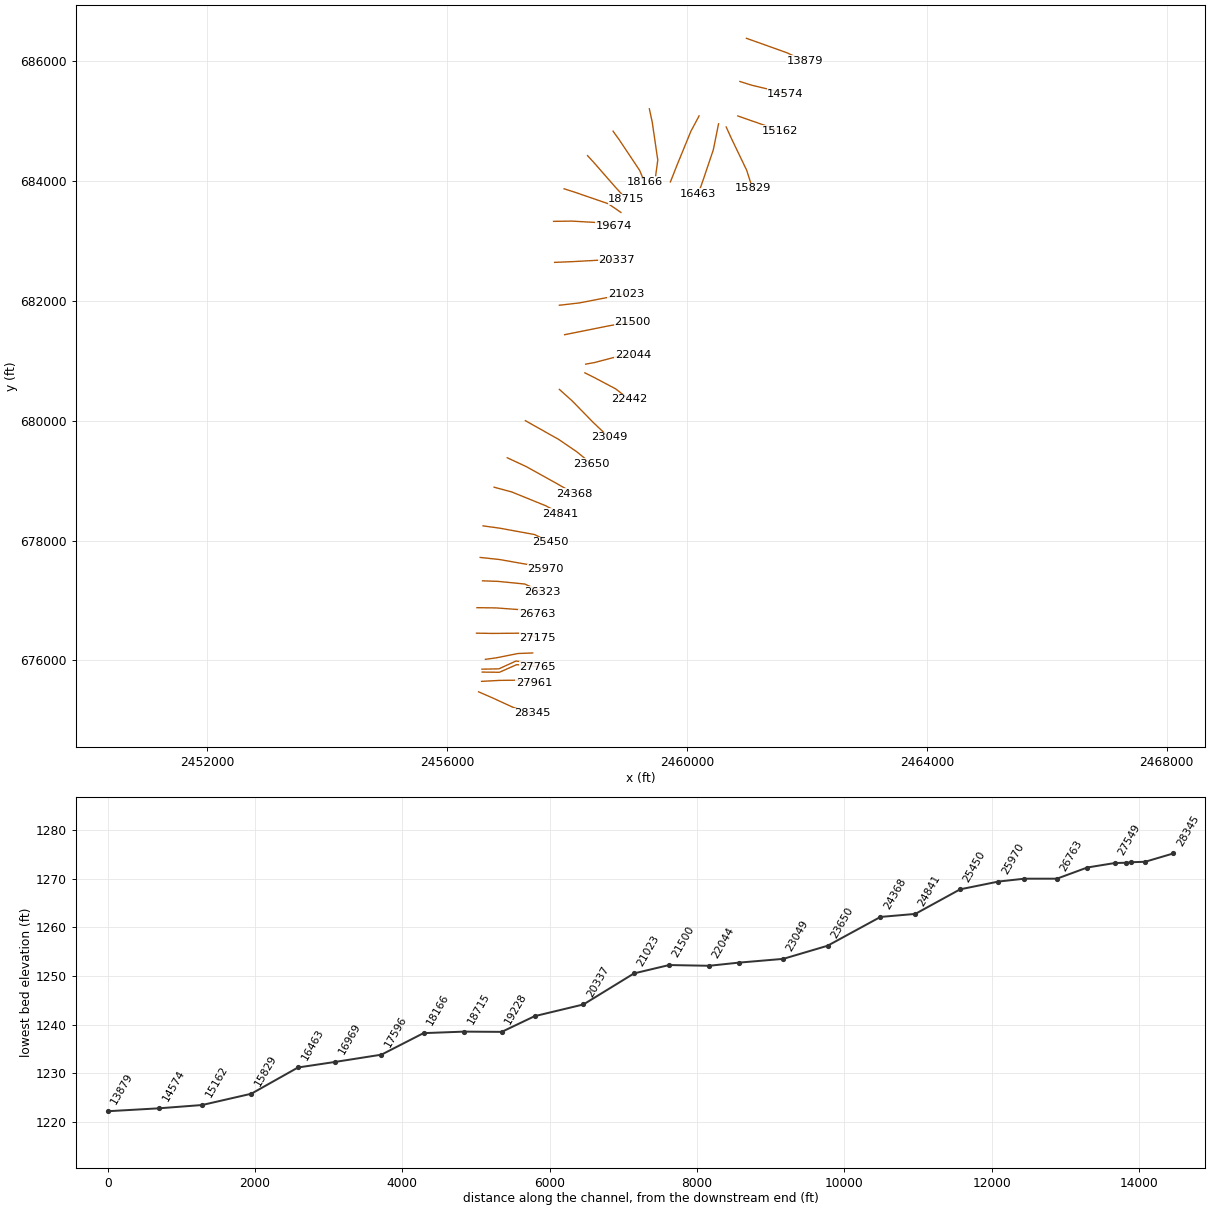
HEC-RAS study SBPOTOMC.prj: SBPOTOMC

--- SBPOTOMC.g01 (geometry) --- (continued)

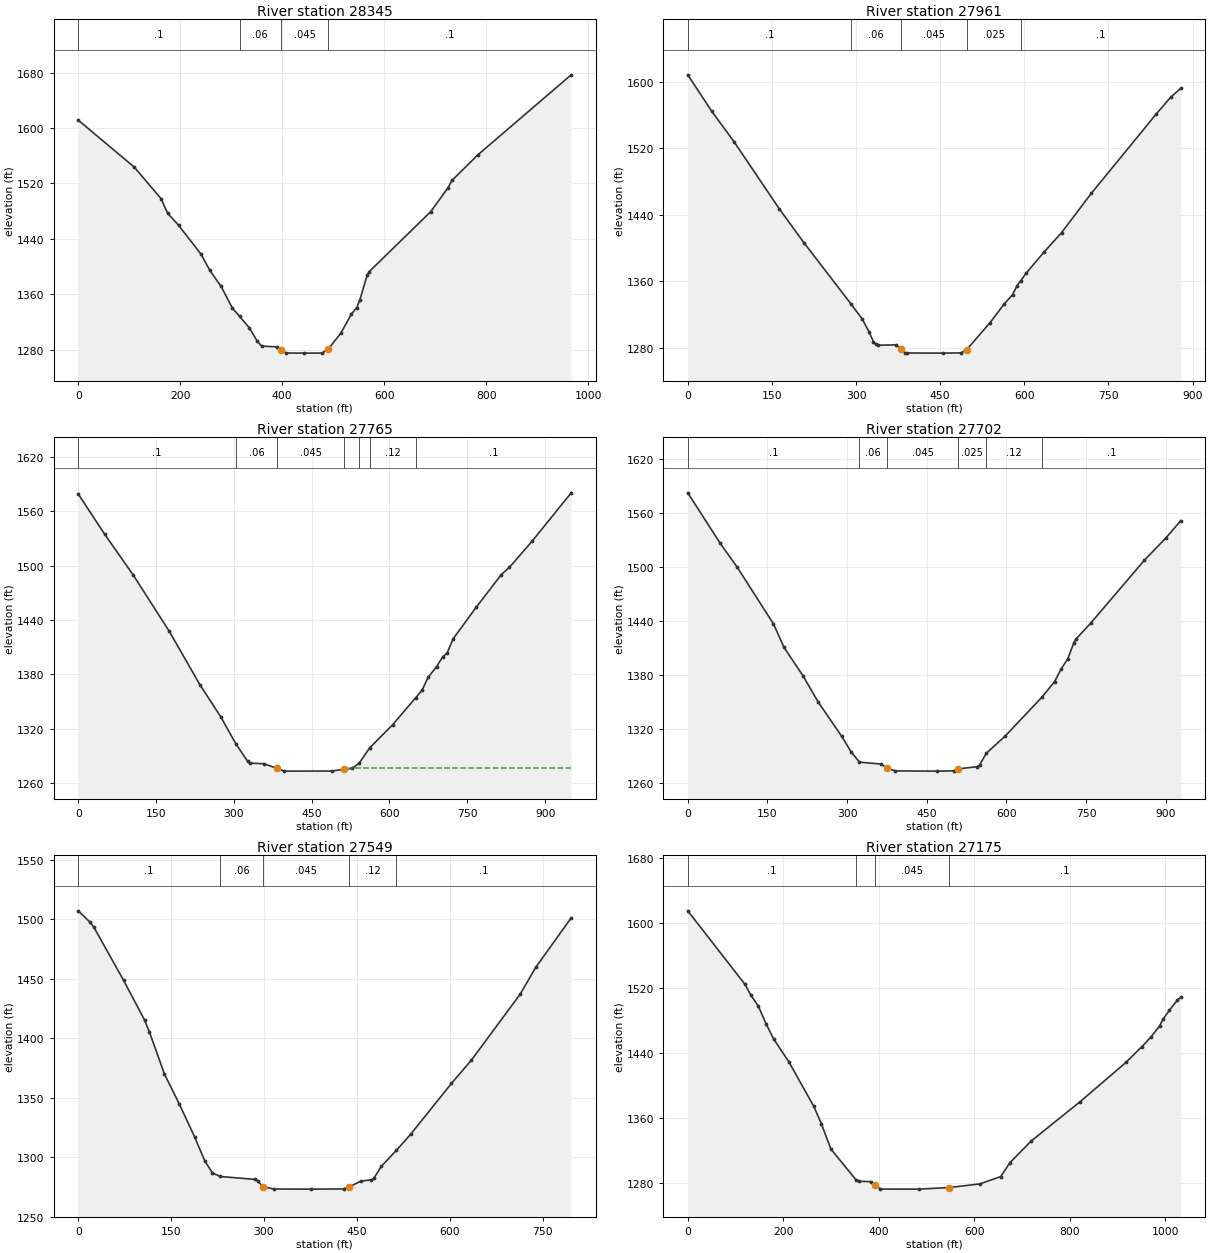
Type RM Length L Ch R = 1 ,28345   ,348.4,384,414.5
XS GIS Cut Line= 4
2456522.11772131675476.2257479422456763.50776216675370.891911936
2457097.06490951 675217.280067762457417.45532736675116.335141588
#Sta/Elev= 30
       0 1611.35   109.8 1543.66   162.2 1498.28   175.3 1477.02   197.1 1459.41
   240.7 1418.07   258.2 1394.47   280.1 1371.49   302.2  1340.3  316.25 1328.39
   335.2 1311.95   350.6 1293.11   359.4 1285.47   389.4 1284.18   397.2 1280.22
   407.9  1275.4   443.1 1275.23   478.3 1275.34   490.4 1281.22   514.9 1303.99
   535.6 1331.67   546.2 1340.99   552.3 1352.35   566.4 1387.45   570.3 1392.64
   691.1 1479.31   724.6  1513.3     733 1524.48   783.3 1561.12   966.5 1676.69
#Mann= 4 ,-1 , 0
       0      .1       0  316.25     .06       0   397.2    .045       0
   490.4      .1       0
Bank Sta=397.2,490.4
XS Rating Curve= 0 ,0
Exp/Cntr(USF)=0,0
Exp/Cntr=0.3,0.1

Type RM Length L Ch R = 1 ,27961   ,159.8,196.1,233.4
XS GIS Cut Line= 4
2456572.10598675675650.6594691372456872.17628682675666.792280969
2457159.34033743675670.0188433352457446.50438804 675621.62040784
#Sta/Elev= 30
       0 1608.73    42.7 1564.91    82.8  1527.9   163.4 1447.06   206.9 1406.72
  291.331332.433   311.1 1314.57   323.1  1299.2   331.1 1287.22   335.1 1284.29
   339.1 1283.12   371.1 1283.38   379.9 1278.97   387.1 1274.09   391.1 1273.68
   455.1 1273.51   487.1  1273.8     497 1277.51   539.1 1310.37   564.2 1332.72
   579.1 1344.03   587.1 1354.77  593.731360.812   603.3 1369.89     635 1395.17
   666.3 1418.55   719.7  1466.2   834.5 1560.97   860.6 1581.51   878.9 1592.47
#Mann= 5 ,-1 , 0
       0      .1       0  291.33     .06       0   379.9    .045       0
     497    .025       0  593.73      .1       0
Bank Sta=379.9,497
XS Rating Curve= 0 ,0
Exp/Cntr(USF)=0,0
Exp/Cntr=0.5,0.3

Type RM Length L Ch R = 1 ,27765   ,60,62.7,63.7
XS GIS Cut Line= 4
2456583.56245898675805.3939854612456870.28531837675802.227425537
2457157.13971707 675929.579600812457505.23352403675897.561091966
#Sta/Elev= 30
       0 1579.04    51.2 1534.42   105.9 1489.78   175.2 1427.83   235.1 1368.18
   274.7 1333.34  304.161303.265   326.6 1284.24     331 1282.21   357.4 1281.58
   383.5  1276.5   396.7 1273.41   488.6  1273.5   511.9 1275.38     528 1276.42
  541.391282.094  561.921299.107   606.2 1324.67  650.461354.296   662.5 1362.31
   674.5 1376.83   690.6 1388.53   702.6 1399.37   710.7 1403.25   722.7 1419.31
   766.9  1453.9   815.1 1489.78   831.2 1498.06   875.4 1527.27   950.2  1580.2
#Mann= 7 ,-1 , 0
       0      .1       0  304.16     .06       0   383.5    .045       0
   511.9    .025       0  541.39      .1       0  561.92     .12       0
  650.46      .1       0
#XS Ineff= 2 , 0
             374  1276.5     520          1276.5
Permanent Ineff=
       F       F
Bank Sta=383.5,511.9
XS Rating Curve= 0 ,0
Exp/Cntr(USF)=0,0
Exp/Cntr=0.5,0.3

Type RM Length L Ch R = 1 ,27702   ,174.7,153.2,131.8
XS GIS Cut Line= 4
2456577.60760399675854.3426448352456859.67847492675859.379624673
2457146.78632569675990.3411004612457474.19001516675945.008281919
#Sta/Elev= 30
       0 1582.89    61.1 1526.75    93.2  1500.1   161.2 1437.27   181.2 1411.05
   217.2 1379.13   245.3 1350.43   289.9 1311.94   308.2  1294.2  323.231283.355
   364.6 1281.09   374.6 1276.53     391 1273.55   470.1 1273.31   500.9 1273.65
   509.7  1275.9   544.9  1278.2   549.3  1279.9  562.061293.189   597.7 1312.35
  667.39 1355.96   690.5 1372.76   702.6 1386.54   715.5  1398.3   726.9 1416.08
   730.9 1420.27   759.2 1438.31   859.6 1507.86   900.5 1532.87   928.2 1551.91
#Mann= 6 ,-1 , 0
       0      .1       0  323.23     .06       0   374.6    .045       0
   509.7    .025       0  562.06     .12       0  667.39      .1       0
Bank Sta=374.6,509.7
XS Rating Curve= 0 ,0
Exp/Cntr(USF)=0,0
Exp/Cntr=0.5,0.3

Type RM Length L Ch R = 1 ,27549   ,393.3,373.3,357
XS GIS Cut Line= 4
2456636.63723408676018.4875789032456804.41847713676041.073515468
2457178.69971163676115.2844498942457423.91845147676124.964136994
#Sta/Elev= 30
       0 1506.96    18.3 1497.84    25.3  1493.2    73.4 1448.53   107.1 1415.33
   115.1 1405.15   139.4 1369.78   163.6 1344.43     188 1317.16   204.3 1297.19
   216.5 1287.01  229.331283.871   285.8 1281.42   289.9 1280.24   298.1 1275.37
   315.8 1273.34   375.6 1273.25   428.6 1273.39   436.7 1274.83   457.1 1280.14
   473.4 1280.94   477.5  1282.3   489.7 1292.46  513.911305.804     537 1319.34
   602.9 1362.06     635  1381.5   713.9 1436.98   739.1 1459.53   796.3 1501.08
#Mann= 5 ,-1 , 0
       0      .1       0  229.33     .06       0   298.1    .045       0
   436.7     .12       0  513.91      .1       0
Bank Sta=298.1,436.7
XS Rating Curve= 0 ,0
Exp/Cntr(USF)=0,0
Exp/Cntr=0.3,0.1

Type RM Length L Ch R = 1 ,27175   ,419.9,412.2,400.9
XS GIS Cut Line= 4
2456487.00644264676454.9526408312456750.34103266676450.563730997
2457246.28784385676454.9526408312457509.62243387 676380.34117366
#Sta/Elev= 30
       0 1614.54   119.8 1524.22   131.8 1511.24   147.8 1497.45   163.8 1475.93
   179.8 1457.15   211.8  1428.9   263.8 1374.41     280 1352.76   299.8 1321.68
   352.11284.111   359.8 1281.89   383.8 1281.56   392.6  1277.5   403.8 1272.39
   483.8 1272.33   547.8  1274.3   611.8 1278.71   655.8 1287.76   675.1 1304.86
   719.5 1331.45   822.2 1379.87   918.5 1428.36   951.1 1447.28   970.3  1459.2
   988.5  1472.9   996.2 1481.55  1009.2 1492.34  1025.9 1504.82    1033 1508.16
#Mann= 4 ,-1 , 0
       0      .1       0   352.1     .06       0   392.6    .045       0
   547.8      .1       0
Bank Sta=392.6,547.8
XS Rating Curve= 0 ,0
Exp/Cntr(USF)=0,0
Exp/Cntr=0.3,0.1

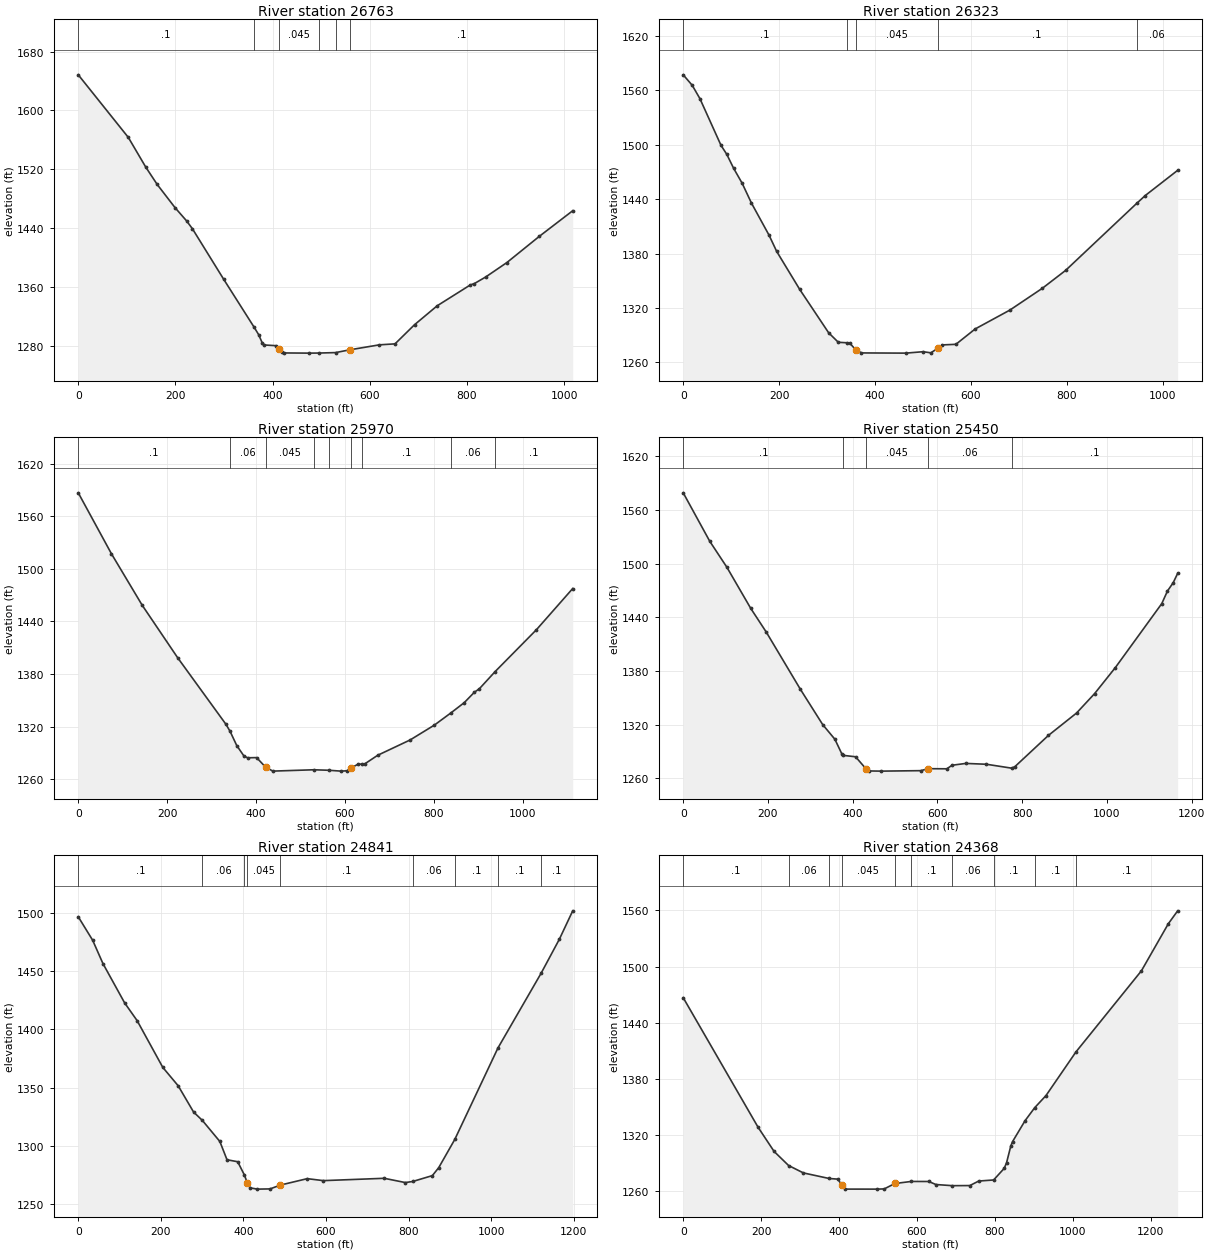
Type RM Length L Ch R = 1 ,26763   ,441.8,440.4,437.1
BEGIN DESCRIPTION:
Mannings N in channel placed 0.1 because of island in the channel
END DESCRIPTION:
XS GIS Cut Line= 4
2456495.78426231676880.6768946892456816.17468016676876.287984855
2457233.12111435 676845.56561602 2457500.8446142676766.565239015
#Sta/Elev= 30
       0 1648.31     103 1563.24   138.9 1522.88   162.5 1499.24     199  1467.9
     223 1449.73     235 1439.02     299 1370.72  361.83 1305.33   371.1  1295.3
   379.1 1283.23   383.2  1281.1   407.2 1280.14   413.8 1275.82   419.3 1271.27
   423.3 1270.28   475.4 1270.03   495.5 1270.15   529.5 1270.75   559.5 1274.62
   619.8  1281.3   651.9 1282.62     692  1308.6   738.7 1334.39   806.9 1362.73
   815.3 1364.61   838.6 1373.57     882 1393.09   948.7 1428.68  1017.6 1463.58
#Mann= 6 ,-1 , 0
       0      .1       0  361.83     .06       0   413.8    .045       0
   495.5      .1       0   529.5    .045       0   559.5      .1       0
Bank Sta=413.8,559.5
XS Rating Curve= 0 ,0
Exp/Cntr(USF)=0,0
Exp/Cntr=0.3,0.1

Type RM Length L Ch R = 1 ,26323   ,359.4,352.7,342
XS GIS Cut Line= 4
2456587.95136881677328.3456977142456842.50813916677319.567878047
2457290.17694219677275.6787797112457588.62281087677144.011484704
#Sta/Elev= 30
       0 1577.29    18.8 1565.68    34.8 1551.01    78.8 1499.39    90.8 1489.52
     105 1474.17   122.9 1457.51   142.3 1435.62   178.9 1400.26   194.9 1382.24
   242.9 1340.32   303.2 1292.44   323.3    1282  341.071281.467   347.4 1280.85
   359.4  1273.9   371.5 1270.25   463.9 1270.03   500.1  1271.6   516.2 1270.36
   530.1 1275.18   540.3 1279.11   568.4 1279.76   608.6 1296.73     681 1317.58
   748.9 1341.73     797 1361.33  945.461435.446   963.1 1444.02  1030.7 1471.87
#Mann= 5 ,-1 , 0
       0      .1       0  341.07     .06       0   359.4    .045       0
   530.1      .1       0  945.46     .06       0
Bank Sta=359.4,530.1
XS Rating Curve= 0 ,0
Exp/Cntr(USF)=0,0
Exp/Cntr=0.3,0.1

Type RM Length L Ch R = 1 ,25970   ,518.2,520.3,520.8
BEGIN DESCRIPTION:
Mannings N in channel placed 0.1 because of island in the channel
END DESCRIPTION:
XS GIS Cut Line= 4
2456548.45118031677718.958672903  2456873.230508677683.847394234
2457369.17731919677596.0691975632457641.28972887677521.457730392
#Sta/Elev= 30
       0 1586.62    74.7 1517.13   143.7 1458.62   223.5 1398.78   332.3 1322.79
  341.521314.853   356.6 1298.57   372.9 1286.58     381 1284.66   401.3 1284.84
   421.6 1273.91   437.9 1269.46   529.7 1270.98   564.3 1270.41   591.1 1269.44
   604.4 1269.82   613.6 1272.92   628.8 1277.17   639.5 1277.62   645.1 1277.88
   673.9 1287.56   746.6 1304.95   801.2 1321.89  838.191335.697   868.4 1347.47
   891.2 1359.33   902.5 1363.35  938.08 1382.97  1030.9 1430.63  1112.5 1477.56
#Mann= 9 ,-1 , 0
       0      .1       0  341.52     .06       0   421.6    .045       0
   529.7      .1       0   564.3    .045       0   613.6     .12       0
   639.5      .1       0  838.19     .06       0  938.08      .1       0
Bank Sta=421.6,613.6
XS Rating Curve= 0 ,0
Exp/Cntr(USF)=0,0
Exp/Cntr=0.3,0.1

Type RM Length L Ch R = 1 ,25450   ,615,609.1,536.9
XS GIS Cut Line= 4
2456596.72918848678245.6278529332456882.00832766678206.127664431
2457456.95551586678100.7938284252457720.29010588677969.126533417
#Sta/Elev= 30
       0 1579.16    62.6 1524.98     103 1495.93   159.5 1449.77   195.9 1423.44
   276.6 1359.31   329.2 1319.86   357.9 1303.51   374.1 1287.34  377.781285.461
   406.7  1283.9   431.1 1270.55   439.2 1268.03   467.7 1267.84   561.2 1268.37
   577.5 1270.58   622.2 1270.44   634.4 1274.42   666.9 1276.46   715.7 1275.52
  775.131271.146   782.8 1272.88   861.9 1307.82   928.2 1332.81   970.7 1354.48
  1019.9 1383.73  1129.4 1455.25  1142.8 1469.34  1156.3 1478.58  1166.9 1489.12
#Mann= 5 ,-1 , 0
       0      .1       0  377.78     .06       0   431.1    .045       0
   577.5     .06       0  775.13      .1       0
Bank Sta=431.1,577.5
XS Rating Curve= 0 ,0
Exp/Cntr(USF)=0,0
Exp/Cntr=0.3,0.1

Type RM Length L Ch R = 1 ,24841   ,478.8,472.4,434.7
XS GIS Cut Line= 4
2456781.06340149 678890.797598472457075.12036034678811.797221466
2457636.90081904678583.5739101192457891.45758939678451.906615112
#Sta/Elev= 30
       0 1496.56    34.9 1476.42    59.7 1456.46   112.3 1422.65   142.6  1407.4
   204.7 1367.29     242 1351.48   279.2 1328.99  300.531321.766   342.9 1303.68
   360.2 1287.99   386.1  1286.3  402.34 1274.89   409.3  1268.2   416.3 1263.87
   433.6 1262.78   464.5 1262.97   489.1 1266.23   554.5 1271.77   593.5 1270.07
   740.9 1272.08     792 1268.42  809.88 1269.34   857.5 1274.39   872.9 1281.21
  911.791305.428  1016.31383.937 1120.81 1448.08  1165.1 1477.35  1197.4 1501.69
#Mann= 9 ,-1 , 0
       0      .1       0  300.53     .06       0  402.34      .1       0
   409.3    .045       0   489.1      .1       0  809.88     .06       0
  911.79      .1       0  1016.3      .1       0 1120.81      .1       0
Bank Sta=409.3,489.1
XS Rating Curve= 0 ,0
Exp/Cntr(USF)=0,0
Exp/Cntr=0.3,0.1

Type RM Length L Ch R = 1 ,24368   ,666.2,718.1,655.6
XS GIS Cut Line= 4
2457000.50889317679382.3554998312457312.12149136679237.521475323
2457825.62394189 678952.242336142458119.68090074678785.463762464
#Sta/Elev= 30
       0 1466.77   192.1 1328.32   233.2 1302.47  270.461287.402   308.4 1279.49
  374.331273.541     397 1272.84   406.7 1266.53   415.3 1262.19   497.5 1262.16
   515.9  1262.4   543.4 1268.18   585.51270.365   630.3 1270.32   648.6 1267.07
  691.091265.851   735.6 1265.97   758.5  1270.8  796.681271.942     824 1284.43
   829.9 1290.39   840.8 1308.29   845.4 1313.03   877.4 1335.33  902.261349.271
   931.1 1362.18  1008.11408.887  1176.1 1495.57    1245  1545.8  1269.1 1559.65
#Mann= 10 ,-1 , 0
       0      .1       0  270.46     .06       0  374.33      .1       0
   406.7    .045       0   543.4    .025       0   585.5      .1       0
  691.09     .06       0  796.68      .1       0  902.26      .1       0
  1008.1      .1       0
Bank Sta=406.7,543.4
XS Rating Curve= 0 ,0
Exp/Cntr(USF)=0,0
Exp/Cntr=0.3,0.1

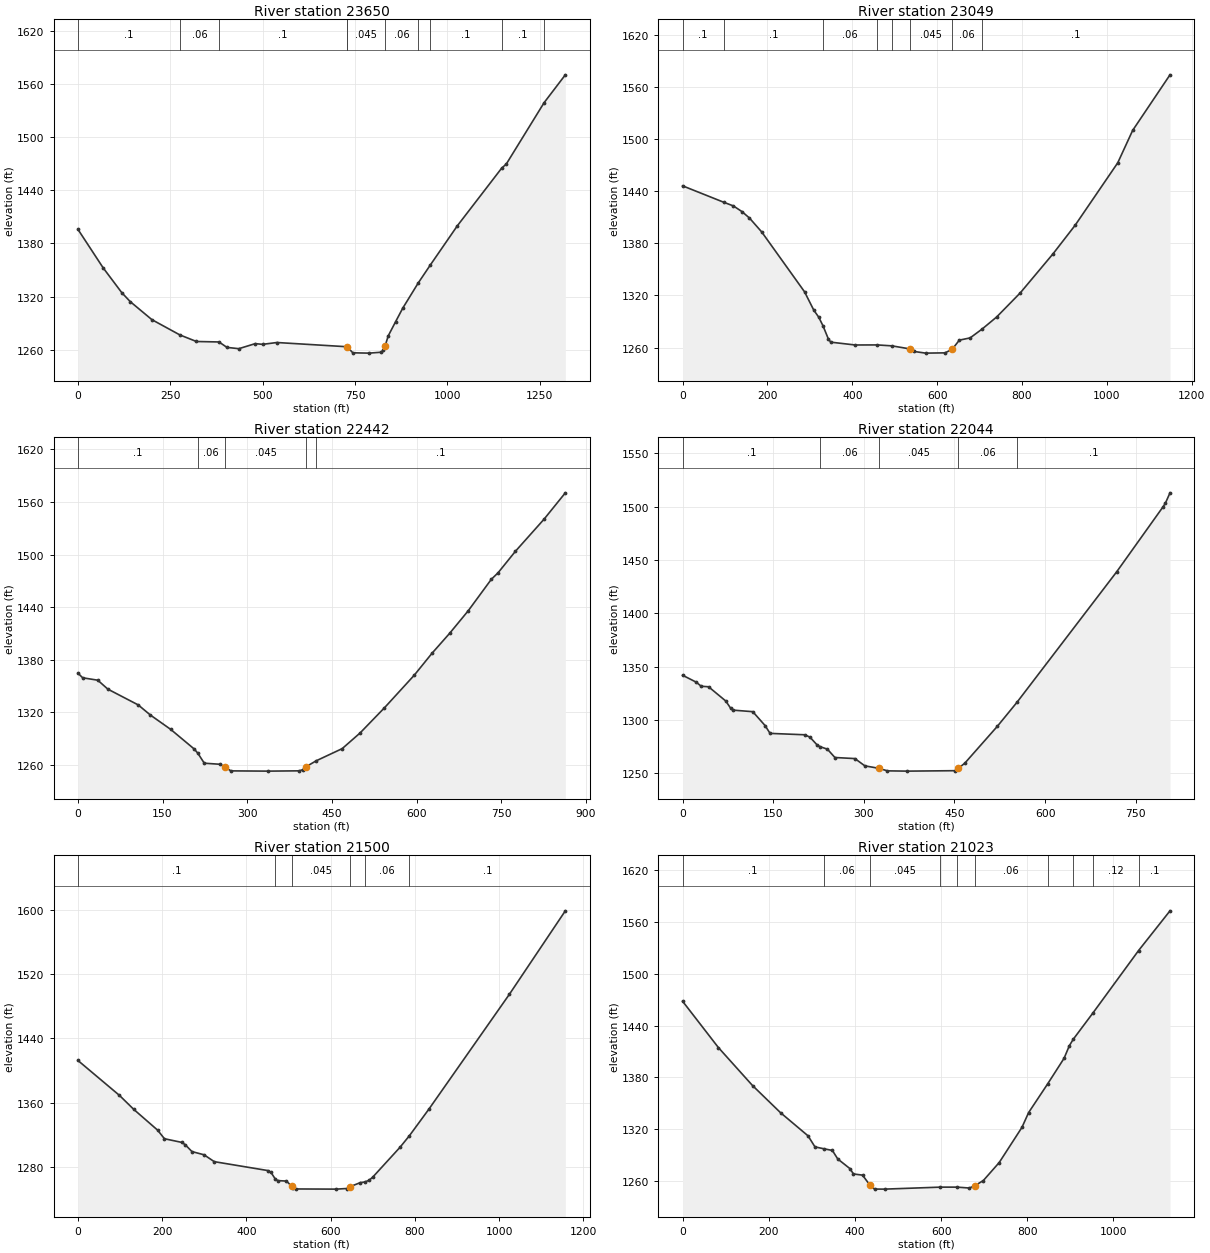
Type RM Length L Ch R = 1 ,23650   ,784,601.6,587.2
XS GIS Cut Line= 4
2457303.34367169680001.1917863672457856.34631072679689.579188182
2458159.18108924679483.3004260042458404.96003992679281.410573659
#Sta/Elev= 30
       0 1395.86    68.2 1352.48   118.7 1324.43   141.6 1314.32   200.2 1293.99
  276.041276.743   320.7 1269.35  381.861268.826   403.4 1262.69   435.5 1261.24
   479.9 1266.93   499.8 1266.14   538.6  1268.2  727.121263.464   729.6 1262.94
   744.1 1256.58   788.1 1256.23   821.6 1257.28   826.4 1259.37     831  1263.8
   839.9 1275.71   859.8 1291.66   879.6 1307.25   920.91335.237  954.251355.902
    1027 1399.88 1146.841464.816  1159.4 1469.49 1261.741538.695  1319.2  1570.1
#Mann= 10 ,-1 , 0
       0      .1       0  276.04     .06       0  381.86      .1       0
  727.12     .06       0   729.6    .045       0     831     .06       0
   920.9      .1       0  954.25      .1       0 1146.84      .1       0
 1261.74      .1       0
Bank Sta=729.6,831
XS Rating Curve= 0 ,0
Exp/Cntr(USF)=0,0
Exp/Cntr=0.3,0.1

Type RM Length L Ch R = 1 ,23049   ,558.3,606.9,638.9
XS GIS Cut Line= 4
2457869.51304022680523.4720565632458084.56962207680330.360023886
2458435.68240875679970.4694175322458694.62808893679724.690466851
#Sta/Elev= 30
       0 1446.04   97.131427.115   119.9 1422.88   140.1 1416.34   157.6 1409.01
   186.5 1392.98   287.4 1324.14   309.3 1302.94   320.8 1294.99  330.87 1285.05
   343.9 1269.47   349.4 1266.15   406.7  1262.9  458.821262.966   493.41261.894
   536.3 1258.35   544.8 1255.51   572.8 1253.53   618.6 1253.84   635.3  1257.9
   652.3 1268.47   677.7 1271.04  705.911281.216     740 1295.01   796.1 1322.96
   873.3 1367.93   924.9 1400.45  1025.7 1472.57  1060.8 1509.83  1148.8 1573.77
#Mann= 8 ,-1 , 0
       0      .1       0   97.13      .1       0  330.87     .06       0
  458.82      .1       0   493.4      .1       0   536.3    .045       0
   635.3     .06       0  705.91      .1       0
Bank Sta=536.3,635.3
XS Rating Curve= 0 ,0
Exp/Cntr(USF)=0,0
Exp/Cntr=0.3,0.1

Type RM Length L Ch R = 1 ,22442   ,319.8,398,466.7
XS GIS Cut Line= 4
2458295.23729408680799.9733760792458435.68240875680729.750818742
2458808.73974461 680532.249876232459032.57414612680356.693482887
#Sta/Elev= 30
       0 1364.67     8.4  1359.3    35.2 1356.54    53.1 1346.32   106.8 1328.35
   128.6 1316.68   164.4  1300.4   205.8 1278.14  212.381273.283   223.9 1261.79
     251 1260.61   260.1  1257.9   270.9 1253.04     337 1252.75   392.2 1253.09
     398 1254.32   404.9 1258.01  422.071264.506   468.3 1278.46   499.9 1296.28
   543.2  1325.1   595.8 1362.16   627.4 1387.31   658.5 1409.97   691.5 1435.76
   732.5 1471.74   744.4 1479.15   775.3 1503.81   825.7 1540.21   863.6 1570.44
#Mann= 5 ,-1 , 0
       0      .1       0  212.38     .06       0   260.1    .045       0
   404.9     .06       0  422.07      .1       0
Bank Sta=260.1,404.9
XS Rating Curve= 0 ,0
Exp/Cntr(USF)=0,0
Exp/Cntr=0.3,0.1

Type RM Length L Ch R = 1 ,22044   ,548.1,543.8,536.3
XS GIS Cut Line= 4
2458308.40402358680944.8074005872458453.23804809680971.140859589
2458839.46211344681072.0857857612459098.40779362681098.419244763
#Sta/Elev= 30
       0 1341.99    22.7 1335.46    30.8 1331.67      43 1331.18    71.5 1317.82
    79.6 1311.03    83.7 1309.27   116.2 1307.83   136.5 1294.85   144.8 1287.49
   202.5 1286.17   210.8 1283.94   223.2 1276.33  227.841274.982   239.7 1272.68
   252.1 1264.88   285.2 1263.87   301.7 1257.04   325.2 1254.73   338.9 1252.37
     372 1252.11   450.6 1252.52   456.3 1254.67   467.1 1259.57   520.9 1294.08
  553.231316.467   718.6 1439.04     795 1499.69     799 1503.19   806.7 1512.96
#Mann= 5 ,-1 , 0
       0      .1       0  227.84     .06       0   325.2    .045       0
   456.3     .06       0  553.23      .1       0
Bank Sta=325.2,456.3
XS Rating Curve= 0 ,0
Exp/Cntr(USF)=0,0
Exp/Cntr=0.3,0.1

Type RM Length L Ch R = 1 ,21500   ,474.8,476.4,469.2
XS GIS Cut Line= 4
2457957.29123689681436.3653019492458352.29312192681515.365678953
2458699.01699877681585.5882362912459094.01888379681651.421883794
#Sta/Elev= 30
       0 1412.61    98.6 1369.08   132.6 1351.63   189.1 1325.82   205.4 1315.06
   246.2 1310.54   254.4 1307.79   270.7 1299.05   299.3 1295.07   323.7 1286.49
   450.2 1275.46   458.4 1273.03  468.921264.515   474.7 1262.86   495.1 1262.31
   507.4 1255.81   511.4 1253.41   516.5 1252.47   613.5 1252.26     638 1253.03
   646.1 1255.37   670.6 1260.41   681.21261.178     691 1263.26   699.8 1267.19
   764.5 1304.36  786.961318.876   833.4 1352.13    1024 1494.93    1157 1599.08
#Mann= 6 ,-1 , 0
       0      .1       0  468.92     .06       0   507.4    .045       0
   646.1    .025       0   681.2     .06       0  786.96      .1       0
Bank Sta=507.4,646.1
XS Rating Curve= 0 ,0
Exp/Cntr(USF)=0,0
Exp/Cntr=0.3,0.1

Type RM Length L Ch R = 1 ,21023   ,689.6,686.8,653.5
BEGIN DESCRIPTION:
Mannings N in channel placed 0.1 because of island in the channel
END DESCRIPTION:
XS GIS Cut Line= 4
2457869.51304022 681927.923203312458207.45909741681967.423391812
2458659.51681027682055.2015884842458984.29613795682116.646326154
#Sta/Elev= 30
       0 1468.27    83.1 1414.62   162.4 1370.55   227.3 1339.14   291.2 1312.29
   307.3 1299.48  327.311297.373   347.7 1295.36   360.2 1285.47   388.4 1274.33
   396.6 1268.11   417.7 1266.75   434.7 1255.24   445.5 1250.62   468.8 1250.54
   598.5 1252.85     637 1252.85   665.5 1251.83   677.7  1254.3   698.1 1260.51
   734.8 1281.29   787.7 1322.11   803.2 1339.29  847.131372.339   885.5  1402.2
   897.7 1416.74  906.871424.295  952.761454.896  1058.41527.037  1131.3 1573.04
#Mann= 10 ,-1 , 0
       0      .1       0  327.31     .06       0   434.7    .045       0
   598.5      .1       0     637    .045       0   677.7     .06       0
  847.13     .12       0  906.87      .1       0  952.76     .12       0
  1058.4      .1       0
Bank Sta=434.7,677.7
XS Rating Curve= 0 ,0
Exp/Cntr(USF)=0,0
Exp/Cntr=0.3,0.1

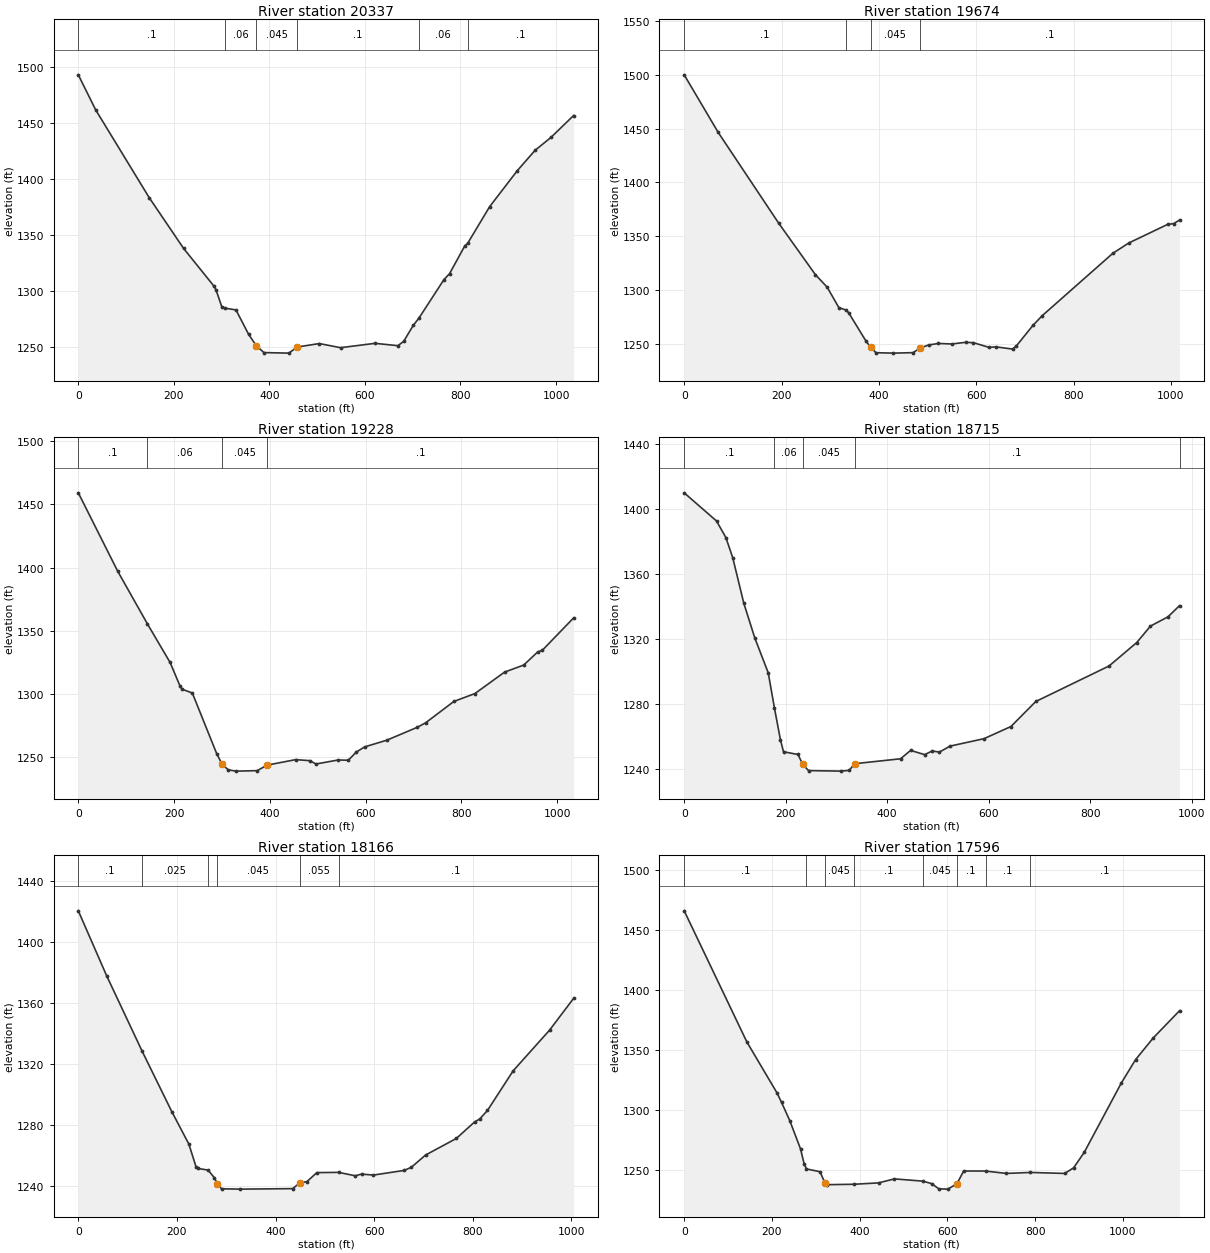
Type RM Length L Ch R = 1 ,20337   ,668.8,662.5,641.6
XS GIS Cut Line= 4
2457790.51266322682643.315506184 2458102.1252614682656.482235685
2458580.51643326682682.8156946862458826.29538394 682687.20460452
#Sta/Elev= 30
       0 1493.26    36.3 1461.93   148.4 1383.33   220.4 1337.87   284.5 1303.83
   288.5  1300.5   300.5 1285.47  306.611284.436     330 1282.83   356.5 1260.97
   372.6 1250.82   388.6 1244.63   440.7 1244.15   458.4 1249.64   504.6 1252.71
   548.9 1249.02     621 1252.91   669.1 1250.82   681.1 1254.67   701.1 1268.98
  713.281275.651   765.2 1309.86   777.2 1315.31   809.2 1340.32  814.781342.282
   861.2 1375.35     919 1407.52   956.1 1425.67   989.3  1437.2  1036.8 1456.85
#Mann= 6 ,-1 , 0
       0      .1       0  306.61     .06       0   372.6    .045       0
   458.4      .1       0  713.28     .06       0  814.78      .1       0
Bank Sta=372.6,458.4
XS Rating Curve= 0 ,0
Exp/Cntr(USF)=0,0
Exp/Cntr=0.3,0.1

Type RM Length L Ch R = 1 ,19674   ,460,445.9,392.4
XS GIS Cut Line= 4
2457772.95702388683327.985440223 2458075.7918024683332.374350057
2458536.62733493683306.0408910552458782.40628561683244.596153385
#Sta/Elev= 30
       0 1499.78    69.8 1446.44   193.8 1362.46   269.8 1314.38   293.8 1302.89
   317.8 1283.92   332.71281.674   337.9 1279.19   373.9 1252.66   382.9 1247.35
     394 1242.13     430 1241.74   470.1 1242.19   485.2 1246.47   502.1 1249.28
   522.2 1250.69   550.2 1250.23   578.3 1251.77   594.3 1251.43   626.3 1247.07
   640.6 1247.55   674.7  1245.5   682.3 1248.26   716.6 1267.44   735.3 1276.31
   880.9 1334.34   913.9 1343.94   993.4 1361.11  1005.8 1361.82  1017.8 1365.14
#Mann= 4 ,-1 , 0
       0      .1       0   332.7     .06       0   382.9    .045       0
   485.2      .1       0
Bank Sta=382.9,485.2
XS Rating Curve= 0 ,0
Exp/Cntr(USF)=0,0
Exp/Cntr=0.3,0.1

Type RM Length L Ch R = 1 ,19228   ,553.1,513.6,409.6
XS GIS Cut Line= 4
2457948.51341723683872.2102595882458150.40326957683806.376612084
2458685.85026927683622.0423990732458896.51794128683477.208374565
#Sta/Elev= 30
       0 1459.24    82.1 1397.18   144.11355.422   191.7 1324.69   212.7 1305.72
   216.9 1303.48   238.1 1300.46   288.9 1252.45   300.3 1243.93   312.9 1239.59
   328.7 1238.51   373.5 1238.89   394.4 1243.28   453.8 1247.62   483.5 1246.81
   496.2 1244.17   542.8 1247.35   563.8 1247.15   580.4 1253.59   597.7  1257.7
   644.2 1263.04   707.7 1273.24   725.2 1276.81   784.2 1293.76   828.3 1300.05
   890.1 1317.04   930.2 1322.66   959.3 1333.05     969 1334.37  1034.3 1360.04
#Mann= 4 ,-1 , 0
       0      .1       0   144.1     .06       0   300.3    .045       0
   394.4      .1       0
Bank Sta=300.3,394.4
XS Rating Curve= 0 ,0
Exp/Cntr(USF)=0,0
Exp/Cntr=0.3,0.1

Type RM Length L Ch R = 1 ,18715   ,557.8,548.3,541.5
XS GIS Cut Line= 4
2458339.12639241684425.2128986192458440.07131859 684315.49015278
2458804.35083477683898.5437185892458988.68504779683696.653866244
#Sta/Elev= 30
       0 1409.87    63.7 1392.53    82.1 1382.35    95.6    1370   117.4 1341.98
     139 1320.66   165.6 1299.08  177.771277.516   189.6 1257.94   195.7 1250.49
   224.3  1248.8   233.6 1242.71     245 1238.88   309.2 1238.56   325.2 1239.04
   335.8 1243.13   426.4 1246.16   446.2 1251.33   473.9 1248.71   488.8 1250.98
   502.9 1250.27     524 1253.96   590.9 1258.54   643.9 1266.02   692.9 1281.43
   837.3 1303.29   891.9 1317.73   918.9 1327.84   953.4 1333.55   976.1 1340.41
#Mann= 5 ,-1 , 0
       0      .1       0  177.77     .06       0   233.6    .045       0
   335.8      .1       0   976.1      .1       0
Bank Sta=233.6,335.8
XS Rating Curve= 0 ,0
Exp/Cntr(USF)=0,0
Exp/Cntr=0.3,0.1

Type RM Length L Ch R = 1 ,18166   ,601.5,570.8,434.2
XS GIS Cut Line= 4
2458764.85064627684833.3815131432458865.79557244684692.936398468
2459208.13053946684179.433947939 2459291.5198263683981.933005427
#Sta/Elev= 30
       0  1420.2    57.6 1377.65  129.551328.353   189.8 1288.79   224.2  1267.7
   238.6 1253.02   242.7 1251.77  263.321250.687   276.1 1245.62   281.8 1241.73
   290.5 1238.47     328 1238.25   434.7 1238.57   448.7 1242.19   463.9 1243.23
   483.8 1249.05     528  1249.2   561.6 1246.98   574.4 1248.07   598.5 1247.44
     661  1250.5   675.4 1252.54   704.2 1260.52   766.7 1271.39   803.7 1282.18
   813.9 1284.04   829.8 1289.69   881.9 1315.61   955.7 1342.18  1004.5 1362.98
#Mann= 6 ,-1 , 0
       0      .1       0  129.55    .025       0  263.32     .06       0
   281.8    .045       0   448.7    .055       0     528      .1       0
Bank Sta=281.8,448.7
XS Rating Curve= 0 ,0
Exp/Cntr(USF)=0,0
Exp/Cntr=0.3,0.1

Type RM Length L Ch R = 1 ,17596   ,657.3,626.6,454.7
BEGIN DESCRIPTION:
Mannings N in channel placed 0.1 because of island in the channel
END DESCRIPTION:
XS GIS Cut Line= 4
2459370.52020331685206.4388489972459418.79821148684982.604447485
2459510.96531798684350.6014314482459475.85403931684091.655751267
#Sta/Elev= 30
       0 1465.87   142.8 1356.55   211.9 1313.83     222 1306.06   240.8  1290.8
   265.1 1267.43   273.2 1255.17  278.741250.642   309.5 1248.35   320.4 1239.31
   325.7 1237.53   386.3 1237.87   442.9 1239.02   479.3 1242.36     544 1240.48
   563.8 1238.44   580.4 1234.11   600.6 1233.82   621.5 1238.18     637 1248.94
  687.011248.891     734 1246.92  789.07 1247.72   867.4 1246.91   887.6 1251.57
   911.8 1264.45   996.5  1322.4  1028.8 1341.75  1069.2 1359.91    1129 1382.56
#Mann= 8 ,-1 , 0
       0      .1       0  278.74     .06       0   320.4    .045       0
   386.3      .1       0     544    .045       0   621.5      .1       0
  687.01      .1       0  789.07      .1       0
Bank Sta=320.4,621.5
XS Rating Curve= 0 ,0
Exp/Cntr(USF)=0,0
Exp/Cntr=0.3,0.1

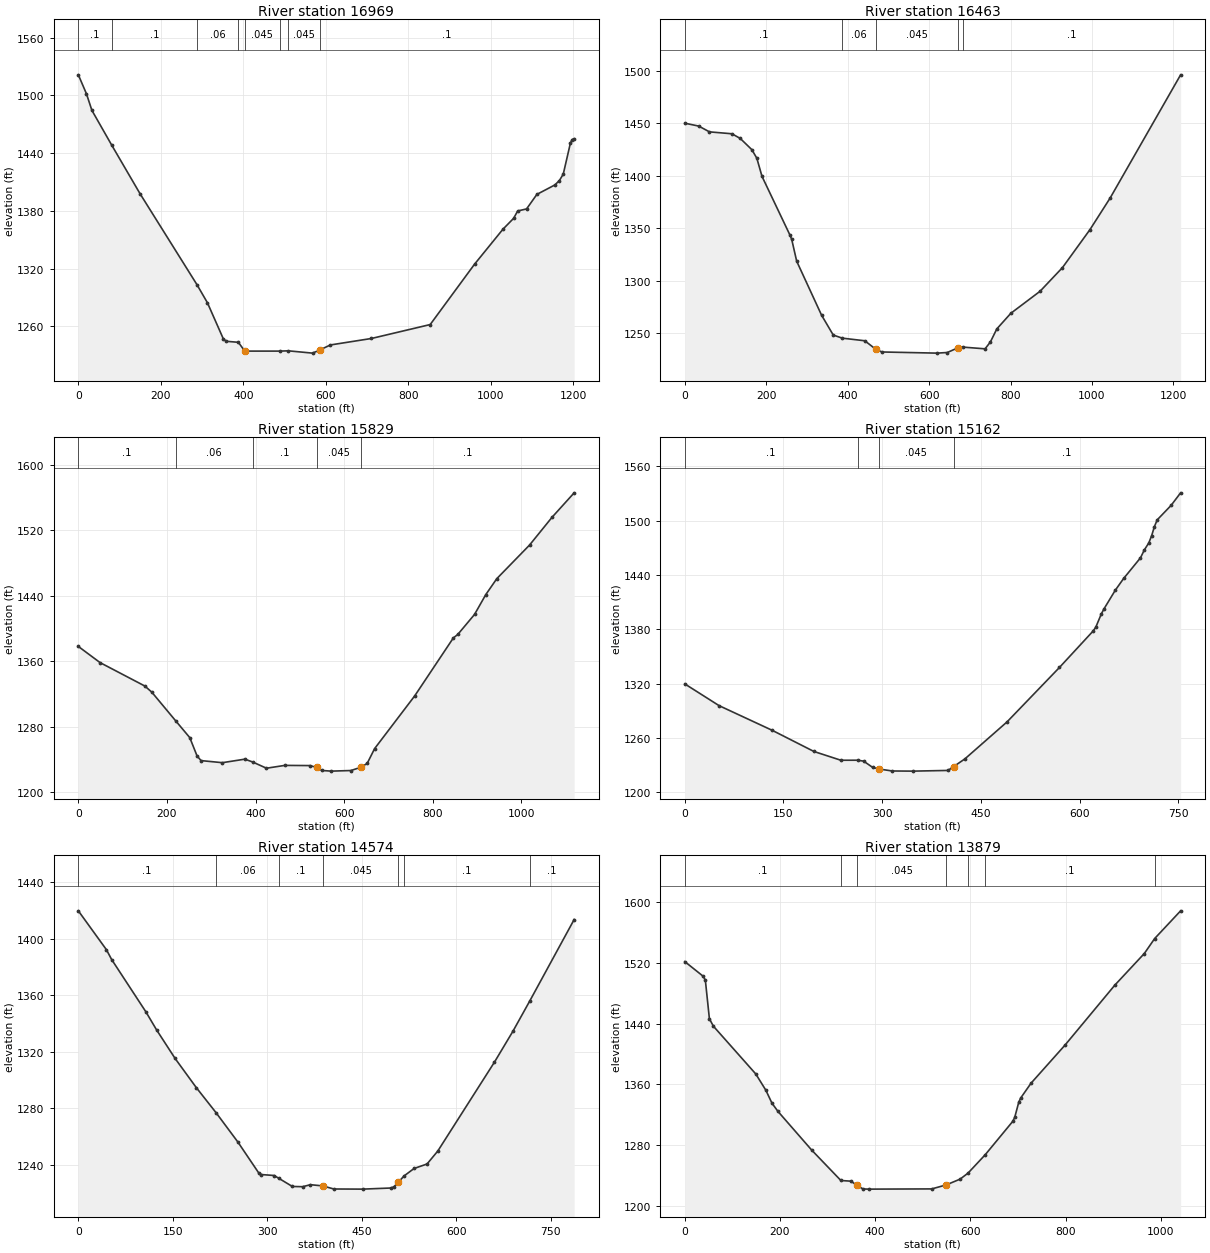
Type RM Length L Ch R = 1 ,16969   ,471.5,506.4,488.9
BEGIN DESCRIPTION:
Mannings N in channel placed 0.1 because of island in the channel
END DESCRIPTION:
XS GIS Cut Line= 4
2460200.02416185685087.9382834912460063.96795701684833.381513143
2459835.74464567684275.9899642782459721.63298999683986.321915261
#Sta/Elev= 30
       0 1521.35    19.7 1501.65    32.9 1484.44   81.021448.274   149.5 1397.98
  287.711303.396     313 1284.66   351.8 1246.96   358.9 1244.62  388.021243.569
   403.7 1234.44   488.6 1234.44   509.2 1234.72     568 1232.33   585.2 1235.55
   611.2 1240.82   710.6 1247.53   853.2    1262   960.9 1324.77  1029.7 1361.06
  1055.5 1372.31  1065.3 1379.95  1086.9 1382.08  1111.9 1397.18  1155.6 1407.01
  1166.5 1411.55  1175.9 1418.26  1193.1 1450.27  1197.4 1454.12  1202.3 1454.91
#Mann= 8 ,-1 , 0
       0      .1       0   81.02      .1       0  287.71     .06       0
  388.02      .1       0   403.7    .045       0   488.6      .1       0
   509.2    .045       0   585.2      .1       0
Bank Sta=403.7,585.2
XS Rating Curve= 0 ,0
Exp/Cntr(USF)=0,0
Exp/Cntr=0.3,0.1

Type RM Length L Ch R = 1 ,16463   ,355.8,633.4,643.1
XS GIS Cut Line= 4
2460524.80348954684956.2709884832460437.02529287684521.768914958
2460279.02453886684052.1555627652460186.85743235 683788.82097275
#Sta/Elev= 30
       0 1449.89    34.1 1447.16    60.6 1441.65   115.7 1439.83   136.1 1435.42
   164.6 1424.75   176.9  1416.6   189.6 1399.32   258.5 1343.28   262.6 1339.35
   274.8 1318.64     336  1267.2   364.6 1248.39  386.771245.427   442.1 1242.93
   469.5 1234.73   484.3 1232.28   619.3 1231.18   644.7 1231.77     670 1236.08
  682.921236.911   737.5 1235.27   750.5 1241.75   766.3 1254.19   800.8 1269.08
   872.6 1290.03   927.6 1312.54   995.2  1348.7  1044.7 1378.73  1217.8  1495.9
#Mann= 5 ,-1 , 0
       0      .1       0  386.77     .06       0   469.5    .045       0
     670    .025       0  682.92      .1       0
Bank Sta=469.5,670
XS Rating Curve= 0 ,0
Exp/Cntr(USF)=0,0
Exp/Cntr=0.3,0.1

Type RM Length L Ch R = 1 ,15829   ,515,667.2,720.1
XS GIS Cut Line= 4
2460652.08187471 684903.604070482460735.47116155684719.269857469
2460994.41684173684179.4339479392461090.97285807683876.599169421
#Sta/Elev= 30
       0 1378.17    49.1  1358.4   150.1 1329.79   165.8 1322.28  219.431287.415
   251.5 1266.73     268 1244.24     277 1238.65     325  1236.1   375.8 1240.41
   393.31236.951   424.6 1229.33   465.9 1232.79   522.9 1232.56   537.9 1230.22
   549.9 1226.56   570.8 1225.78   615.3 1226.52   637.5 1230.53   651.8 1235.15
   668.6  1253.3   758.9  1317.6   846.3 1388.59   856.2 1392.78   894.1 1417.29
   919.5 1441.54   944.4 1461.05  1018.2 1502.05  1069.1  1536.1  1118.9 1565.91
#Mann= 5 ,-1 , 0
       0      .1       0  219.43     .06       0   393.3      .1       0
   537.9    .045       0   637.5      .1       0
Bank Sta=537.9,637.5
XS Rating Curve= 0 ,0
Exp/Cntr(USF)=0,0
Exp/Cntr=0.3,0.1

Type RM Length L Ch R = 1 ,15162   ,580.6,587.7,596.2
XS GIS Cut Line= 4
2460845.19390739685087.9382834912460968.08338273685044.049185155
2461385.02981692684899.2151606462461556.19730043684837.770422976
#Sta/Elev= 30
       0 1319.72    52.1 1295.73   133.3 1268.34   196.3 1245.14   237.2 1235.48
  262.551235.496   271.8  1234.5   285.7  1227.5   295.1 1225.81   315.4 1223.62
     347 1223.46   400.1 1224.22   408.5 1228.39   425.8 1236.98   489.8 1277.77
   569.5 1337.85   620.6 1378.01   624.7 1382.21   633.2 1397.02   637.4 1402.74
   654.4 1423.11   667.2 1436.19   692.7 1458.86   698.6 1467.64   705.4 1475.39
   709.7 1483.37   713.9  1493.4   718.2 1500.83   739.2  1516.7   753.7 1530.58
#Mann= 4 ,-1 , 0
       0      .1       0  262.55     .06       0   295.1    .045       0
   408.5      .1       0
Bank Sta=295.1,408.5
XS Rating Curve= 0 ,0
Exp/Cntr(USF)=0,0
Exp/Cntr=0.3,0.1

Type RM Length L Ch R = 1 ,14574   ,705.4,695,679.8
XS GIS Cut Line= 4
2460880.30518606 685662.885471692461073.41721874 685601.44073402
 2461512.3082021685496.1068980142461639.58658727685456.606709512
#Sta/Elev= 30
       0 1419.88    44.5 1392.42    52.9  1385.4   107.5 1348.18   124.3 1335.51
   153.7  1315.3   187.3 1294.69  218.681276.918   253.4  1256.1   286.3 1234.34
   290.4 1233.11     311 1232.43  318.281230.453   339.8 1224.67   356.2  1224.5
   368.6 1225.92   388.3 1225.05   405.6 1222.88   451.4 1222.78   496.1 1223.57
   501.1 1224.42   507.8 1227.57  517.461232.202   533.1  1237.4   553.7 1240.58
   570.8 1249.78   660.7  1312.7   690.1 1334.61  717.091356.271   787.3 1413.73
#Mann= 7 ,-1 , 0
       0      .1       0  218.68     .06       0  318.28      .1       0
   388.3    .045       0   507.8      .1       0  517.46      .1       0
  717.09      .1       0
Bank Sta=388.3,507.8
XS Rating Curve= 0 ,0
Exp/Cntr(USF)=0,0
Exp/Cntr=0.3,0.1

Type RM Length L Ch R = 1 ,13879   ,634,625.6,595.5
XS GIS Cut Line= 4
 2460990.0279319686382.6666843982461213.86233341686303.666307393
2461665.92004627686141.2766435512461959.97700512 686005.22043871
#Sta/Elev= 30
       0 1521.77    38.9 1502.33    43.2 1497.17    51.7 1446.49    60.1 1436.71
   149.2 1373.77   170.4 1352.28   183.2 1335.27   195.9  1324.4   266.8 1273.45
  327.941233.542   348.8 1232.66   361.6  1227.3   374.3  1222.4   387.1 1222.18
   518.8 1222.47   549.3 1227.76   578.3 1235.31  595.121243.301  631.011267.355
   688.8 1311.24   693.1 1316.52   701.6 1336.59   705.8 1342.25   727.4 1361.65
   798.5 1411.59   903.7 1490.94   965.4 1532.42  987.241552.179  1041.7 1588.63
#Mann= 7 ,-1 , 0
       0      .1       0  327.94     .06       0   361.6    .045       0
   549.3     .12       0  595.12      .1       0  631.01      .1       0
  987.24      .1       0
Bank Sta=361.6,549.3
XS Rating Curve= 0 ,0
Exp/Cntr(USF)=0,0
Exp/Cntr=0.3,0.1