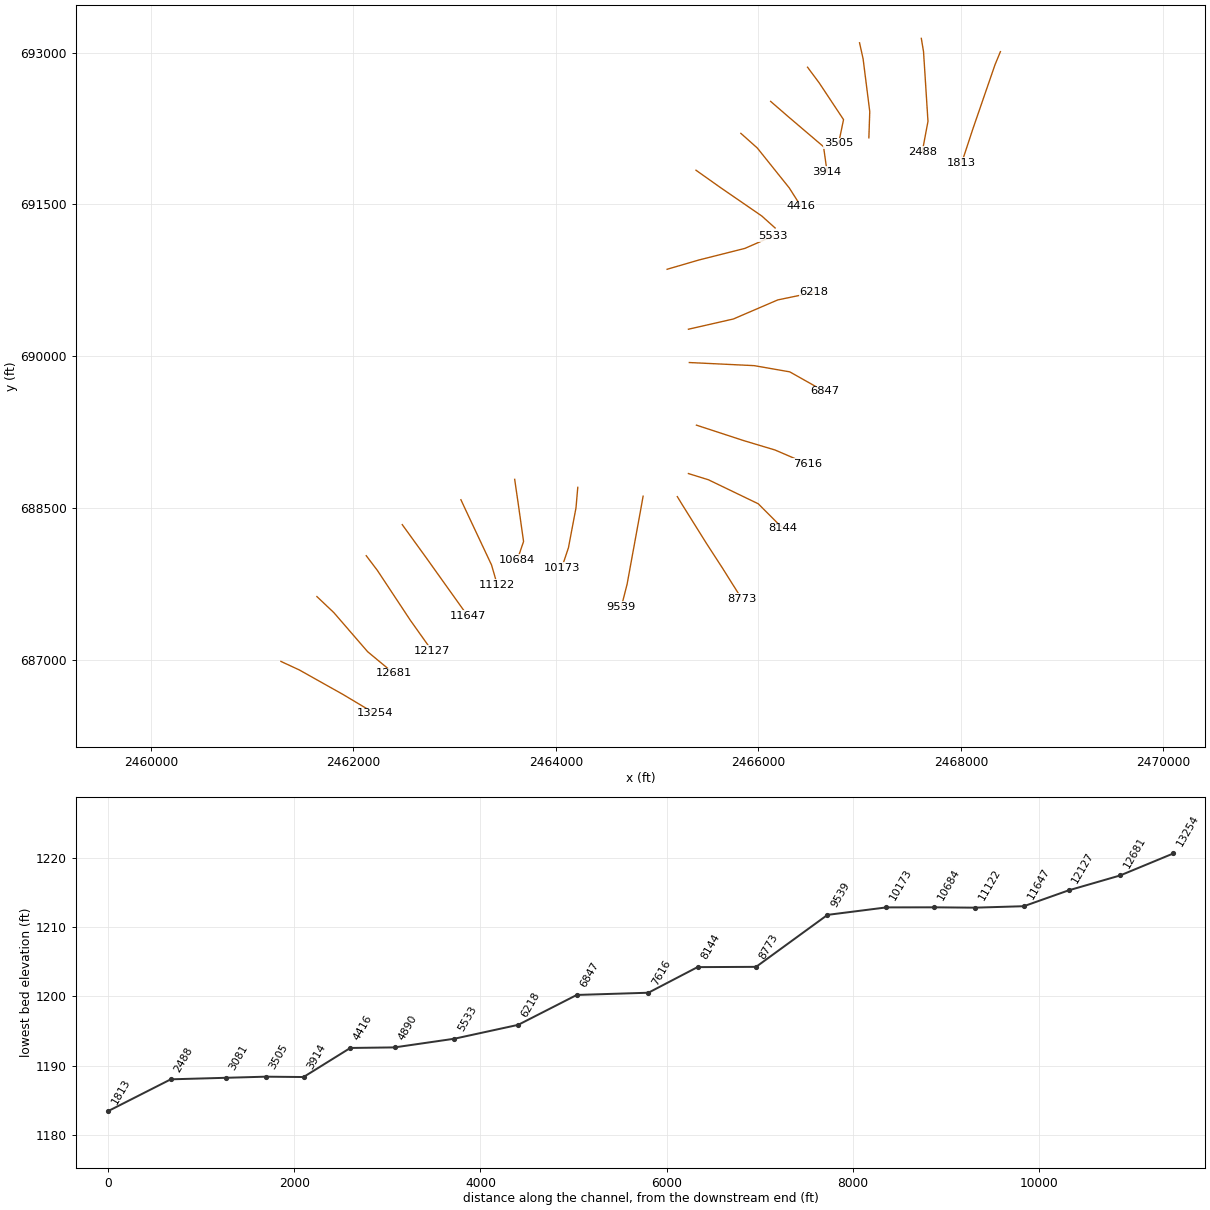
HEC-RAS study SBPOTOMC.prj: SBPOTOMC

--- SBPOTOMC.g01 (geometry) --- (continued)

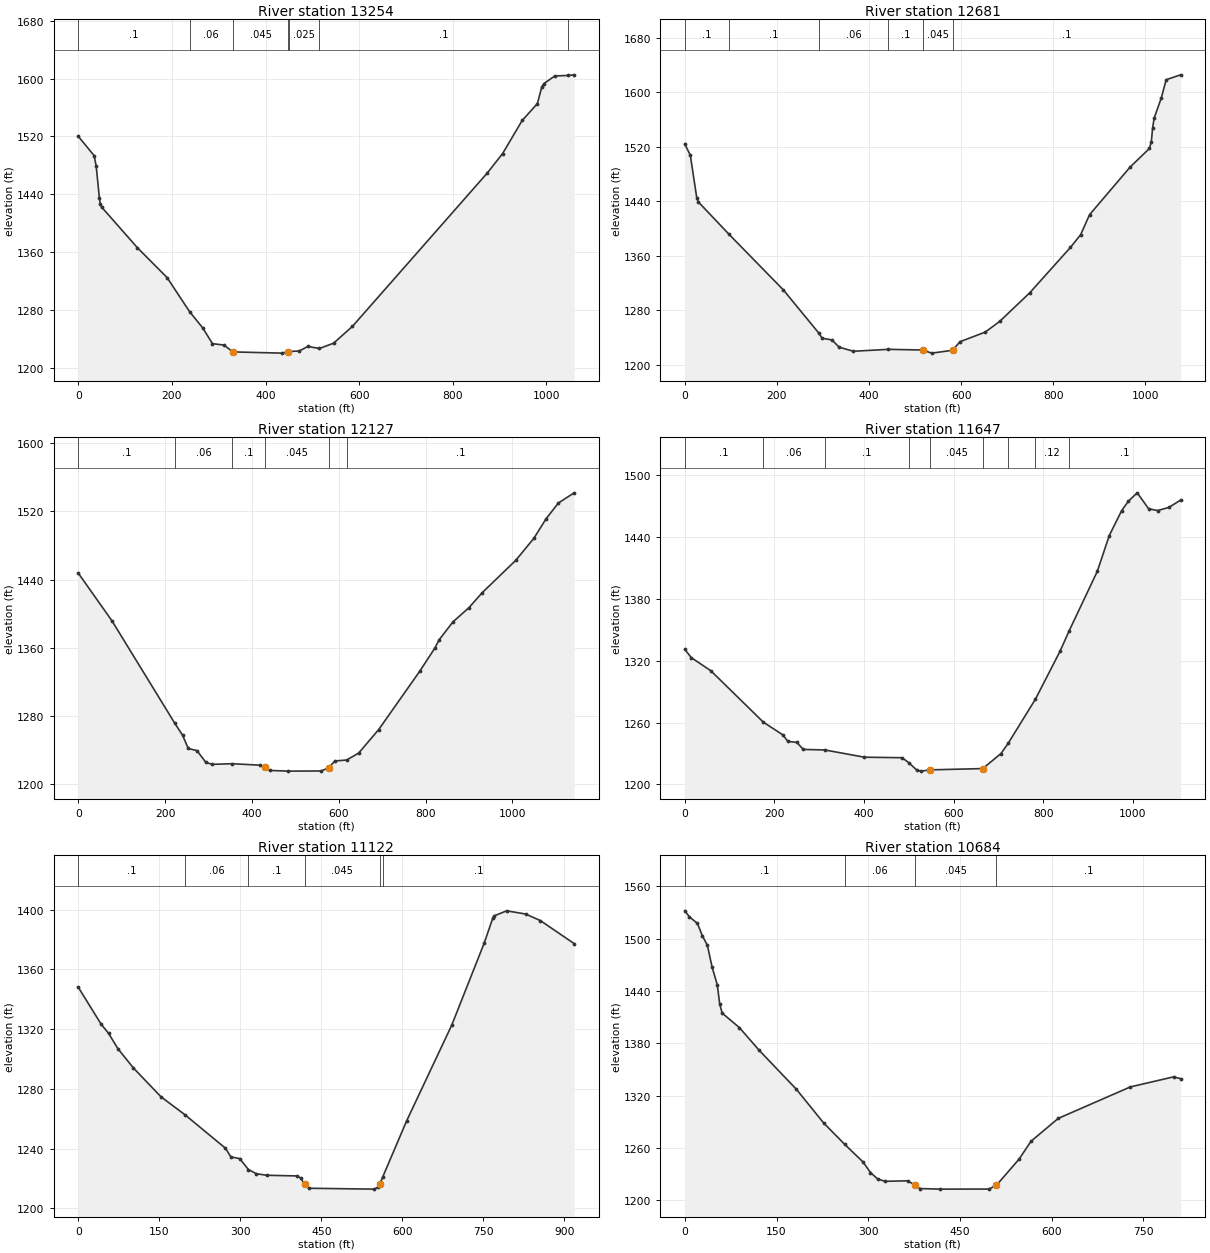
Type RM Length L Ch R = 1 ,13254   ,616.4,572.7,541.2
XS GIS Cut Line= 4
2461284.08489075686983.9473315992461464.03019393686900.558044761
2461894.14335762686659.1680039142462210.14486564686470.444881069
#Sta/Elev= 30
       0 1520.14    33.8 1493.49    38.2 1479.09      45 1434.75      47 1426.42
    50.1 1422.19   126.4 1366.14   189.6 1325.07  237.651277.993   265.7 1255.56
   286.7 1233.67   311.5 1231.71   329.9 1222.29   435.4 1220.59   449.1 1222.79
  449.161222.796   472.1 1223.55   490.4 1229.79  515.141227.022   545.5 1234.32
   585.9 1257.66     874 1469.54   906.6 1496.28   948.5 1542.08     981 1565.43
   990.4 1588.41   995.1 1593.15  1018.4  1603.7 1047.321604.297  1059.6 1605.19
#Mann= 7 ,-1 , 0
       0      .1       0  237.65     .06       0   329.9    .045       0
   449.1      .1       0  449.16    .025       0  515.14      .1       0
 1047.32      .1       0
Bank Sta=329.9,449.1
XS Rating Curve= 0 ,0
Exp/Cntr(USF)=0,0
Exp/Cntr=0.3,0.1

Type RM Length L Ch R = 1 ,12681   ,577,554,545.1
XS GIS Cut Line= 4
2461639.58658727687624.7281673022461806.36516095687466.727413293
 2462139.9223083687080.5033479382462398.86798848686865.446766092
#Sta/Elev= 30
       0 1523.94      12 1507.69    25.9  1445.5      29 1439.44   95.371392.124
   213.7 1310.34  291.56 1246.35   298.2 1239.16   319.4 1236.82   335.2 1226.12
     366 1220.16  442.191222.961   516.3    1222   536.2 1217.41   581.6 1221.55
   597.5 1234.11   652.5 1248.26   684.1 1264.15   748.9 1305.75   837.3 1372.35
   859.7 1391.19   878.9 1420.37   967.3 1490.48  1008.9 1517.51  1013.1 1527.48
  1015.9 1547.66  1019.3 1562.21  1034.9 1591.93  1045.3 1618.35  1076.7 1625.54
#Mann= 6 ,-1 , 0
       0      .1       0   95.37      .1       0  291.56     .06       0
  442.19      .1       0   516.3    .045       0   581.6      .1       0
Bank Sta=516.3,581.6
XS Rating Curve= 0 ,0
Exp/Cntr(USF)=0,0
Exp/Cntr=0.3,0.1

Type RM Length L Ch R = 1 ,12127   ,471.9,479.5,483.4
XS GIS Cut Line= 4
 2462126.7555788688028.5078719922462236.47832464687883.673847484
2462561.25765232687392.1159461222462776.31423417687089.281167605
#Sta/Elev= 30
       0 1447.47    77.3 1391.74  222.511271.184   240.2 1257.37   253.2 1241.84
   273.4  1239.3   293.6 1225.65     308  1223.2  354.561223.939   417.6 1222.28
   429.3 1219.96   441.5 1216.06   483.3 1215.26   559.2 1215.44   576.5 1219.04
     591 1227.16  618.241228.314   645.8  1236.4     692 1264.05   787.2 1332.93
   821.6 1359.79   831.2 1369.34   863.2 1390.45   899.9 1407.03   930.6 1424.69
  1007.9 1462.63  1049.8 1488.64  1077.4 1511.17    1106 1529.83  1142.3 1541.77
#Mann= 6 ,-1 , 0
       0      .1       0  222.51     .06       0  354.56      .1       0
   429.3    .045       0   576.5     .12       0  618.24      .1       0
Bank Sta=429.3,576.5
XS Rating Curve= 0 ,0
Exp/Cntr(USF)=0,0
Exp/Cntr=0.3,0.1

Type RM Length L Ch R = 1 ,11647   ,555,525.4,510.9
XS GIS Cut Line= 4
2462482.25727532688335.7315603432462723.64731617 688002.17441299
2462929.92607834687712.5063639742463127.42702086687436.005044458
#Sta/Elev= 30
       0 1331.18    14.5 1323.17    58.2 1310.37  175.381260.534   218.7 1248.24
   230.1 1241.91   250.2 1240.87   264.5 1234.04  312.651233.542     401 1226.49
   485.2 1226.01  500.371221.057   518.9 1213.64   527.4 1212.98   548.2 1214.21
   665.3 1215.45     706 1230.06  722.151240.008  782.911282.846   837.6 1329.13
  858.531349.469   921.1 1406.95   947.7 1441.58   975.2 1465.68   990.5 1475.02
  1010.2 1483.13  1035.8  1467.6  1055.8 1465.94  1080.5  1468.9  1107.1 1476.09
#Mann= 9 ,-1 , 0
       0      .1       0  175.38     .06       0  312.65      .1       0
  500.37    .025       0   548.2    .045       0   665.3     .12       0
  722.15      .1       0  782.91     .12       0  858.53      .1       0
Bank Sta=548.2,665.3
XS Rating Curve= 0 ,0
Exp/Cntr(USF)=0,0
Exp/Cntr=0.3,0.1

Type RM Length L Ch R = 1 ,11122   ,472,438.3,421.3
XS GIS Cut Line= 4
2463061.59337335688581.5105110232463158.14938969688375.231748845
2463364.42815187687936.3407654872463421.48397971687738.839822975
#Sta/Elev= 30
       0    1348    42.6 1323.12    55.9 1317.26    73.6 1306.73   102.1 1293.95
   153.3 1274.58  197.341262.664   272.3 1240.24   282.6 1234.39   298.9 1233.21
  314.971225.901   329.8 1223.08   348.7 1222.07   404.9 1221.61   411.9 1220.17
     419 1215.95   426.9 1213.35   547.2 1212.77   555.2 1213.93   558.3  1216.2
  563.641220.839   608.2 1258.65   691.5 1322.62   751.7 1377.66   767.4 1394.17
   770.7 1396.01   793.3  1399.3   828.5 1397.16   855.8 1392.75   918.3 1377.33
#Mann= 6 ,-1 , 0
       0      .1       0  197.34     .06       0  314.97      .1       0
     419    .045       0   558.3     .12       0  563.64      .1       0
Bank Sta=419,558.3
XS Rating Curve= 0 ,0
Exp/Cntr(USF)=0,0
Exp/Cntr=0.3,0.1

Type RM Length L Ch R = 1 ,10684   ,545.8,511.1,486.6
XS GIS Cut Line= 4
2463592.65146322688783.4003633682463627.76274188688542.010322521
2463680.42965989688168.9529866662463618.98492222 687989.00768349
#Sta/Elev= 30
       0 1531.86     7.6 1524.95    20.7 1517.41    28.8 1503.01    36.9 1492.49
    44.6 1467.46    53.1 1447.06    57.1 1425.03    61.1  1414.6    89.4 1397.92
   121.8 1371.83   182.4 1327.33   226.9  1288.8  261.231264.328   291.5 1243.95
   303.6 1231.85   315.8 1224.22   327.9  1221.8   364.2 1222.34   376.3 1217.63
   384.4 1213.48   416.7 1212.82   497.5 1212.91   509.7 1217.32   546.7 1247.27
   566.2 1267.74   610.7 1293.91   728.5 1329.97   799.2 1341.51   810.8 1339.47
#Mann= 4 ,-1 , 0
       0      .1       0  261.23     .06       0   376.3    .045       0
   509.7      .1       0
Bank Sta=376.3,509.7
XS Rating Curve= 0 ,0
Exp/Cntr(USF)=0,0
Exp/Cntr=0.3,0.1

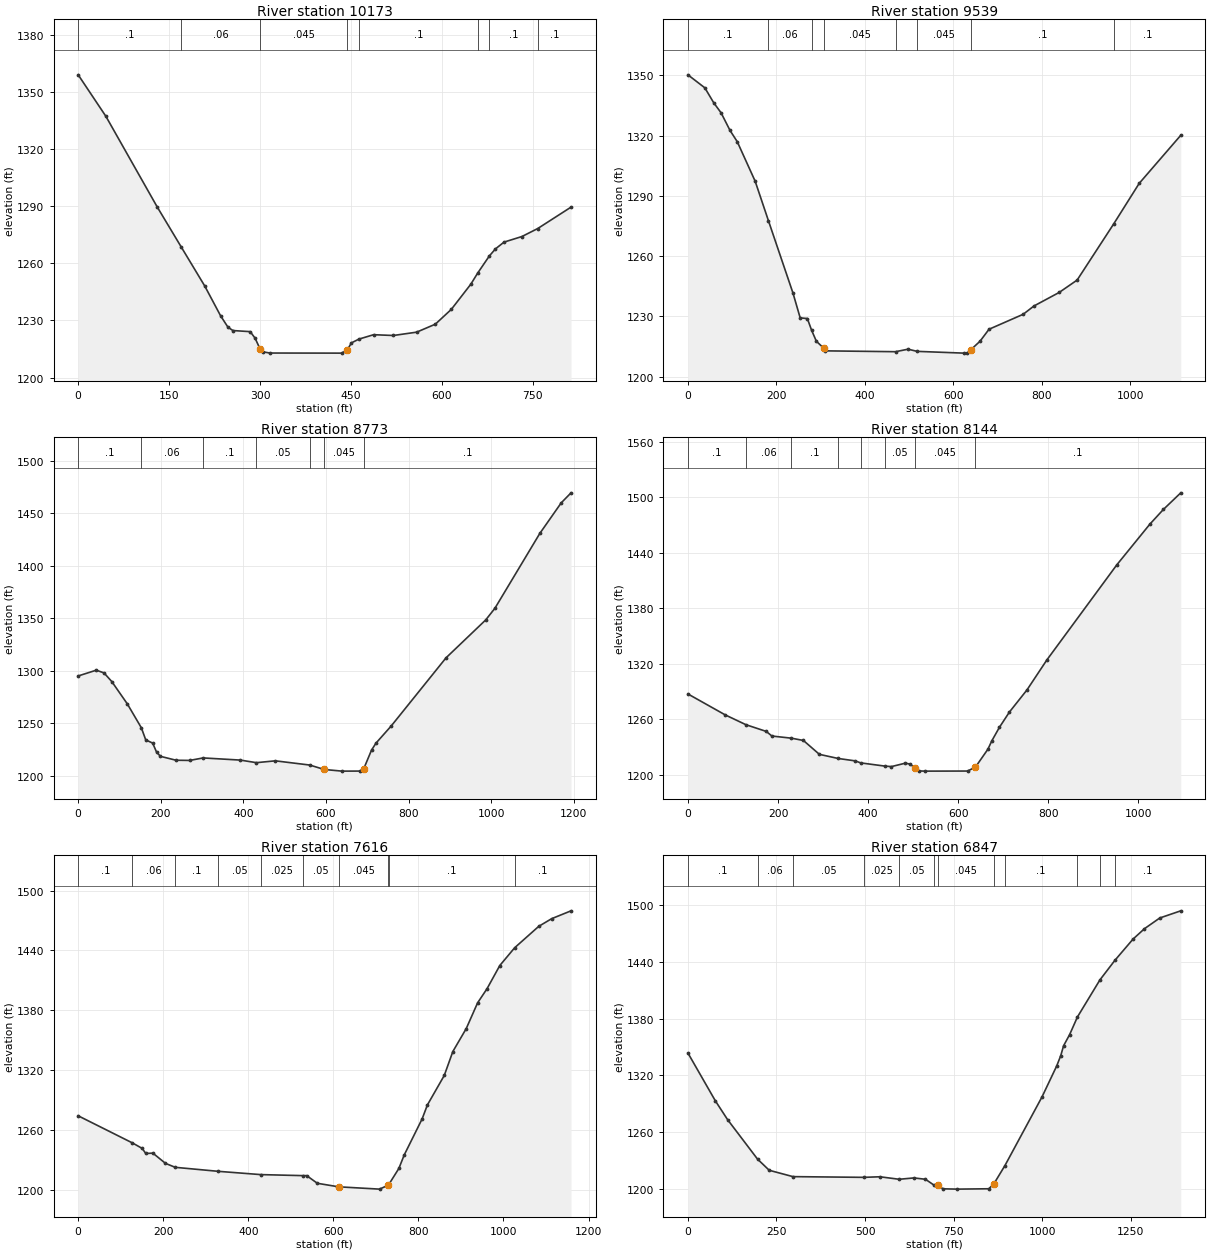
Type RM Length L Ch R = 1 ,10173   ,632.9,633.6,653.9
XS GIS Cut Line= 4
2464215.87665958688704.3999863642464198.32102025688502.510134019
2464123.70955308688107.5082489962464057.87590558687910.007306485
#Sta/Elev= 30
       0 1359.05    45.7 1337.24     130  1289.8  170.131268.485   208.8 1248.04
   234.8 1232.46     247 1226.44   255.2 1224.67   283.7  1224.1   291.8 1220.64
     300 1214.95     304 1213.51   316.2 1212.86   434.3 1212.81   443.6 1214.39
   450.6 1218.19  462.97 1220.18   487.2 1222.49   519.8 1222.08   558.1 1223.82
     589 1228.02   615.4 1235.82   647.5 1249.02  658.88 1254.89  678.041263.853
   688.1 1267.57   702.3 1271.15   731.8 1274.08  757.81 1278.27   812.8 1289.53
#Mann= 8 ,-1 , 0
       0      .1       0  170.13     .06       0     300    .045       0
   443.6    .025       0  462.97      .1       0  658.88      .1       0
  678.04      .1       0  757.81      .1       0
Bank Sta=300,443.6
XS Rating Curve= 0 ,0
Exp/Cntr(USF)=0,0
Exp/Cntr=0.3,0.1

Type RM Length L Ch R = 1 ,9539    ,564.7,766.5,889.6
BEGIN DESCRIPTION:
Mannings N in channel placed 0.1 because of island in the channel
END DESCRIPTION:
XS GIS Cut Line= 4
2464861.04640512688616.6217896922464830.32403629688445.454306182
2464703.04565111687747.6176426422464645.98982328 687523.78324113
#Sta/Elev= 30
       0 1350.24    38.3 1343.76    58.3 1336.34    74.9 1331.36    95.2 1322.56
   111.5 1316.98   152.1 1297.25  182.08  1277.6   237.5 1241.63   253.8 1229.27
     270 1228.95  279.661223.095   290.4 1217.64   306.9 1214.22   310.7 1212.86
   469.3 1212.44   497.7 1213.69   518.1 1212.61   623.8 1211.73   631.9 1211.75
   639.7 1213.44   660.4 1217.66   680.7 1223.61   757.9 1231.06   782.3 1235.19
   839.3 1241.93   879.9 1248.09  963.011276.195  1020.2 1296.21  1114.2 1320.15
#Mann= 8 ,-1 , 0
       0      .1       0  182.08     .06       0  279.66      .1       0
   306.9    .045       0   469.3      .1       0   518.1    .045       0
   639.7      .1       0  963.01      .1       0
Bank Sta=306.9,639.7
XS Rating Curve= 0 ,0
Exp/Cntr(USF)=0,0
Exp/Cntr=0.3,0.1

Type RM Length L Ch R = 1 ,8773    ,489.4,628.9,664.4
XS GIS Cut Line= 5
2465198.99246231688612.2328798582465247.27047048688533.232502854
2465488.66051132688147.008437499 2465642.2723555687910.007306485
2465835.38438818687602.783618134
#Sta/Elev= 30
       0 1295.02    43.8 1300.54    62.5 1297.94    81.3 1289.71   118.9 1268.43
   152.91245.621   163.6 1234.02   180.3    1231   189.7 1222.44   199.1 1218.36
   236.9 1214.63   269.9 1214.45  302.611216.828   392.5 1214.77  431.531212.312
   477.4 1214.06  560.631210.043   595.9 1205.81   638.7 1204.24   681.6 1204.29
   691.6  1206.7   710.2 1224.25     721 1230.93   757.9 1247.31   890.8 1312.39
   986.8 1348.51    1009  1359.6  1117.6 1430.93  1169.6 1460.19  1193.3 1469.72
#Mann= 7 ,-1 , 0
       0      .1       0   152.9     .06       0  302.61      .1       0
  431.53     .05       0  560.63      .1       0   595.9    .045       0
   691.6      .1       0
Bank Sta=595.9,691.6
XS Rating Curve= 0 ,0
Exp/Cntr(USF)=0,0
Exp/Cntr=0.3,0.1

Type RM Length L Ch R = 1 ,8144    ,491.6,527.6,544.3
XS GIS Cut Line= 4
2465308.71520815688840.4561912052465506.21615066688779.011453535
2465997.77405202688542.0103225212466239.16409287688300.620281674
#Sta/Elev= 30
       0 1287.54    82.7 1264.95  128.841254.318   173.9 1247.08   186.4  1242.1
  229.881239.765   256.3 1237.32   291.8 1222.32  333.481217.862   371.7 1215.24
  383.371213.102  437.081209.632   451.7  1209.1   482.7 1212.81     492 1211.87
   504.9 1207.64   513.8 1204.37   527.2  1204.2   620.8 1204.29   638.2 1208.57
   665.7 1227.76   674.7 1237.07   691.5 1251.61   713.6 1268.01   752.6 1291.92
   796.6  1324.2   951.9 1426.93  1025.4 1470.94  1055.3 1486.77  1093.9 1504.72
#Mann= 8 ,-1 , 0
       0      .1       0  128.84     .06       0  229.88      .1       0
  333.48     .05       0  383.37      .1       0  437.08     .05       0
   504.9    .045       0   638.2      .1       0
Bank Sta=504.9,638.2
XS Rating Curve= 0 ,0
Exp/Cntr(USF)=0,0
Exp/Cntr=0.3,0.1

Type RM Length L Ch R = 1 ,7616    ,715.3,768.7,778.7
XS GIS Cut Line= 4
2465387.71558515689318.8473630662465857.32893735 689165.23551889
 2466164.5526257689073.0684123852466480.55413371688937.012207544
#Sta/Elev= 30
       0 1274.06  127.68 1246.82   150.5 1241.35   158.9 1236.27   175.7  1236.6
   205.3 1226.34   228.21222.379  328.731218.386  429.261215.077  529.661214.035
   537.3 1214.05   562.4 1206.36   612.5 1202.82   708.6 1200.51   729.4 1204.52
     7301204.877   754.1 1221.29   766.7 1234.84   808.8    1271   821.2 1284.99
   860.8 1314.52     881 1338.54   912.5 1361.56   939.2 1387.36   961.3 1401.46
   991.4 1424.78 1026.231442.557    1083 1464.09  1113.4 1471.78  1158.9 1479.64
#Mann= 10 ,-1 , 0
       0      .1       0  127.68     .06       0   228.2      .1       0
  328.73     .05       0  429.26    .025       0  529.66     .05       0
   612.5    .045       0   729.4      .1       0     730      .1       0
 1026.23      .1       0
Bank Sta=612.5,729.4
XS Rating Curve= 0 ,0
Exp/Cntr(USF)=0,0
Exp/Cntr=0.3,0.1

Type RM Length L Ch R = 1 ,6847    ,450.2,629.3,661.3
XS GIS Cut Line= 4
2465317.49302781689937.6836496012465958.27386352689906.961280766
 2466309.3866502689845.5165430952466651.72161722689652.404510418
#Sta/Elev= 30
       0 1343.64    77.3 1293.32   111.9 1273.46  196.421231.852   229.5 1220.05
  296.371213.361  496.271212.606   541.9 1213.21  596.221210.575     638 1211.99
   670.4 1210.58  695.831204.058     707 1204.64   719.2 1200.53   759.5 1200.19
   849.1 1200.57   863.5 1205.77  894.471224.845   999.5 1297.47  1040.9 1330.06
  1052.2 1340.81  1060.3 1351.32  1077.2 1362.94 1099.361381.628 1162.821420.696
 1205.191441.366  1256.3  1463.7  1288.6 1474.68  1331.8 1485.96    1391 1493.49
#Mann= 12 ,-1 , 0
       0      .1       0  196.42     .06       0  296.37     .05       0
  496.27    .025       0  596.22     .05       0  695.83      .1       0
     707    .045       0   863.5      .1       0  894.47      .1       0
 1099.36      .1       0 1162.82      .1       0 1205.19      .1       0
Bank Sta=707,863.5
XS Rating Curve= 0 ,0
Exp/Cntr(USF)=0,0
Exp/Cntr=0.3,0.1

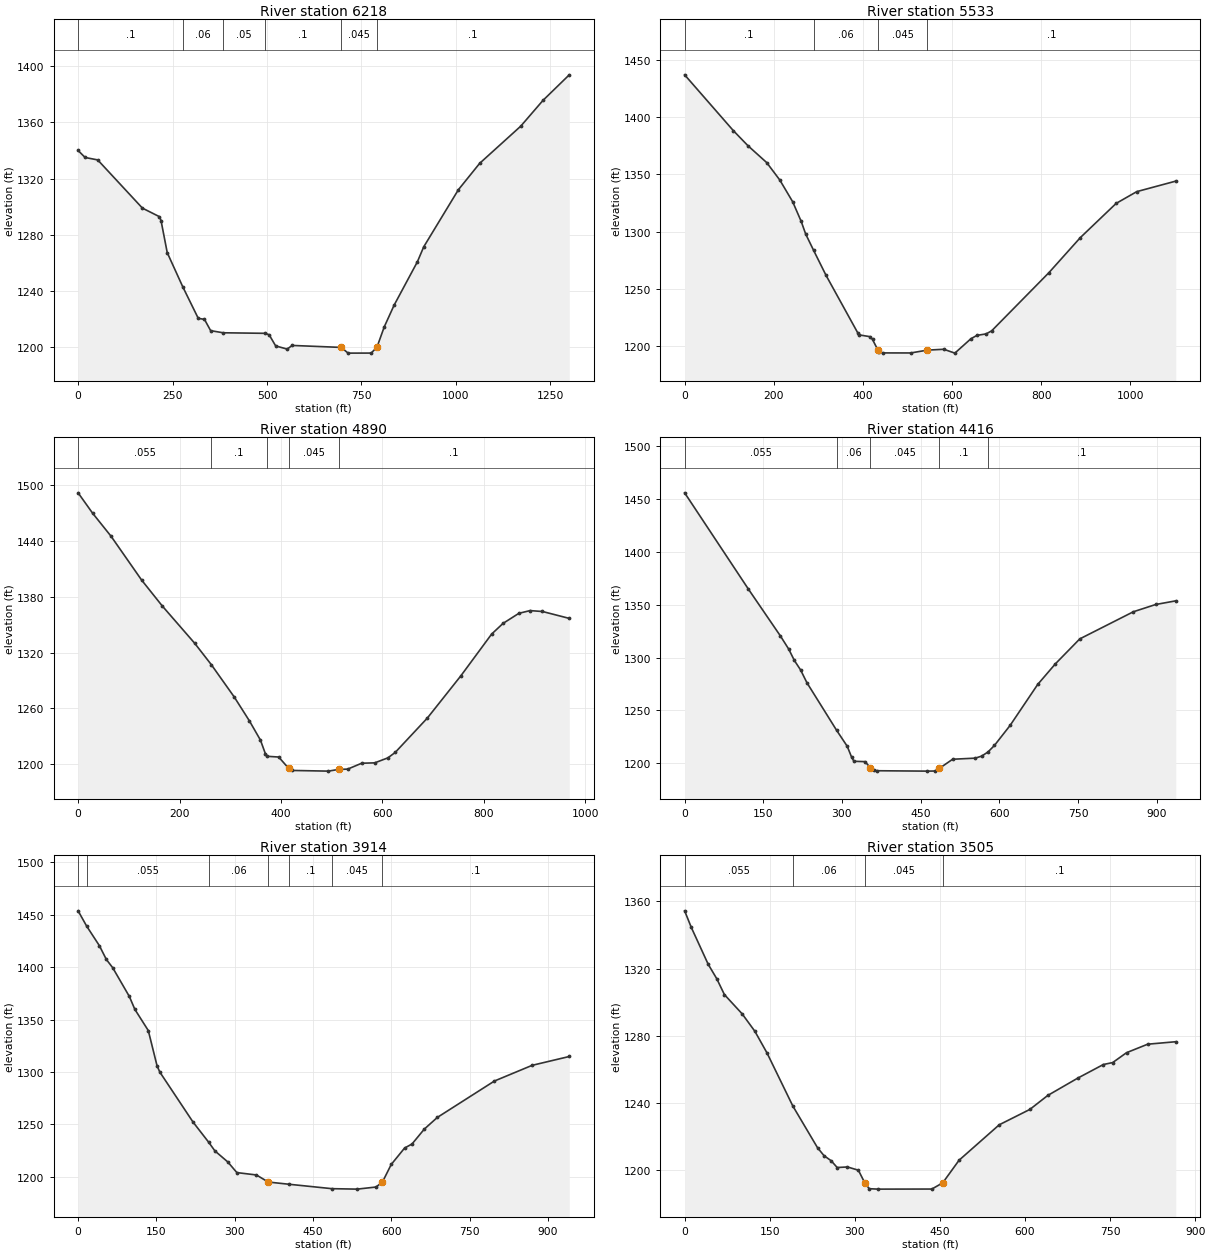
Type RM Length L Ch R = 1 ,6218    ,650.8,685.5,627.8
XS GIS Cut Line= 4
2465308.71520815 690266.851887122465751.99510134690367.796813292
 2466190.8860847690556.5199361362466550.77669105690631.131403307
#Sta/Elev= 30
       0 1339.98    18.6    1335    51.9 1333.27   170.3 1298.97   215.4 1292.89
   219.5 1290.13   235.9 1267.33  276.731243.206     318 1220.61   334.4 1219.89
   350.8 1211.87  383.871210.349  494.611209.965   505.5 1208.97   522.9    1201
   553.4 1198.75   566.5 1201.35   696.6 1199.94   714.5 1195.88   775.7 1195.92
     791 1200.14   810.3 1214.59   836.4 1230.02   897.9 1260.81   914.8 1271.51
  1006.4 1312.06  1062.8 1330.85  1171.4 1357.25  1230.4 1375.62  1299.9 1393.78
#Mann= 6 ,-1 , 0
       0      .1       0  276.73     .06       0  383.87     .05       0
  494.61      .1       0   696.6    .045       0     791      .1       0
Bank Sta=696.6,791
XS Rating Curve= 0 ,0
Exp/Cntr(USF)=0,0
Exp/Cntr=0.3,0.1

Type RM Length L Ch R = 1 ,5533    ,707,642.2,486.3
XS GIS Cut Line= 4
2465098.04753614690859.3547146532465414.04904415690951.521821159
2465866.10675701691065.6334768322466146.99698636691188.522952172
#Sta/Elev= 30
       0 1436.94   109.1 1388.27   142.4 1374.89   184.1 1360.31   213.5 1345.08
   242.4 1326.08   261.5 1308.95   271.6 1297.87  289.471283.567   317.4  1261.7
   388.5 1211.53   391.8 1209.79   416.5 1208.22   421.5 1205.81     433 1197.04
   437.1 1194.89   445.4 1194.06   507.3 1194.03   544.4  1196.5   581.5 1197.24
   606.3 1193.88   642.1 1206.38   655.8 1209.39   676.4 1210.67   688.8 1213.33
   817.5 1264.23   887.8 1294.78   968.2 1324.67  1014.4 1334.93    1102 1344.12
#Mann= 4 ,-1 , 0
       0      .1       0  289.47     .06       0     433    .045       0
   544.4      .1       0
Bank Sta=433,544.4
XS Rating Curve= 0 ,0
Exp/Cntr(USF)=0,0
Exp/Cntr=0.3,0.1

Type RM Length L Ch R = 1 ,4890    ,508.1,474.5,441.8
XS GIS Cut Line= 4
2465383.32667532691838.0816075432465624.71671617691666.914124033
2466032.88533069691386.023894683 2466164.5526257691267.523329177
#Sta/Elev= 30
       0 1491.54    28.7  1469.6      65 1444.89   125.2 1397.88     166    1370
   229.8 1330.03   262.51307.115   308.1 1272.09   337.7 1246.69   359.5 1226.01
   369.3 1211.32   372.61208.554   395.5 1207.77   415.3 1195.57   421.1 1193.37
   493.5 1192.63   514.7 1194.54   531.5 1194.77   559.1  1201.1   584.9 1201.52
   610.9 1206.89   625.3 1212.72   688.6  1249.6   754.8 1295.04   815.4 1339.82
   837.9  1351.3   869.2 1362.14   891.2 1365.04   915.7 1364.08   968.5 1356.67
#Mann= 5 ,-1 , 0
       0    .055       0   262.5      .1       0   372.6     .06       0
   415.3    .045       0   514.7      .1       0
Bank Sta=415.3,514.7
XS Rating Curve= 0 ,0
Exp/Cntr(USF)=0,0
Exp/Cntr=0.3,0.1

Type RM Length L Ch R = 1 ,4416    ,457.1,502.3,509.6
XS GIS Cut Line= 4
2465826.60656851 692202.361123732465988.99623235692057.527099222
2466304.99774037691662.5252141992466419.10939604691482.579911022
#Sta/Elev= 30
       0 1455.86   121.5 1364.81   182.4  1320.6   198.5 1307.95   209.2 1297.25
     221 1288.36   233.2 1276.15   289.71231.231     310 1216.07   318.3 1205.84
   322.8 1201.85   343.9 1201.53   354.2 1195.82   361.3 1193.32   367.7 1192.91
   462.6 1192.55   477.1 1192.65   485.4 1195.05     511  1203.8   553.9 1204.82
   566.2 1206.73   578.41210.653   590.7 1216.87   620.5 1235.75   673.2 1274.58
     707 1294.12   753.4 1317.66   855.6 1343.34   898.3 1350.22   936.5 1353.66
#Mann= 5 ,-1 , 0
       0    .055       0   289.7     .06       0   354.2    .045       0
   485.4      .1       0   578.4      .1       0
Bank Sta=354.2,485.4
XS Rating Curve= 0 ,0
Exp/Cntr(USF)=0,0
Exp/Cntr=0.3,0.1

Type RM Length L Ch R = 1 ,3914    ,432,408.2,369.6
BEGIN DESCRIPTION:
Mannings N in channel placed 0.1 because of island in the channel
END DESCRIPTION:
XS GIS Cut Line= 4
2466120.66352736692518.3626317482466287.44210104 692373.52860724
2466642.94379756692070.6938287232466678.05507623691820.525968208
#Sta/Elev= 30
       0 1453.62   16.421439.013    40.8 1420.36    54.1 1407.25    66.3 1399.36
    98.1 1372.01   108.7 1359.67   134.4 1339.51   151.1 1306.07   156.4 1299.99
     220 1252.33  249.871233.166     262 1224.77   286.6 1214.29     304 1204.12
   341.4 1201.86   364.1 1195.12   403.9    1193   486.1 1188.79   534.4 1188.36
   570.4 1190.36   582.7 1195.06   599.6 1211.89   625.2 1227.54   639.4 1231.38
   662.9 1245.56   687.9 1256.72   797.3 1291.43   869.5 1306.37   940.5 1314.78
#Mann= 7 ,-1 , 0
       0      .1       0   16.42    .055       0  249.87     .06       0
   364.1    .045       0   403.9      .1       0   486.1    .045       0
   582.7      .1       0
Bank Sta=364.1,582.7
XS Rating Curve= 0 ,0
Exp/Cntr(USF)=0,0
Exp/Cntr=0.3,0.1

Type RM Length L Ch R = 1 ,3505    ,479.3,424.2,329.8
XS GIS Cut Line= 4
2466484.94304355692856.3086889342466599.05469922692702.696844759
2466840.44474007692338.417328571 2466792.1667319692105.805107391
#Sta/Elev= 30
       0  1354.4    11.7 1344.53    41.6 1322.47    56.6 1313.93    70.1 1304.44
   101.4 1292.95   123.8 1282.57   145.3 1269.58  190.721237.989   234.3 1213.09
   245.8 1208.34   258.3 1205.35   268.9  1201.3   287.1 1201.63   306.3 1199.69
     318 1191.87   325.5 1188.66   341.1 1188.41   435.8 1188.46     455 1192.16
   483.8 1205.65   554.6 1226.78   608.6 1235.95   640.1 1244.27   693.2 1254.65
   738.2 1262.74   754.6 1263.89     779 1269.78   816.3 1274.85   865.9 1276.33
#Mann= 4 ,-1 , 0
       0    .055       0  190.72     .06       0     318    .045       0
     455      .1       0
Bank Sta=318,455
XS Rating Curve= 0 ,0
Exp/Cntr(USF)=0,0
Exp/Cntr=0.3,0.1

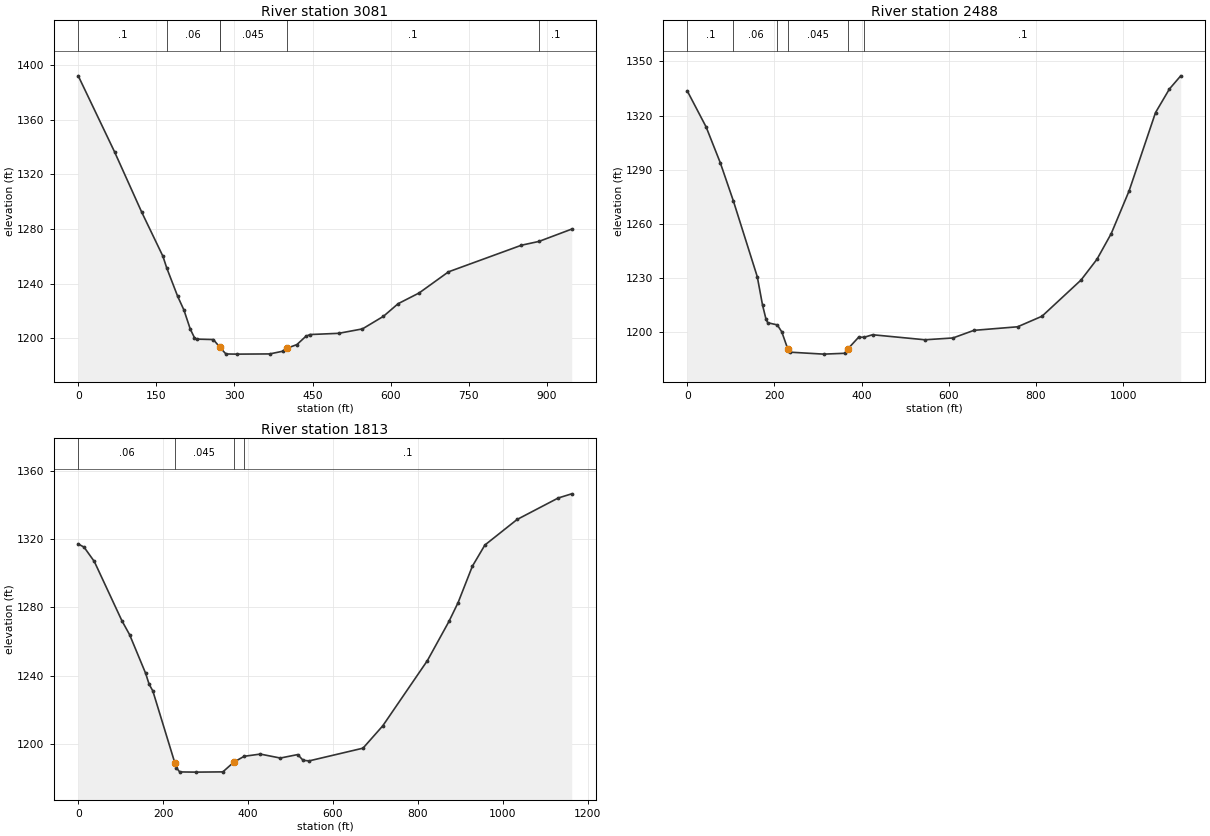
Type RM Length L Ch R = 1 ,3081    ,598.5,592.8,580.4
XS GIS Cut Line= 4
2466998.44549408693097.6987297812467033.55677275692939.697975772
2467099.39042025692417.4177055762467090.61260058692158.472025394
#Sta/Elev= 30
       0 1392.18    69.7 1336.53   121.7 1292.45   162.7 1259.89  169.981251.359
   190.9 1230.64     203 1220.52   215.1 1206.62   223.1 1200.34   227.2 1199.25
   259.4 1198.93  271.461193.535   272.1 1193.13   283.6 1188.37   304.4 1188.25
   367.7  1188.4   392.5 1190.36   400.5 1192.54   419.8 1195.23   436.8 1201.22
   444.9  1202.6   500.2  1203.5   545.7 1206.74     586 1215.97   614.2 1225.21
   654.5 1233.07   710.8 1248.54   850.9 1268.05  884.621270.845   947.4 1279.86
#Mann= 6 ,-1 , 0
       0      .1       0  169.98     .06       0  271.46      .1       0
   272.1    .045       0   400.5      .1       0  884.62      .1       0
Bank Sta=272.1,400.5
XS Rating Curve= 0 ,0
Exp/Cntr(USF)=0,0
Exp/Cntr=0.3,0.1

Type RM Length L Ch R = 1 ,2488    ,710.6,675.4,524.5
XS GIS Cut Line= 4
2467608.50396095693141.5878281172467630.44851011 693009.92053311
2467674.33760845692320.8616892372467617.28178061 692018.02691072
#Sta/Elev= 30
       0 1333.63    43.3 1313.67    75.7 1293.92  105.811272.748   160.6 1230.87
   172.6 1215.26   180.6  1207.4   184.6  1205.4  206.471204.196   216.7 1200.42
   230.8 1190.76   236.7  1189.1   312.9 1188.03     361 1188.49     369 1191.08
     393 1197.35  406.271197.394   425.1 1198.75   545.3 1195.97   609.5 1196.97
   657.6 1201.18   757.8 1203.15   813.9    1209   903.3    1229   939.9  1240.5
   972.6 1254.69  1013.7 1278.38  1074.2 1321.62  1106.1 1334.69  1132.1 1341.97
#Mann= 6 ,-1 , 0
       0      .1       0  105.81     .06       0  206.47      .1       0
   230.8    .045       0     369    .055       0  406.27      .1       0
Bank Sta=230.8,369
XS Rating Curve= 0 ,0
Exp/Cntr(USF)=0,0
Exp/Cntr=0.3,0.1

Type RM Length L Ch R = 1 ,1813    ,644.3,647.8,612.6
XS GIS Cut Line= 4
2468389.72991132 693009.920533112468337.06299332692882.642147936
2468117.61750164692246.250222066 2468007.8947558691912.693074714
#Sta/Elev= 30
       0 1317.26    13.8 1315.35    37.9 1306.96   102.8 1272.25     121 1264.04
   158.6 1241.46   167.1 1234.89   175.6 1231.11   227.5 1188.86   230.6 1186.14
     239 1183.55   277.1 1183.43   340.6 1183.58     366  1189.2  390.771192.721
   428.8 1194.01   475.9 1191.69   516.9 1193.73   529.5 1190.37   543.7 1190.02
   670.6 1197.48   717.1 1210.58   822.2 1248.84   872.9 1271.77   894.5 1282.84
   928.1 1304.17   957.6 1316.61  1033.4 1331.59  1130.3  1344.2    1162 1346.64
#Mann= 4 ,-1 , 0
       0     .06       0   227.5    .045       0     366    .025       0
  390.77      .1       0
Bank Sta=227.5,366
XS Rating Curve= 0 ,0
Exp/Cntr(USF)=0,0
Exp/Cntr=0.3,0.1