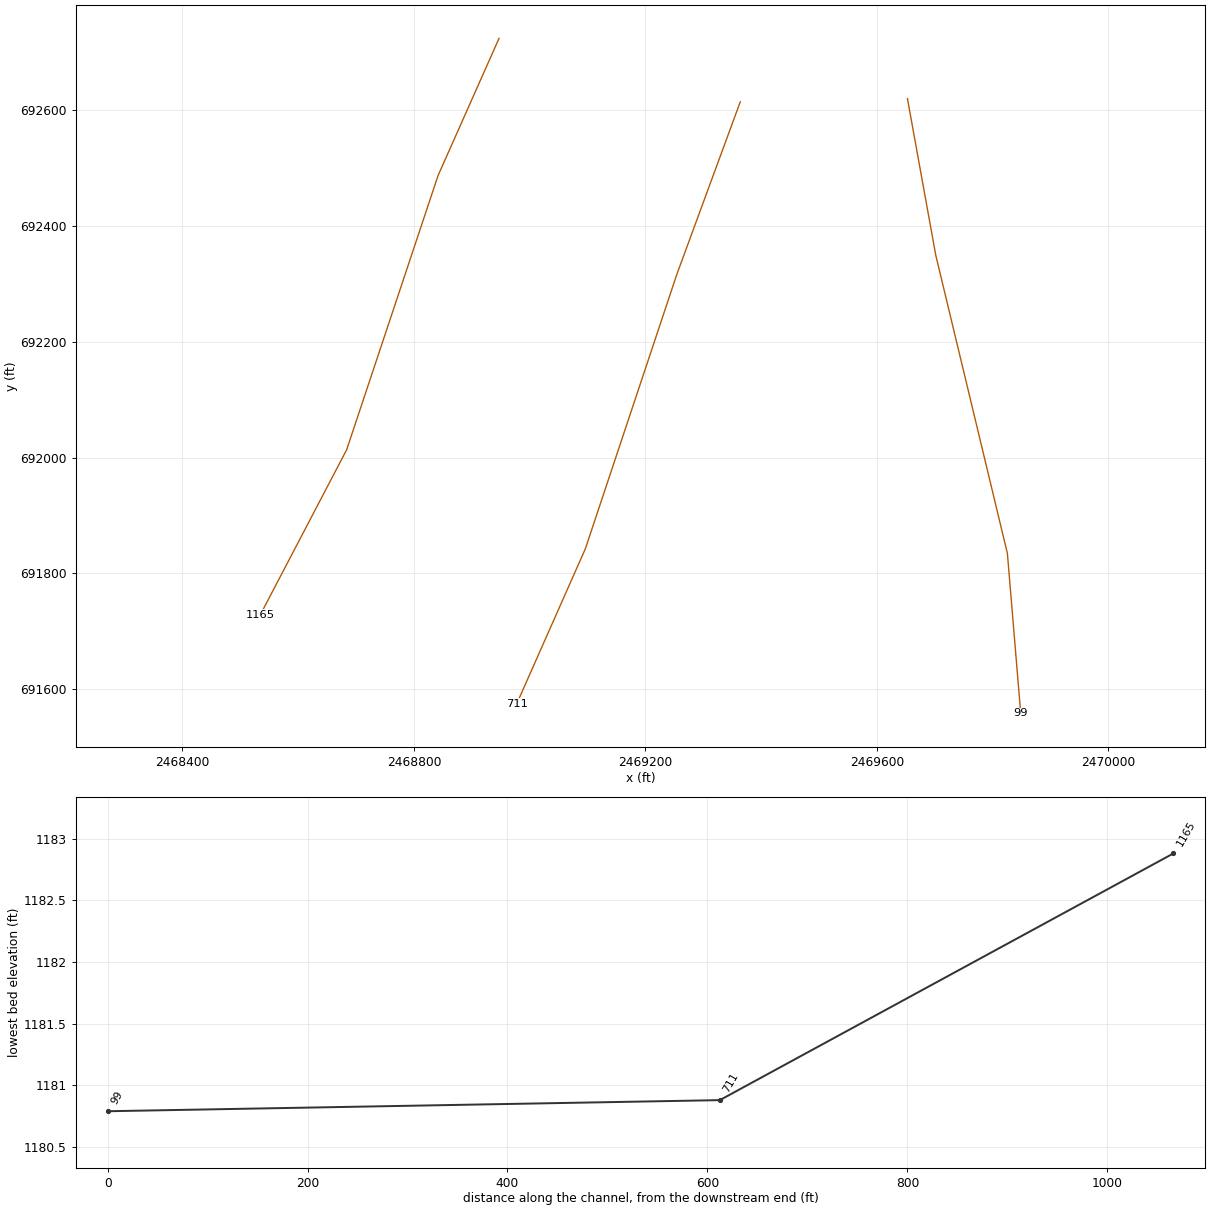
HEC-RAS study SBPOTOMC.prj: SBPOTOMC

--- SBPOTOMC.g01 (geometry) --- (continued)

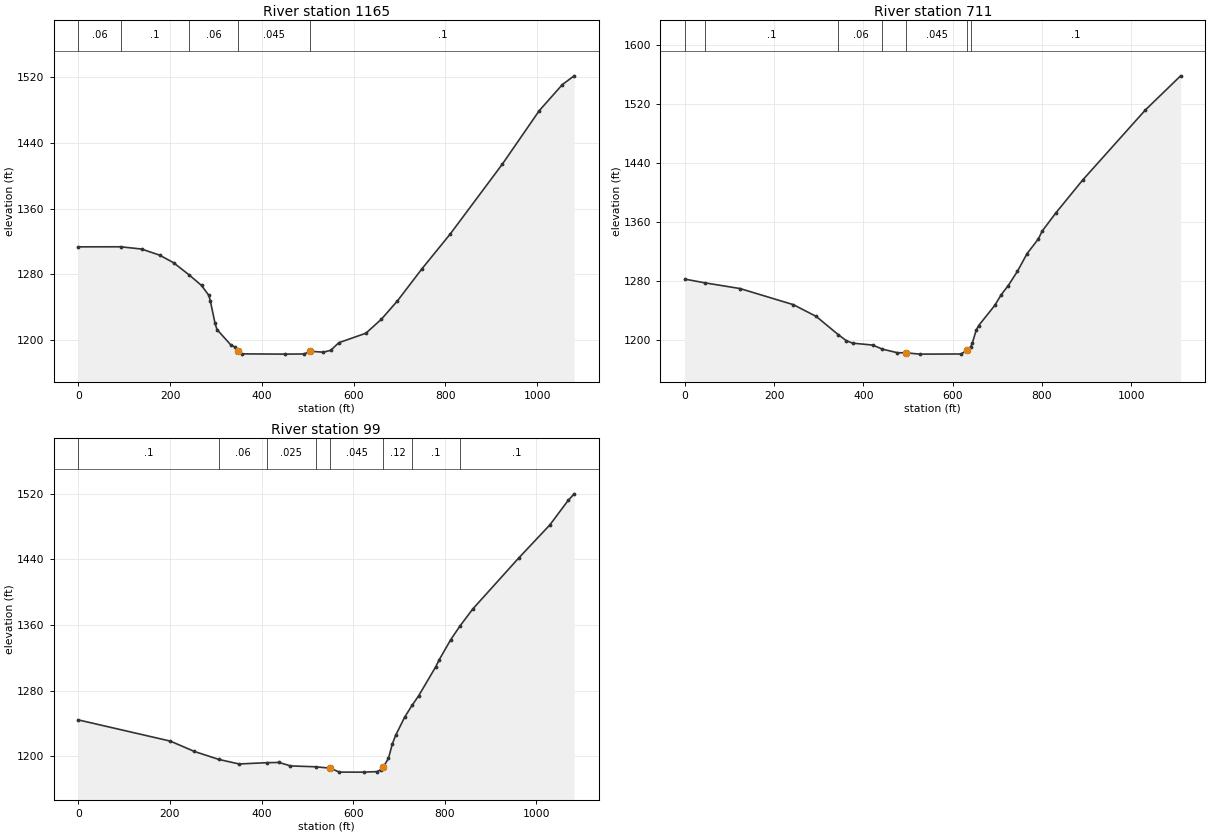
Type RM Length L Ch R = 1 ,1165    ,450.2,453.8,446.9
XS GIS Cut Line= 4
2468947.12146019692724.6413939272468841.78762418692487.640262913
2468683.78687017692013.6380008862468534.56393583691728.358861703
#Sta/Elev= 30
       0 1313.59   92.181313.676     138 1310.91     177 1303.52   207.7 1294.21
  241.761279.329   268.6 1266.53   284.5 1254.47   287.7 1247.81   298.1 1220.27
   302.3 1212.85   331.9 1194.46   341.4 1191.47   348.7 1186.97   357.1 1183.19
   449.9 1182.88     492 1183.07   505.8 1186.34   534.2 1185.25   550.1 1187.53
   567.9 1196.79     627  1208.4   660.8 1225.51   695.6 1247.72   749.2 1286.95
   810.4    1329   924.6 1414.58  1004.8 1479.53  1055.2 1511.33  1080.9 1521.97
#Mann= 5 ,-1 , 0
       0     .06       0   92.18      .1       0  241.76     .06       0
   348.7    .045       0   505.8      .1       0
Bank Sta=348.7,505.8
XS Rating Curve= 0 ,0
Exp/Cntr(USF)=0,0
Exp/Cntr=0.3,0.1

Type RM Length L Ch R = 1 ,711     ,486.6,612.4,664.1
XS GIS Cut Line= 4
2469364.06789438692614.9186480872469254.34514854692316.472779403
2469096.34439453691842.4705173762468977.84382902691574.747017528
#Sta/Elev= 30
       0 1282.53   45.441277.457   123.6 1269.77     243 1247.95   294.4 1231.96
  343.771207.246   361.8 1199.08   375.8 1195.77   420.8 1193.15   442.7 1187.63
   475.6 1182.83     496 1182.61   526.2 1180.88   618.4 1181.09   631.7  1185.9
  640.551191.165   644.3 1196.54   652.7 1213.65   658.2 1219.65   694.3 1247.03
   708.8 1261.62   724.4 1273.82   744.9 1293.13   766.6 1317.16   791.9 1337.09
   800.3 1347.61   830.6 1371.98   890.7 1416.62  1031.5 1511.84  1110.4 1558.08
#Mann= 7 ,-1 , 0
       0      .1       0   45.44      .1       0  343.77     .06       0
   442.7      .1       0     496    .045       0   631.7    .055       0
  640.55      .1       0
Bank Sta=496,631.7
XS Rating Curve= 0 ,0
Exp/Cntr(USF)=0,0
Exp/Cntr=0.3,0.1

Type RM Length L Ch R = 1 ,99      ,99,99,99
XS GIS Cut Line= 4
2469653.01555332692620.4383045092469701.96813695692349.759312711
2469825.78937788691834.3174027992469848.82588782691557.879283516
#Sta/Elev= 30
       0 1244.42   200.8 1218.58   253.6 1205.93  306.941196.237   351.1 1190.72
  412.391192.331   438.5 1192.54   463.1 1188.38  517.851187.301   549.5 1185.64
   570.1 1180.81   623.6 1180.79   652.4 1181.41   660.6 1183.95   666.2 1187.41
   677.1 1197.42   685.3 1214.68   692.7 1225.43   712.6 1247.87  728.751262.225
   742.9 1273.63   779.9 1308.73   788.1 1317.84   812.9 1342.03   832.81358.422
   861.1  1379.5   961.1 1441.41  1029.4 1481.91  1069.5 1511.83  1082.6 1519.86
#Mann= 8 ,-1 , 0
       0      .1       0  306.94     .06       0  412.39    .025       0
  517.85      .1       0   549.5    .045       0   666.2     .12       0
  728.75      .1       0   832.8      .1       0
Bank Sta=549.5,666.2
XS Rating Curve= 0 ,0
Exp/Cntr(USF)=0,0
Exp/Cntr=0.3,0.1
Stream Node=SBPOTOMC        ,Main            , 0 , 0 ,Upstream end
Stream Node=SBPOTOMC        ,Main            , 0 , 1 ,Downstream end
LCMann Table=0

Chan Stop Cuts=-1
Use User Specified Reach Order=0
Composite Channel Slope=5